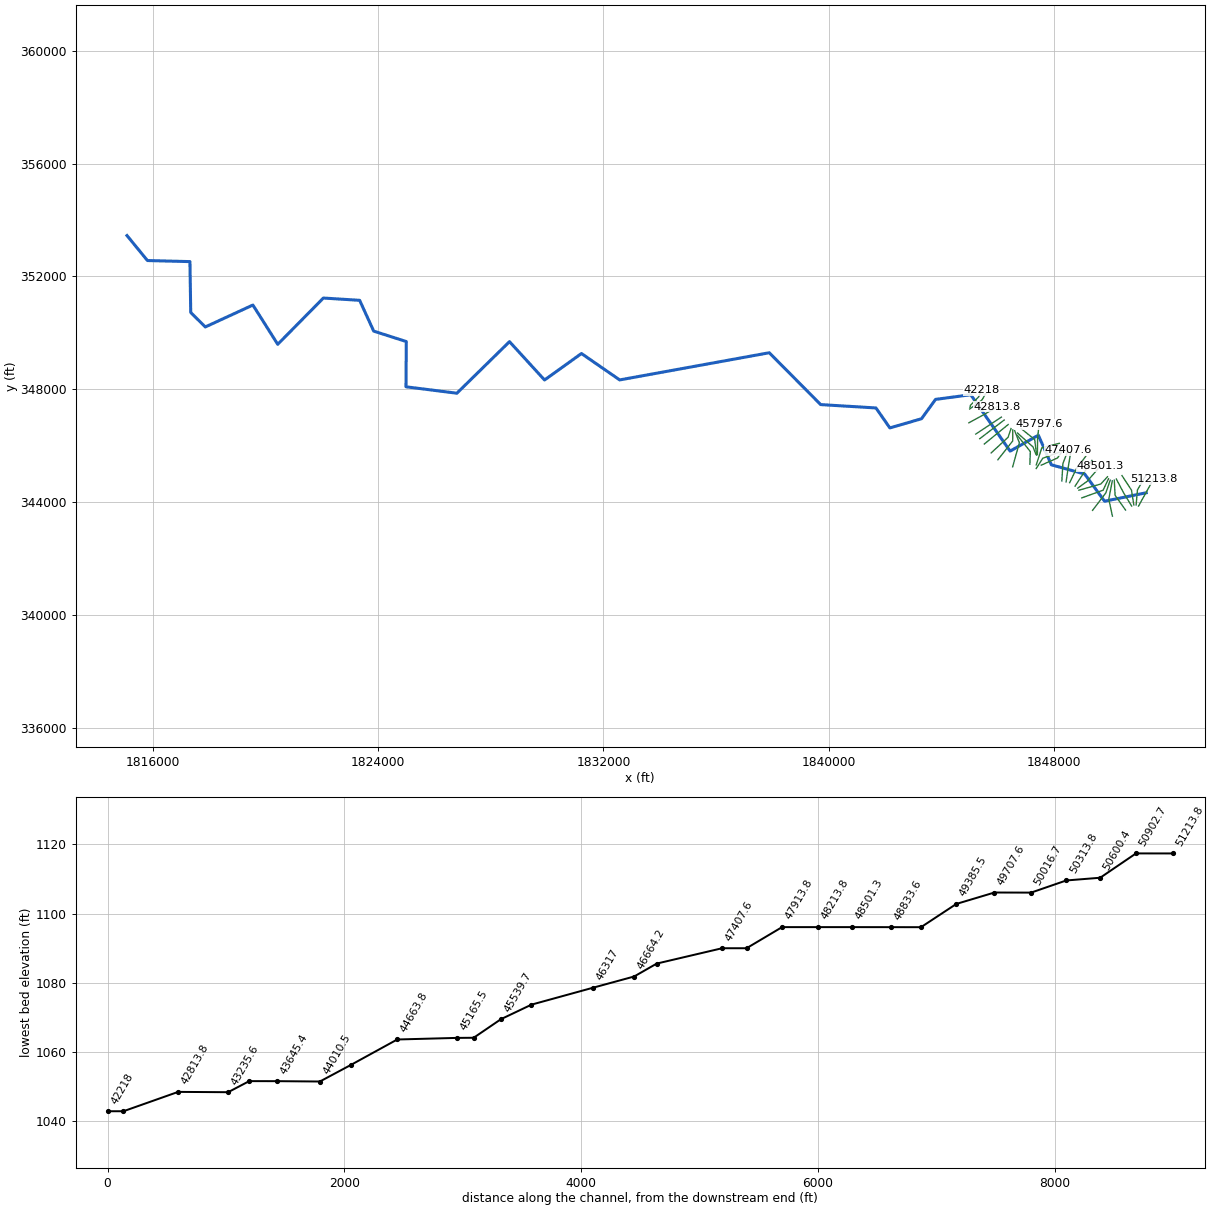
--- ClrFrk1.prj (project) ---

Proj Title=ClrFrk1
Current Plan=p01
Default Exp/Contr=0,0
English Units
Geom File=g01
Flow File=f01
Plan File=p01
BEGIN DESCRIPTION:
END DESCRIPTION:
DSS Export Rating Curves= 0
DSS Export Rating Curve Sorted= 0
DSS Export Volume Flow Curves= 0
DXF OffsetX= 0
DXF OffsetY= 0
DXF ScaleX= 0
DXF ScaleY= 0

--- ClrFrk1.p01 (plan) ---

Plan Title=Floodplain
Program Version=4.00
Geom File=g01
Flow File=f01
K Sum by GR=0
Std Step Tol=0.01
Critical Tol=0.01
Num of Std Step Trials=20
Max Error Tol=0.3
Flow Tol Ratio=0.001
Split Flow NTrial=30
Split Flow Tol=0.02
Split Flow Ratio=0.02
Log Output Level=0
Friction Slope Method=1
Unsteady Friction Slope Method=2
Unsteady Bridges Friction Slope Method=1
Global Log Level=0
CheckData=False
Run HTab=0
Run UNet=0
Run PostProcess=0
UNET Theta=0
UNET Theta Warmup=0
UNET ZTol=0
UNET ZSATol=0
UNET MxIter=0
UNET MaxInSteps=0
UNET DtIC=0
UNET DtMin=0
UNET MaxCRTS=0
UNET WFStab=0
UNET SFStab=0
UNET WFX=0
UNET SFX=0
UNET DSS MLevel=0
UNET DZMax Abort=0
UNET Convert EG Bridges=0
UNET Use Existing IB Tables=0
UNET Froude Limit=0
UNET Froude Power=0
Write IC File=0
Echo Input=False
Echo Output=False
Write Detailed=0

--- ClrFrk1.f01 (steady flow) ---

Flow Title=NFF Regression Equation
Program Version=4.00
Number of Profiles=1
Profile Names=P100yr
River Rch & RM=ClrFrk1,Main      ,51213.8
6495.690
River Rch & RM=ClrFrk1,Main      ,38611.5
6971.407
River Rch & RM=ClrFrk1,Main      ,38038.5
8086.133
River Rch & RM=ClrFrk1,Main      ,32613.8
8230.639
River Rch & RM=ClrFrk1,Main      ,213.8
9141.487
Boundary for River Rch & Prof#=ClrFrk1,Main      ,1
Up Type=0
Dn Type=3
Dn Slope=0.005907

--- ClrFrk1.g01 (geometry) ---

Geom Title=USGS 3m DEM
Program Version=4.10

River Reach=ClrFrk1         ,Main
Reach XY= 30
     1851267.695      344328.957     1849788.545      344028.665
     1849083.917       344992.53     1847899.954      345320.787
     1847438.896       346370.61     1846436.441      345805.785
     1845038.429      347806.017     1843789.333       347640.63
     1843291.763      346954.227     1842168.116      346629.153
     1841674.074        347337.2     1839713.824      347455.775
     1837887.774       349294.94     1832578.795      348331.229
     1831221.634      349267.849     1829912.381       348328.26
     1828667.238      349688.091     1826800.724      347859.447
     1824994.179      348087.431     1825004.643      349692.095
     1823848.044      350062.032     1823349.222      351154.832
     1822062.368       351235.62     1820442.032      349594.533
     1819560.288      350986.913     1817870.541      350209.779
     1817353.873      350723.873     1817325.702      352527.378
     1815817.429      352565.191     1815091.402      353451.438

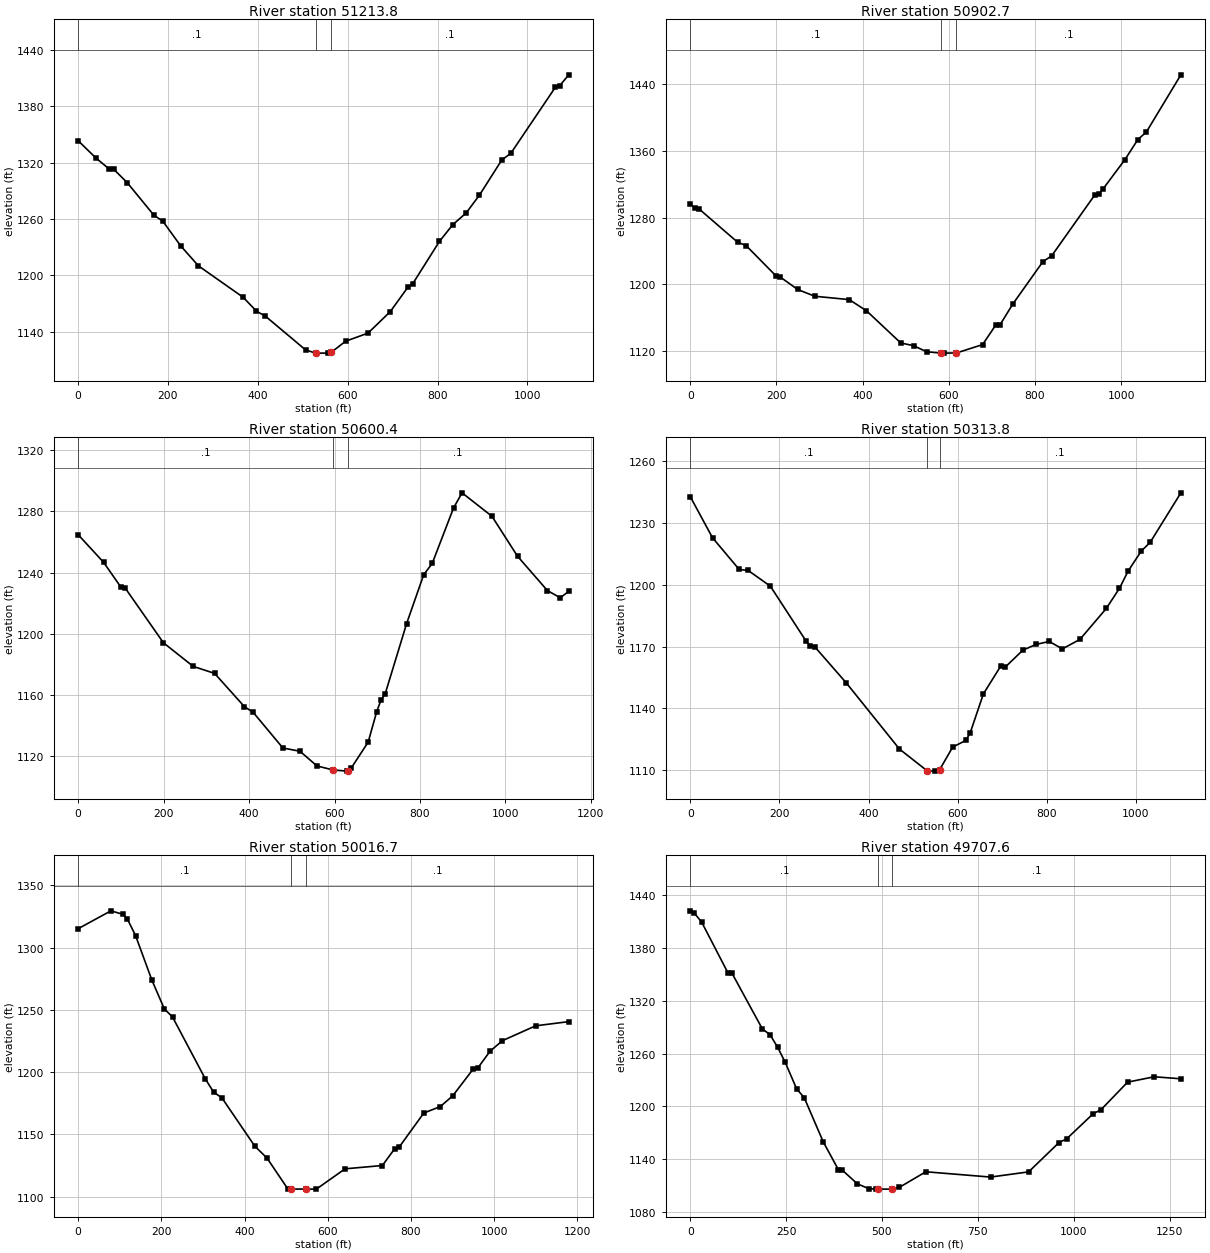
Type RM Length L Ch R = 1 ,51213.8 ,311.8,311.1,310.4
XS GIS Cut Line= 3
     1850993.774      343856.534     1851258.953      344333.814
     1851524.132      344811.094
#Sta/Elev= 30
       0 1343.52    39.7 1325.01    69.5 1313.17    79.4 1313.01   109.2 1298.88
   168.8 1264.11   188.6  1257.8   228.3 1231.57     268 1210.21   367.3 1176.86
   397.1    1162     417 1156.68   506.3 1120.84   528.5 1117.44   555.9 1117.39
   563.5 1118.28   595.6 1130.09   645.3 1138.68   694.9 1161.57   734.6 1187.89
   744.6 1191.06   804.1 1236.17   833.9 1254.07   863.7 1266.51   893.4 1285.58
   943.1 1322.95     963  1329.9  1062.2 1400.24  1072.2 1402.09    1092 1413.52
#Mann= 3 , 0 , 0
       0      .1       0   528.5    .045       0   563.5      .1       0
Bank Sta=528.5,563.5
XS Rating Curve= 0 ,0
Exp/Cntr=0.3,0.1

Type RM Length L Ch R = 1 ,50902.7 ,266,302.3,338.5
XS GIS Cut Line= 3
     1850908.968      343895.162     1850955.848      344431.442
     1851258.042      344949.869
#Sta/Elev= 30
       0 1296.64      10  1291.1    19.9 1290.57   109.7 1250.48   129.6 1246.36
   199.4 1209.78   209.4 1208.44   249.2 1193.72   289.1 1185.58   368.8 1181.59
   408.7 1168.29   488.5 1129.56   518.4 1126.32   548.3 1119.03   582.7 1117.41
   588.3  1117.4   617.7 1117.61   678.3 1127.62   708.4 1150.72   718.4 1151.02
   748.4 1176.25   818.4 1227.19   838.4 1233.92   938.4  1306.9   948.4 1308.62
   958.4 1314.68  1008.4 1349.26  1038.4 1373.36  1058.4 1382.59  1138.4 1451.09
#Mann= 3 , 0 , 0
       0      .1       0   582.7    .045       0   617.7      .1       0
Bank Sta=582.7,617.7
XS Rating Curve= 0 ,0
Exp/Cntr=0.3,0.1

Type RM Length L Ch R = 1 ,50600.4 ,287.6,286.6,283.5
XS GIS Cut Line= 3
     1850826.443      343897.154     1850745.481      344420.009
     1850407.098       344938.24
#Sta/Elev= 30
       0 1264.79    59.9 1246.64    99.8 1230.63   109.8 1230.06   199.7 1194.17
   269.5 1178.73   319.4 1174.19   389.3 1152.42   409.3 1148.88   479.2 1125.48
   519.1 1123.35     559 1113.75     596 1111.18   628.9 1110.37     631 1110.77
   638.9 1112.28   678.8 1129.35   698.8 1149.28   708.8 1156.76   718.8 1161.04
   768.7  1206.7   808.6 1238.54   828.6 1245.96   878.5 1282.18   898.4 1292.06
   968.3 1276.77  1028.2 1250.66  1098.1 1228.27    1128 1223.57    1148 1227.69
#Mann= 3 , 0 , 0
       0      .1       0     596    .045       0     631      .1       0
Bank Sta=596,631
XS Rating Curve= 0 ,0
Exp/Cntr=0.3,0.1

Type RM Length L Ch R = 1 ,50313.8 ,294.8,297.1,301.4
XS GIS Cut Line= 3
     1850750.289      343857.376     1850464.374      344326.594
     1850207.419      344814.516
#Sta/Elev= 30
       0 1242.74      50 1222.78   109.9 1207.38   129.9 1206.93   179.8 1199.29
   259.8  1172.7   269.7 1170.21   279.7 1169.82   349.7 1152.49   469.5 1120.27
     532 1109.67   549.5 1109.58   559.3 1110.16   588.9 1121.25   618.4 1124.47
   628.2 1128.17   657.8 1147.06   697.2 1160.69     707 1160.06   746.4 1168.27
     776 1171.04   805.5 1172.48     835 1168.87   874.4 1173.48   933.5 1188.47
     963 1198.22   982.8 1206.73  1012.3 1216.38    1032 1220.55  1100.9 1244.57
#Mann= 3 , 0 , 0
       0      .1       0     532    .045       0   559.3      .1       0
Bank Sta=532,559.3
XS Rating Curve= 0 ,0
Exp/Cntr=0.3,0.1

Type RM Length L Ch R = 1 ,50016.7 ,322.3,309.1,295.9
XS GIS Cut Line= 3
      1850532.96      343715.606       1850162.4      344239.368
     1850133.285      344775.971
#Sta/Elev= 30
       0 1315.23      79 1329.61   108.6 1326.72   118.4 1323.07   138.2 1309.66
   177.7 1273.66   207.3 1250.83     227 1244.31     306 1194.46   325.7 1183.97
   345.5 1179.44   424.4 1140.68     454 1131.02   503.4 1106.55   512.7 1106.15
   547.7  1106.1   572.5 1106.07   641.6 1122.38   731.2 1125.04     761 1138.59
     771 1139.55   830.7 1167.18   870.5 1172.41   900.3 1181.03   950.1 1202.81
     960 1203.14   989.9 1216.83  1019.8 1225.33  1099.4 1237.24    1179 1240.61
#Mann= 3 , 0 , 0
       0      .1       0   512.7    .045       0   547.7      .1       0
Bank Sta=512.7,547.7
XS Rating Curve= 0 ,0
Exp/Cntr=0.3,0.1

Type RM Length L Ch R = 1 ,49707.6 ,350.3,322.1,294
XS GIS Cut Line= 3
     1850068.448      343499.422     1849938.314      344099.886
      1850063.14      344753.247
#Sta/Elev= 30
       0 1422.07     9.9 1419.87    29.7 1409.33    99.1 1350.99     109 1351.13
   188.3 1287.86   208.1 1281.51   227.9 1267.16   247.7 1250.09   277.5 1219.91
   297.3 1209.95   346.8 1159.84   386.5  1128.1   396.4 1127.67     436 1112.08
   465.8 1106.61   485.6  1106.1   490.4  1106.1   525.4 1106.11     545    1108
   614.4 1125.81   783.2 1119.79   882.5 1125.69   961.9 1159.03   981.7 1163.18
  1051.2 1191.86  1071.1 1196.19  1140.6 1227.56  1210.1 1233.67  1279.6 1231.38
#Mann= 3 , 0 , 0
       0      .1       0   490.4    .045       0   525.4      .1       0
Bank Sta=490.4,525.4
XS Rating Curve= 0 ,0
Exp/Cntr=0.3,0.1

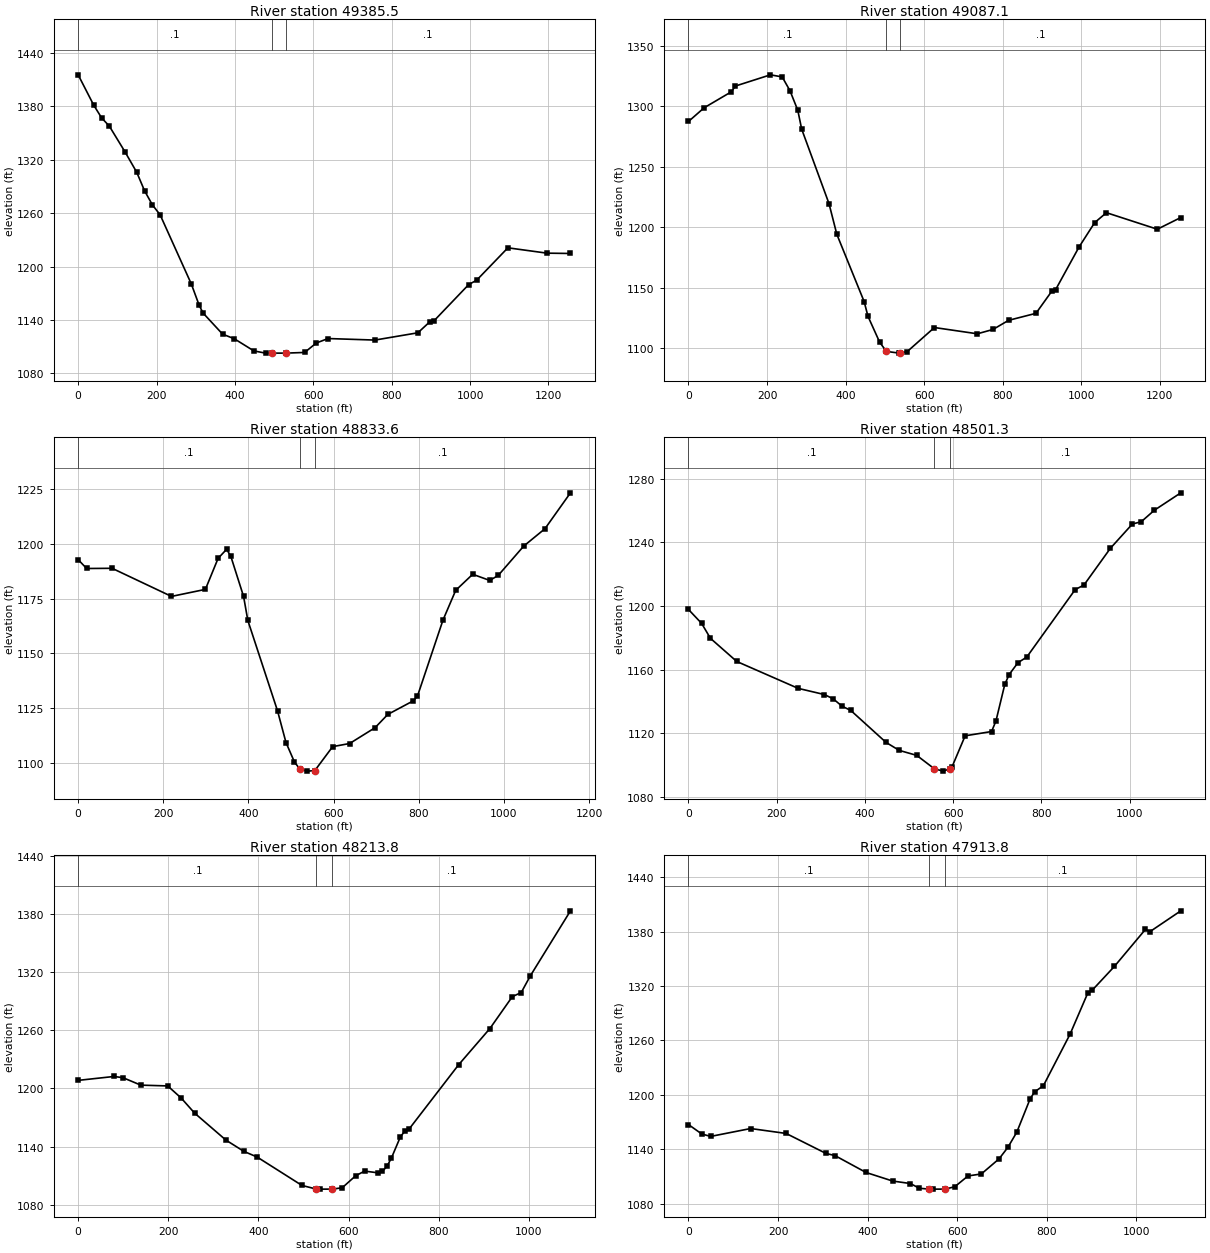
Type RM Length L Ch R = 1 ,49385.5 ,317.5,298.4,279.3
XS GIS Cut Line= 3
     1849363.095      343705.066      1849833.13      344323.972
     1849990.416      344776.597
#Sta/Elev= 30
       0  1415.3    39.8 1381.18    59.8 1367.02    79.7 1357.58   119.6 1328.78
   149.4 1305.94   169.4 1285.16   189.3 1269.38   209.2 1258.07   288.9 1180.31
   308.9  1156.4   318.8  1147.8   368.6  1124.1   398.5 1118.93   448.4 1105.28
   478.2  1102.8   494.4  1102.8   529.4  1102.8   577.9 1103.55   607.8  1114.2
   637.7 1119.18   757.2 1117.46     867 1125.64     897 1137.85   906.9 1138.53
   996.8 1179.86  1016.8 1184.63  1096.6 1221.06  1196.4 1215.05  1256.3  1214.7
#Mann= 3 , 0 , 0
       0      .1       0   494.4    .045       0   529.4      .1       0
Bank Sta=494.4,529.4
XS Rating Curve= 0 ,0
Exp/Cntr=0.3,0.1

Type RM Length L Ch R = 1 ,49087.1 ,255.8,253.5,251.2
XS GIS Cut Line= 3
     1848979.915      344147.306     1849737.094      344420.009
     1849928.419      344825.604
#Sta/Elev= 30
       0 1287.51    39.7  1298.8   109.3 1312.08   119.2 1316.77   208.6 1326.06
   238.5 1324.33   258.3 1312.96   278.2 1296.79   288.1 1281.23   357.7 1219.62
   377.6 1194.28   447.1 1138.69     457 1126.41   486.8 1104.98   503.9 1097.49
   536.5 1096.08   538.9 1096.11   556.4 1097.24     626 1117.24   735.2 1112.06
     775 1115.62   814.8 1123.18   884.5 1128.97   924.4 1147.07   934.3 1148.38
   994.1 1183.74    1034 1203.94  1063.9 1212.13  1193.4 1198.47  1253.2 1208.13
#Mann= 3 , 0 , 0
       0      .1       0   503.9    .045       0   538.9      .1       0
Bank Sta=503.9,538.9
XS Rating Curve= 0 ,0
Exp/Cntr=0.3,0.1

Type RM Length L Ch R = 1 ,48833.6 ,312.7,332.2,351.7
XS GIS Cut Line= 3
      1848878.39      344419.738     1849654.776      344639.522
     1849892.021      344895.885
#Sta/Elev= 30
       0  1192.8    19.9 1188.74    79.7 1188.83   219.2 1175.98   298.8 1179.19
   328.7  1193.4   348.7 1197.53   358.6 1194.26   388.5 1175.96   398.5 1164.98
   468.2 1123.67   488.1 1109.16     508 1100.24   520.7 1097.03   537.9 1096.09
   555.7 1096.31   597.7 1107.29   637.6 1108.72   697.3 1115.95   727.2 1122.02
     787 1128.23   796.9 1130.41   856.8 1165.16   886.7 1178.76   926.6  1186.1
   966.6 1183.28   986.5 1185.57  1046.4 1198.98  1096.3 1206.93  1156.2 1223.34
#Mann= 3 , 0 , 0
       0      .1       0   520.7    .045       0   555.7      .1       0
Bank Sta=520.7,555.7
XS Rating Curve= 0 ,0
Exp/Cntr=0.3,0.1

Type RM Length L Ch R = 1 ,48501.3 ,283.3,287.5,291.8
XS GIS Cut Line= 3
     1848836.038      344493.316     1849174.592      344737.845
       1849631.4      345265.933
#Sta/Elev= 30
       0 1197.79    29.8 1189.04    49.7 1179.66   109.4 1165.09   248.6 1148.17
   308.2 1144.27   328.1 1141.56     348 1136.96   367.9 1134.27   447.6 1114.21
   477.5 1109.17   517.4    1106   557.2 1097.59   577.2  1096.1   592.2 1097.46
   597.2 1098.67   627.1 1118.32     687 1121.02   696.9 1127.64   716.9 1150.62
   726.8 1156.85   746.8 1164.33   766.8 1167.86   876.5 1210.31   896.4 1213.18
   956.3  1236.3  1006.2 1251.59  1026.1 1252.97    1056 1260.24  1115.9 1271.19
#Mann= 3 , 0 , 0
       0      .1       0   557.2    .045       0   592.2      .1       0
Bank Sta=557.2,592.2
XS Rating Curve= 0 ,0
Exp/Cntr=0.3,0.1

Type RM Length L Ch R = 1 ,48213.8 ,295.6,300,297.9
XS GIS Cut Line= 3
     1848740.865      344564.697     1849041.262      345020.633
      1849341.66      345476.569
#Sta/Elev= 30
       0 1208.29    79.4 1212.31    99.3 1211.09     139 1203.38   198.6 1202.56
   228.3 1190.19   258.1 1174.61   327.6 1146.74   367.3 1135.12   397.1 1129.18
   496.4 1099.91   528.5 1096.13   536.1  1096.1   563.5  1096.1   585.7 1097.51
   615.5 1109.88   635.4  1114.7   665.1 1112.92     675 1114.48     685 1119.63
   694.9 1128.25   714.8 1150.09   724.7    1156   734.6  1158.4   843.8 1224.34
   913.3 1261.78     963 1294.66   982.8 1298.93  1002.6 1315.84    1092  1383.2
#Mann= 3 , 0 , 0
       0      .1       0   528.5    .045       0   563.5      .1       0
Bank Sta=528.5,563.5
XS Rating Curve= 0 ,0
Exp/Cntr=0.3,0.1

Type RM Length L Ch R = 1 ,47913.8 ,290.1,300,315.8
XS GIS Cut Line= 3
     1848550.341      344687.949     1848792.144      345187.548
      1849120.34      345621.903
#Sta/Elev= 30
       0 1167.27    29.7 1156.88    49.6 1154.22   138.8  1162.9     218 1157.49
   307.2 1135.42   327.1 1133.08   396.5 1114.46   455.9 1105.02   495.6 1102.26
   515.4 1097.07   537.5 1096.12   545.1  1096.1   572.5  1096.1   594.6 1098.71
   624.3 1110.65     654 1112.83   693.6  1129.5   713.4 1142.26   733.2 1158.93
   762.9 1195.62   772.8 1203.27   792.6 1210.18     852 1266.82   891.6 1312.19
   901.5 1315.34     951 1341.56  1020.3 1382.38  1030.2 1379.85  1099.4 1402.91
#Mann= 3 , 0 , 0
       0      .1       0   537.5    .045       0   572.5      .1       0
Bank Sta=537.5,572.5
XS Rating Curve= 0 ,0
Exp/Cntr=0.3,0.1

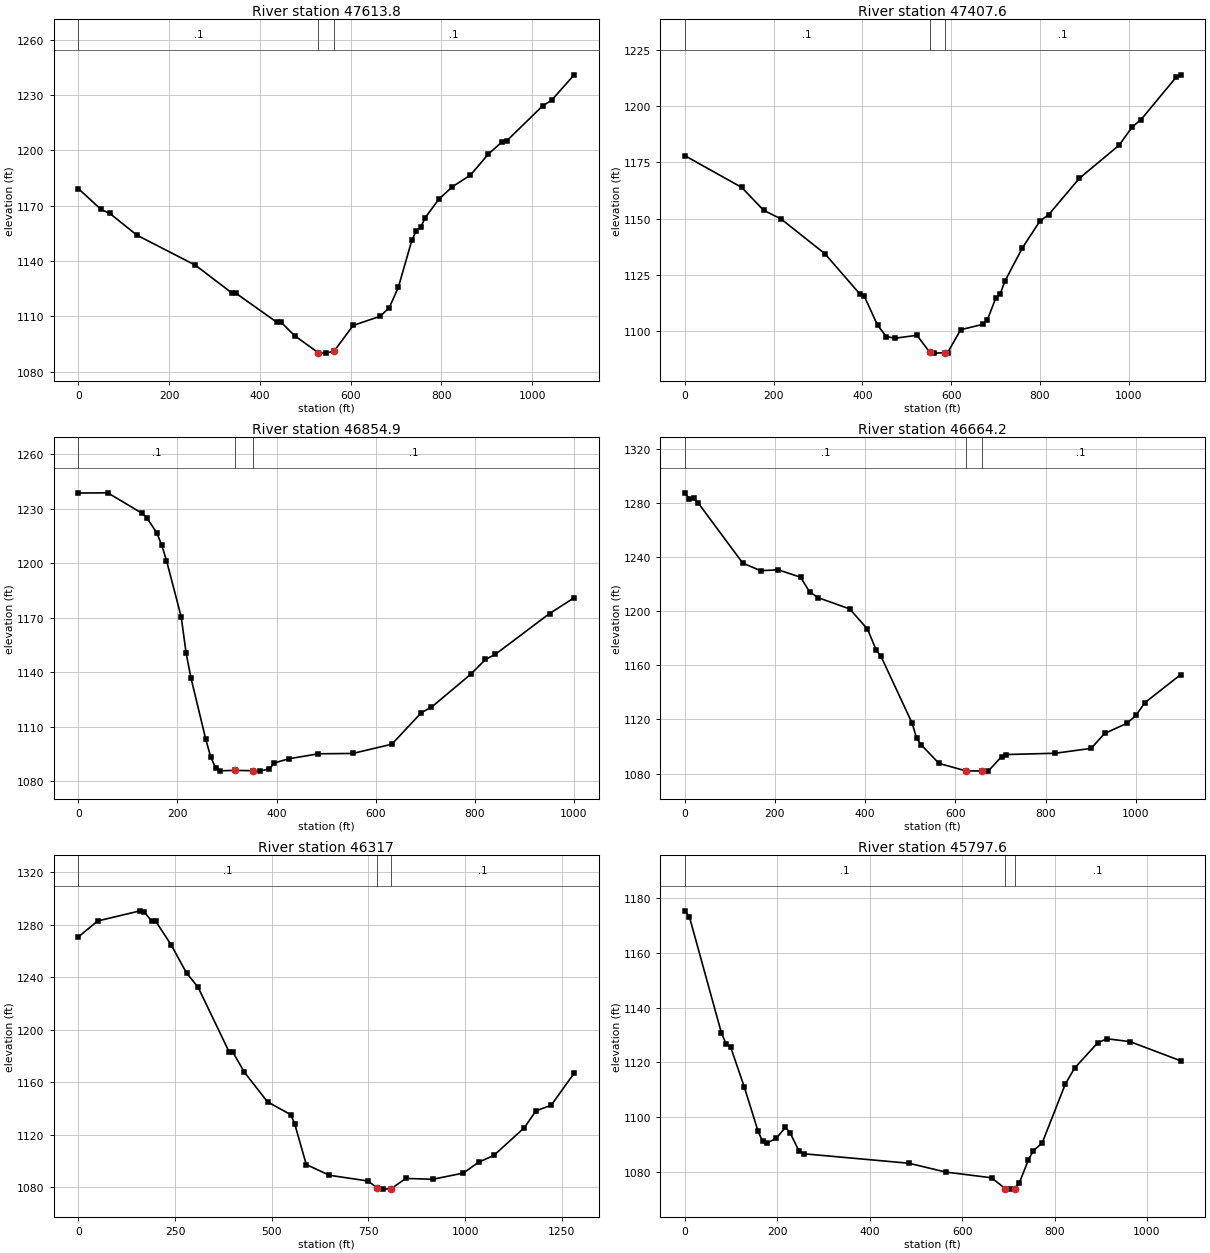
Type RM Length L Ch R = 1 ,47613.8 ,202.8,206.2,209.8
XS GIS Cut Line= 3
     1848423.149      344715.233     1848502.594      345255.364
     1848591.643      345794.382
#Sta/Elev= 30
       0 1179.29    49.6 1168.07    69.5 1165.79     129 1154.03   258.1 1137.69
   337.5 1122.79   347.4 1122.47   436.8 1106.84   446.7 1106.77   476.5 1099.47
   528.4 1090.26   545.9    1090   563.4 1091.06   605.5 1105.04   665.1 1109.99
     685 1114.69   704.9 1125.65   734.7 1151.21   744.6 1156.38   754.5 1158.51
   764.5  1163.6   794.3 1173.58   824.1  1180.3   863.8 1186.61   903.5 1198.05
   933.3 1204.64   943.3 1205.09  1022.7 1224.16  1042.6 1227.24  1092.3 1241.04
#Mann= 3 , 0 , 0
       0      .1       0   528.4    .045       0   563.4      .1       0
Bank Sta=528.4,563.4
XS Rating Curve= 0 ,0
Exp/Cntr=0.3,0.1

Type RM Length L Ch R = 1 ,47407.6 ,589,552.6,516.7
XS GIS Cut Line= 3
     1848272.081      344746.105     1848310.259      345366.658
     1848490.463      345828.054
#Sta/Elev= 30
       0 1178.04   128.3 1163.85   177.6 1153.68   217.1 1149.76   315.8 1134.28
   394.8 1116.27   404.6 1115.27   434.2 1102.48     454 1097.38   473.7 1096.65
     523 1097.95   551.4 1090.52   562.5    1090   586.4 1090.19   592.1  1090.2
   621.7 1100.44   671.3 1102.82   681.2 1104.61     701 1114.71   710.9 1116.53
   720.8 1121.94   760.4 1136.83     800 1148.84   819.9 1151.74   889.2 1167.97
   978.4 1182.66  1008.1 1190.84  1027.9 1194.08  1107.2 1213.03  1117.1 1214.05
#Mann= 3 , 0 , 0
       0      .1       0   551.4    .045       0   586.4      .1       0
Bank Sta=551.4,586.4
XS Rating Curve= 0 ,0
Exp/Cntr=0.3,0.1

Type RM Length L Ch R = 1 ,46854.9 ,192.8,190.6,188.5
XS GIS Cut Line= 3
     1847539.677      345307.207     1848118.185      345563.305
     1848329.817      345864.126
#Sta/Elev= 30
       0 1238.54    59.3 1238.66   128.5 1227.44   138.4 1224.87   158.2 1216.69
     168 1210.09   177.9 1201.43   207.6 1170.41   217.5 1150.43   227.4 1136.71
     257 1103.23   266.9 1093.52   276.8 1087.45   286.7 1085.75   316.7 1085.97
   351.7 1085.79   365.8 1085.56   385.5 1086.82   395.4 1090.06   425.1 1092.37
   484.4  1095.1   553.6 1095.28   632.7 1100.38   692.3 1117.77   712.2 1120.65
   791.7 1138.82   821.5 1146.98   841.4  1149.8   950.8 1172.25  1000.5 1180.91
#Mann= 3 , 0 , 0
       0      .1       0   316.7    .045       0   351.7      .1       0
Bank Sta=316.7,351.7
XS Rating Curve= 0 ,0
Exp/Cntr=0.3,0.1

Type RM Length L Ch R = 1 ,46664.2 ,350.6,347.2,343.9
XS GIS Cut Line= 3
     1847361.375      345188.836     1847596.842      345554.159
     1848221.082      345782.818
#Sta/Elev= 30
       0 1287.47     9.9 1283.13    19.8  1283.3    29.6 1280.03   128.4 1235.58
   167.9 1229.94   207.4 1230.57   256.8 1225.09   276.6  1214.3   296.3 1209.91
   365.5 1201.69     405 1186.88   424.8 1170.97   434.6 1166.96   504.1 1117.22
     514 1106.18   523.9  1101.4   563.6 1087.52   623.2 1082.04   658.2  1081.9
   672.8 1081.83   702.5 1092.62   712.5 1094.08   821.6 1095.05     901 1098.64
   930.8 1109.66   980.4 1117.18  1000.2 1122.96    1020 1132.36  1099.4 1153.12
#Mann= 3 , 0 , 0
       0      .1       0   623.2    .045       0   658.2      .1       0
Bank Sta=623.2,658.2
XS Rating Curve= 0 ,0
Exp/Cntr=0.3,0.1

Type RM Length L Ch R = 1 ,46317   ,479.4,519.5,559.5
XS GIS Cut Line= 3
      1847363.61      345316.353     1847560.257      345924.587
     1848183.114      346082.891
#Sta/Elev= 30
       0 1270.75    49.9 1282.92   159.8 1290.66   169.8 1289.85   189.8 1282.84
   199.8  1282.8   239.7 1264.88   279.7 1243.32   309.6 1232.45   389.5 1183.38
   399.5 1182.96   429.5 1167.61   489.4 1145.02   549.3 1135.33   559.3 1128.41
   589.3 1097.33   649.1 1089.16     748 1084.82   773.3 1079.54   787.5 1078.59
   808.3 1078.85   846.9 1086.74   916.1  1086.1   995.2  1090.8  1034.7 1099.06
  1074.3  1104.3  1153.4 1125.49    1183 1138.22  1222.6 1142.52  1281.9 1166.98
#Mann= 3 , 0 , 0
       0      .1       0   773.3    .045       0   808.3      .1       0
Bank Sta=773.3,808.3
XS Rating Curve= 0 ,0
Exp/Cntr=0.3,0.1

Type RM Length L Ch R = 1 ,45797.6 ,224.4,257.9,291.3
XS GIS Cut Line= 3
     1847404.768      345691.355     1847411.628       346265.29
     1847466.506      346761.099
#Sta/Elev= 30
       0 1175.39     9.9 1173.24    79.2 1130.78    89.1 1126.84      99  1125.7
   128.6 1111.07   158.3 1094.98   168.2 1091.16   178.1 1090.57   197.9 1092.24
   217.7 1096.27   227.6 1094.34   247.4 1087.52   257.3 1086.62   484.9 1083.16
   564.1 1079.95   663.8 1077.84   693.7 1073.83   703.7  1073.7   713.6 1073.92
   723.6  1075.9   743.6 1084.48   753.6 1087.57   773.5 1090.68   823.4 1112.12
   843.4 1117.92   893.2 1127.14   913.2 1128.64   963.1  1127.6  1072.8  1120.6
#Mann= 3 , 0 , 0
       0      .1       0   693.7    .045       0   713.6      .1       0
Bank Sta=693.7,713.6
XS Rating Curve= 0 ,0
Exp/Cntr=0.3,0.1

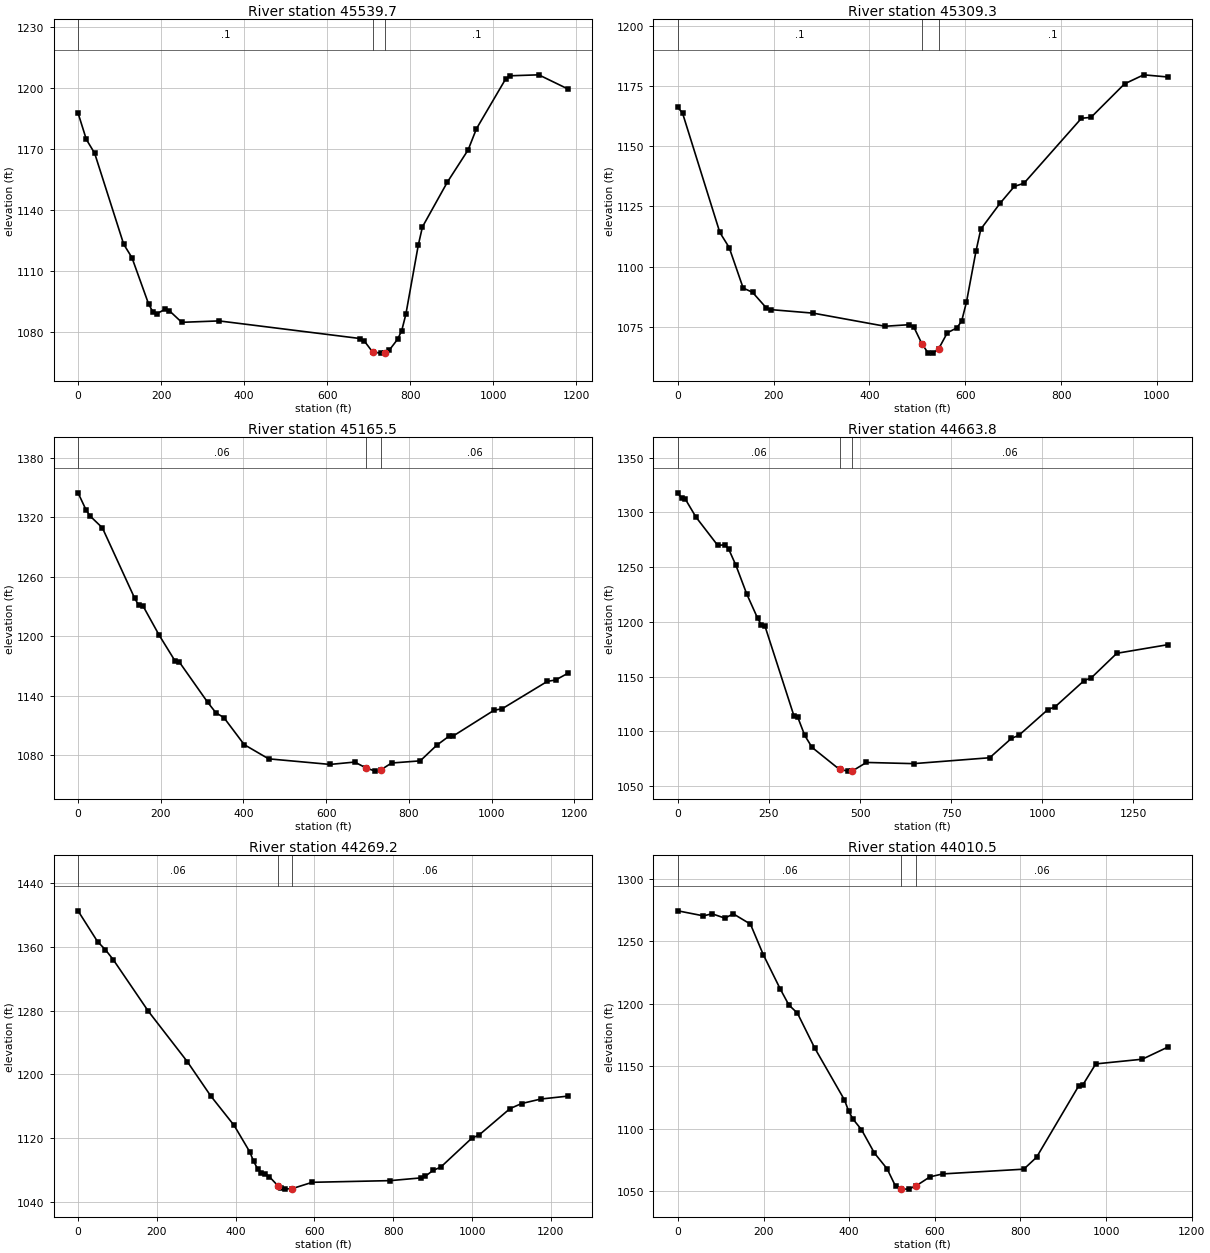
Type RM Length L Ch R = 1 ,45539.7 ,232.2,230.4,228.6
XS GIS Cut Line= 3
     1847378.091      345663.534     1847307.969      346218.414
      1846824.54      346606.421
#Sta/Elev= 30
       0 1187.52      20  1174.5      40 1167.73   109.9 1123.03   129.8 1116.42
   169.8  1093.7   179.8 1089.88   189.8 1088.87   209.7 1091.08   219.7 1090.36
   249.7 1084.64   339.6 1085.33   679.3 1076.67   689.3 1075.42   709.3 1070.03
   729.3  1069.5   739.3 1069.73   749.3 1070.96   769.2 1076.27   779.2 1080.48
   789.2 1088.55   819.2  1122.6   829.2 1131.54   889.2 1153.55   939.2 1169.38
   959.2 1179.76  1029.2 1204.12  1039.2 1205.78  1109.2 1206.26  1179.2 1199.33
#Mann= 3 , 0 , 0
       0      .1       0   709.3    .045       0   739.3      .1       0
Bank Sta=709.3,739.3
XS Rating Curve= 0 ,0
Exp/Cntr=0.3,0.1

Type RM Length L Ch R = 1 ,45309.3 ,149.3,143.8,138.2
XS GIS Cut Line= 3
     1847352.177      345691.355      1847249.28      345954.313
     1846698.211      346448.217
#Sta/Elev= 30
       0 1166.06     9.7 1163.75    87.6  1114.2   107.1 1107.95   136.3 1091.13
   155.8 1089.38     185 1082.81   194.7 1082.17   282.4 1080.72   432.4 1075.28
   482.4 1075.92   492.4 1075.03   509.3 1068.04   522.4 1064.17   532.4 1064.13
   544.3 1065.89   562.4 1072.55   582.4 1074.62   592.4 1077.43   602.4 1085.28
   622.4 1106.55   632.4 1115.58   672.4 1126.26   702.4 1133.31   722.4  1134.6
   842.4 1161.57   862.4 1161.95   932.4 1175.85   972.4  1179.6  1022.4 1178.71
#Mann= 3 , 0 , 0
       0      .1       0   509.3    .045       0   544.3      .1       0
Bank Sta=509.3,544.3
XS Rating Curve= 0 ,0
Exp/Cntr=0.3,0.1

Type RM Length L Ch R = 1 ,45165.5 ,532.6,501.7,470.8
XS GIS Cut Line= 3
     1847137.237      345341.506     1847153.243      345791.965
     1846693.638      346363.613
#Sta/Elev= 30
       0 1344.77    19.6 1327.35    29.4 1321.27    58.8 1309.51   137.2 1238.23
     147 1231.19   156.8 1230.91     196 1201.31   235.2 1174.79     245 1174.04
   313.6 1133.41   333.2 1123.04   352.8 1117.99   401.8 1090.81   460.7  1076.5
   609.3 1070.85   668.8 1073.23   697.1 1067.17   718.4 1064.09   732.1 1065.36
     758 1072.26   827.4 1074.46     867 1090.12   896.8 1099.28   906.7 1099.44
  1005.8 1125.48  1025.6 1127.03  1134.7 1154.63  1154.5 1155.98  1184.2 1162.74
#Mann= 3 , 0 , 0
       0     .06       0   697.1    .045       0   732.1     .06       0
Bank Sta=697.1,732.1
XS Rating Curve= 0 ,0
Exp/Cntr=0.3,0.1

Type RM Length L Ch R = 1 ,44663.8 ,407.4,394.6,381.8
XS GIS Cut Line= 3
     1846526.716      345250.042     1846764.522      346102.941
     1846597.775      346529.862
#Sta/Elev= 30
       0  1317.9      10 1312.83    19.9 1312.46    49.7 1295.71   109.4 1269.88
   129.3 1270.41   139.3 1266.58   159.2 1251.74     189 1225.43   218.9 1203.26
   228.8 1197.53   238.8 1196.29   318.4  1114.2   328.3 1113.43   348.2  1096.2
   368.1 1085.32   443.6 1065.14   467.6 1063.63   478.6 1063.76   517.3 1071.56
   646.7 1070.47   855.6 1075.86   915.3 1093.61   935.2 1096.24    1015 1119.82
  1034.9 1122.35  1114.6 1146.35  1134.5 1148.94  1204.3 1171.29  1343.8 1179.12
#Mann= 3 , 0 , 0
       0     .06       0   443.6    .045       0   478.6     .06       0
Bank Sta=443.6,478.6
XS Rating Curve= 0 ,0
Exp/Cntr=0.3,0.1

Type RM Length L Ch R = 1 ,44269.2 ,263.9,258.6,253.4
XS GIS Cut Line= 3
     1846000.728      345498.507     1846529.003      346166.966
     1846530.179      346558.082
#Sta/Elev= 30
       0 1405.14    49.5 1366.58    69.4 1356.41    89.2 1344.05   178.3 1279.33
   277.4 1216.03   336.8 1173.08   396.3    1136   435.9 1102.88   445.8 1090.91
   455.7 1081.79   465.6 1076.47   475.5 1075.35   485.4  1071.9   508.7 1059.68
   515.2 1057.19   525.1 1056.22   543.7 1056.88   594.4 1064.78   792.6 1066.88
   871.6 1070.37   881.3  1072.3   900.9 1079.68   920.4 1083.72   998.7  1119.8
  1018.2 1124.23  1096.4 1157.18  1125.8 1163.53  1174.7 1169.19  1243.1 1172.82
#Mann= 3 , 0 , 0
       0     .06       0   508.7    .045       0   543.7     .06       0
Bank Sta=508.7,543.7
XS Rating Curve= 0 ,0
Exp/Cntr=0.3,0.1

Type RM Length L Ch R = 1 ,44010.5 ,367.1,365.1,363.1
XS GIS Cut Line= 3
     1845763.541        345742.5     1846364.368      346297.302
     1846469.075      346606.023
#Sta/Elev= 30
       0 1274.26    59.8 1270.22    79.8 1271.89   109.7 1268.44   129.6 1271.82
   169.5 1263.61   199.5 1239.16   239.4 1211.48   259.3 1198.85   279.2 1192.37
   319.1 1164.74     389 1122.92   398.9  1113.9   408.9 1107.55   428.8  1099.1
   458.8 1080.47   488.7 1067.72   508.6 1053.63   521.2 1051.61   538.6 1051.49
   556.2 1054.05   588.4 1061.28   618.3 1063.66   807.8 1067.46   837.6 1076.98
   936.3 1134.24   946.2 1135.18   975.9 1151.73  1084.5 1155.48  1143.8 1165.12
#Mann= 3 , 0 , 0
       0     .06       0   521.2    .045       0   556.2     .06       0
Bank Sta=521.2,556.2
XS Rating Curve= 0 ,0
Exp/Cntr=0.3,0.1

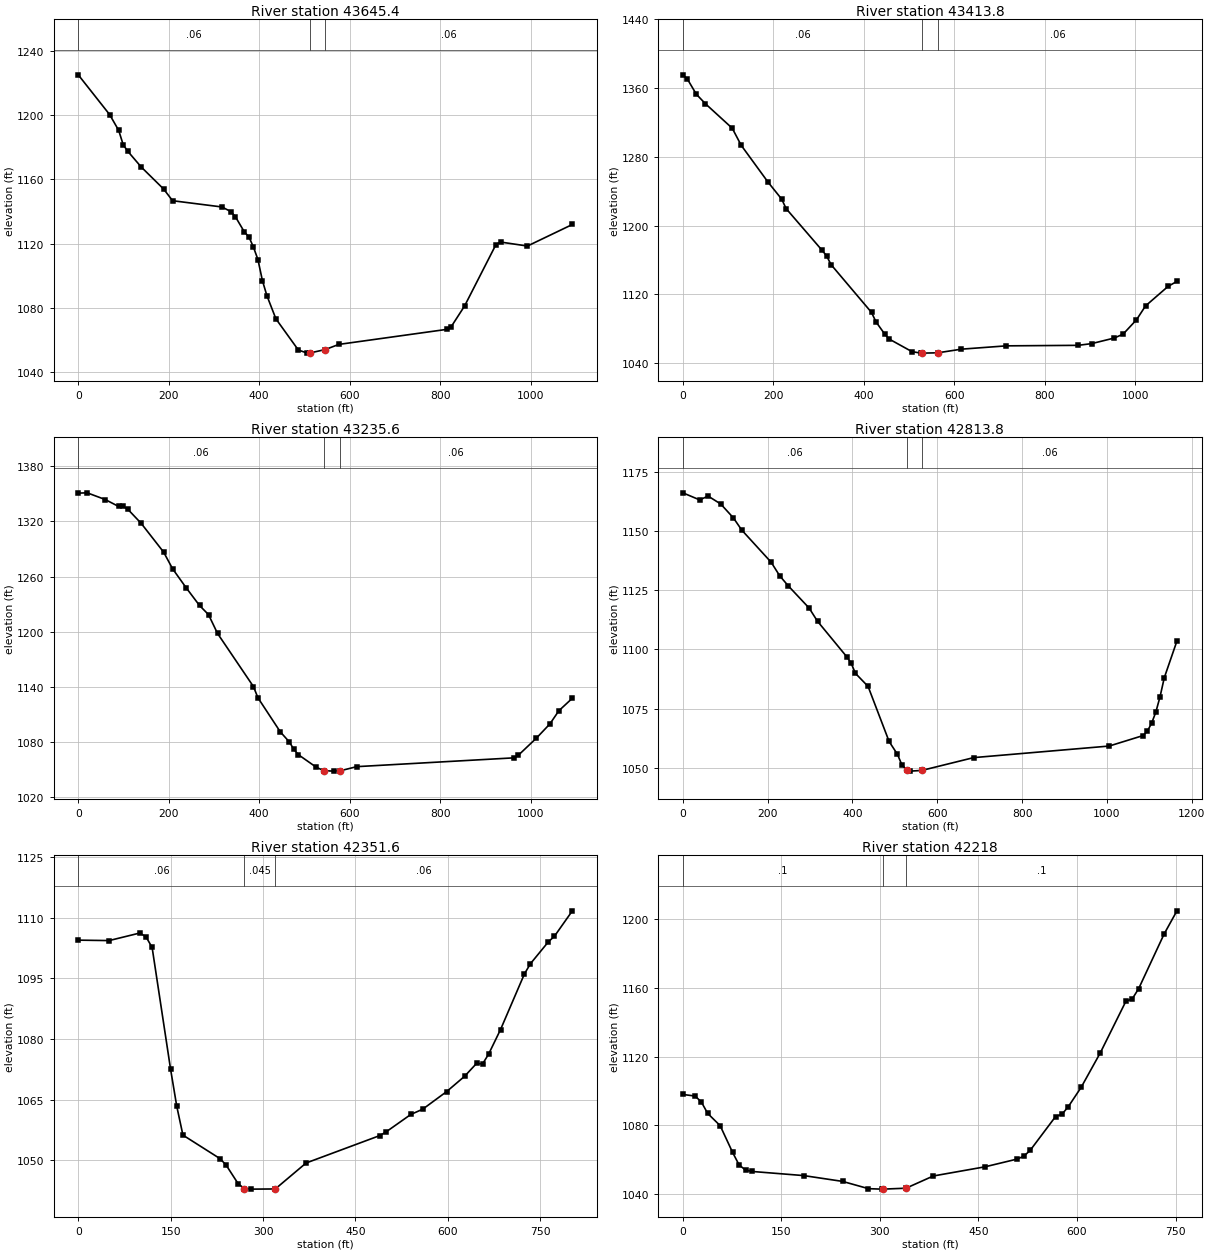
Type RM Length L Ch R = 1 ,43645.4 ,232.6,231.6,230.6
XS GIS Cut Line= 3
     1845521.118      346058.406     1845944.202      346403.537
     1846367.287      346748.668
#Sta/Elev= 30
       0 1225.31    69.5 1200.44    89.4 1190.61    99.3 1181.71   109.2 1177.68
     139 1167.82   188.6 1154.04   208.5 1146.73   317.7 1142.82   337.5  1139.9
   347.4 1136.68   367.3 1127.16   377.2 1124.15   387.2 1117.74   397.1    1110
     407 1096.86     417  1087.4   436.8 1073.01   486.4 1053.54   506.3 1051.59
   511.1 1051.63   546.1 1053.84   575.8 1057.03     814  1066.4     824 1067.98
   853.8 1081.02   923.2 1119.39   933.2 1120.93   992.7 1118.44    1092 1131.89
#Mann= 3 , 0 , 0
       0     .06       0   511.1    .045       0   546.1     .06       0
Bank Sta=511.1,546.1
XS Rating Curve= 0 ,0
Exp/Cntr=0.3,0.1

Type RM Length L Ch R = 1 ,43413.8 ,180.4,178.2,175.9
XS GIS Cut Line= 3
     1845358.055       346245.65      1845791.59      346577.558
     1846225.125      346909.466
#Sta/Elev= 30
       0 1375.52     9.9 1370.72    29.8 1352.95    49.6 1342.02   109.2 1313.36
     129 1293.47   188.6 1250.41   218.4 1230.89   228.3 1219.78   307.8 1171.24
   317.7 1164.78   327.6 1154.58     417 1098.95   426.9 1087.97   446.7 1073.37
   456.6 1067.82   506.3 1053.36   526.2  1051.6   528.5  1051.6   563.5 1051.97
   615.5  1056.2   714.8 1060.07   873.6 1060.67   903.4 1062.66     953 1069.11
   972.9 1073.65  1002.6 1090.41  1022.5 1106.52  1072.2  1129.2    1092 1135.16
#Mann= 3 , 0 , 0
       0     .06       0   528.5    .045       0   563.5     .06       0
Bank Sta=528.5,563.5
XS Rating Curve= 0 ,0
Exp/Cntr=0.3,0.1

Type RM Length L Ch R = 1 ,43235.6 ,424.6,421.8,419.9
XS GIS Cut Line= 3
     1845215.807      346409.765     1845671.164      346711.039
     1846126.521      347012.313
#Sta/Elev= 30
       0 1350.74    19.8 1351.06    59.6 1343.76    89.4  1336.2    99.3 1336.28
   109.2 1333.37     139  1317.9   188.6 1286.64   208.5 1268.47   238.2    1248
     268 1228.55   287.9  1218.6   307.8 1198.15   387.2 1140.34   397.1 1128.16
   446.7 1091.01   466.6  1080.1   476.5 1072.02   486.4 1066.31   526.2 1052.57
   543.3 1048.81   565.8  1048.4   578.3 1048.69   615.5 1053.27     963 1062.85
   972.9 1065.81  1012.6 1084.33  1042.4 1099.78  1062.2 1114.09    1092  1127.7
#Mann= 3 , 0 , 0
       0     .06       0   543.3    .045       0   578.3     .06       0
Bank Sta=543.3,578.3
XS Rating Curve= 0 ,0
Exp/Cntr=0.3,0.1

Type RM Length L Ch R = 1 ,42813.8 ,457.4,462.1,465.9
XS GIS Cut Line= 3
     1844971.545      346809.986     1845450.999      347071.104
      1845987.08      347381.147
#Sta/Elev= 30
       0 1166.33    39.7 1163.34    59.6 1164.95    89.3 1161.61   119.1 1155.75
     139 1150.55   208.4 1136.91   228.3 1131.23   248.2 1127.02   297.8 1117.54
   317.6 1111.94   387.1 1096.79     397 1094.16     407 1089.89   436.8 1084.37
   486.4 1061.05   506.2 1055.57   516.2 1051.29   528.4  1048.8     536 1048.49
   563.4 1048.78   685.8 1054.21  1005.4 1059.11  1085.3 1063.55  1095.3  1065.4
  1105.3 1068.71  1115.3 1073.44  1125.3 1079.97  1135.3 1088.02  1165.2  1103.6
#Mann= 3 , 0 , 0
       0     .06       0   528.4    .045       0   563.4     .06       0
Bank Sta=528.4,563.4
XS Rating Curve= 0 ,0
Exp/Cntr=0.3,0.1

Type RM Length L Ch R = 1 ,42351.6 ,128.3,133.7,139.1
XS GIS Cut Line= 3
     1845001.559       347298.83     1845436.011      347618.953
     1845568.634      347845.326
#Sta/Elev= 30
       0 1104.48      50 1104.37    99.9 1106.24   109.9 1105.32   119.9 1102.67
   149.9 1072.52   159.9 1063.39   169.9 1056.26   229.8 1050.47   239.8  1048.9
   259.8 1044.18   269.8 1043.04   279.8  1042.9   319.8 1042.94   369.8 1049.36
   489.7 1056.16   499.7 1057.06   539.7 1061.36   559.1 1062.67     598 1067.03
   627.1 1070.81   646.5 1073.99   656.3 1073.87     666 1076.27   685.4 1082.36
   724.3 1096.16     734 1098.66   763.2 1104.09   772.9 1105.44     802 1111.73
#Mann= 3 , 0 , 0
       0     .06       0   269.8    .045       0   319.8     .06       0
Bank Sta=269.8,319.8
XS Rating Curve= 0 ,0
Exp/Cntr=0.3,0.1

Type RM Length L Ch R = 1 ,42218   ,254.1,275.6,297
XS GIS Cut Line= 4
     1845012.992      347358.281     1845027.829      347432.543
     1845323.968      347735.569     1845415.432      347971.088
#Sta/Elev= 30
       0 1097.95    18.9 1097.01    28.4 1093.42    37.9 1086.89    56.8 1079.81
    75.7 1064.29    85.6    1057    95.4 1053.98   105.3 1053.18   184.1 1050.77
   243.2 1047.39   282.6 1043.16   302.4  1042.9   304.7  1042.9   339.7 1043.44
   381.2 1050.54     460 1055.88   509.2 1060.41   518.9 1062.03   528.6 1065.39
   567.4 1085.13   577.2 1086.47   586.9 1090.94   606.3  1102.1   635.5 1122.21
   674.4 1152.16   684.1 1153.55   693.8 1159.47   732.6 1191.28   752.1 1204.73
#Mann= 3 , 0 , 0
       0      .1       0   304.7    .045       0   339.7      .1       0
Bank Sta=304.7,339.7
XS Rating Curve= 0 ,0
Exp/Cntr=0.3,0.1