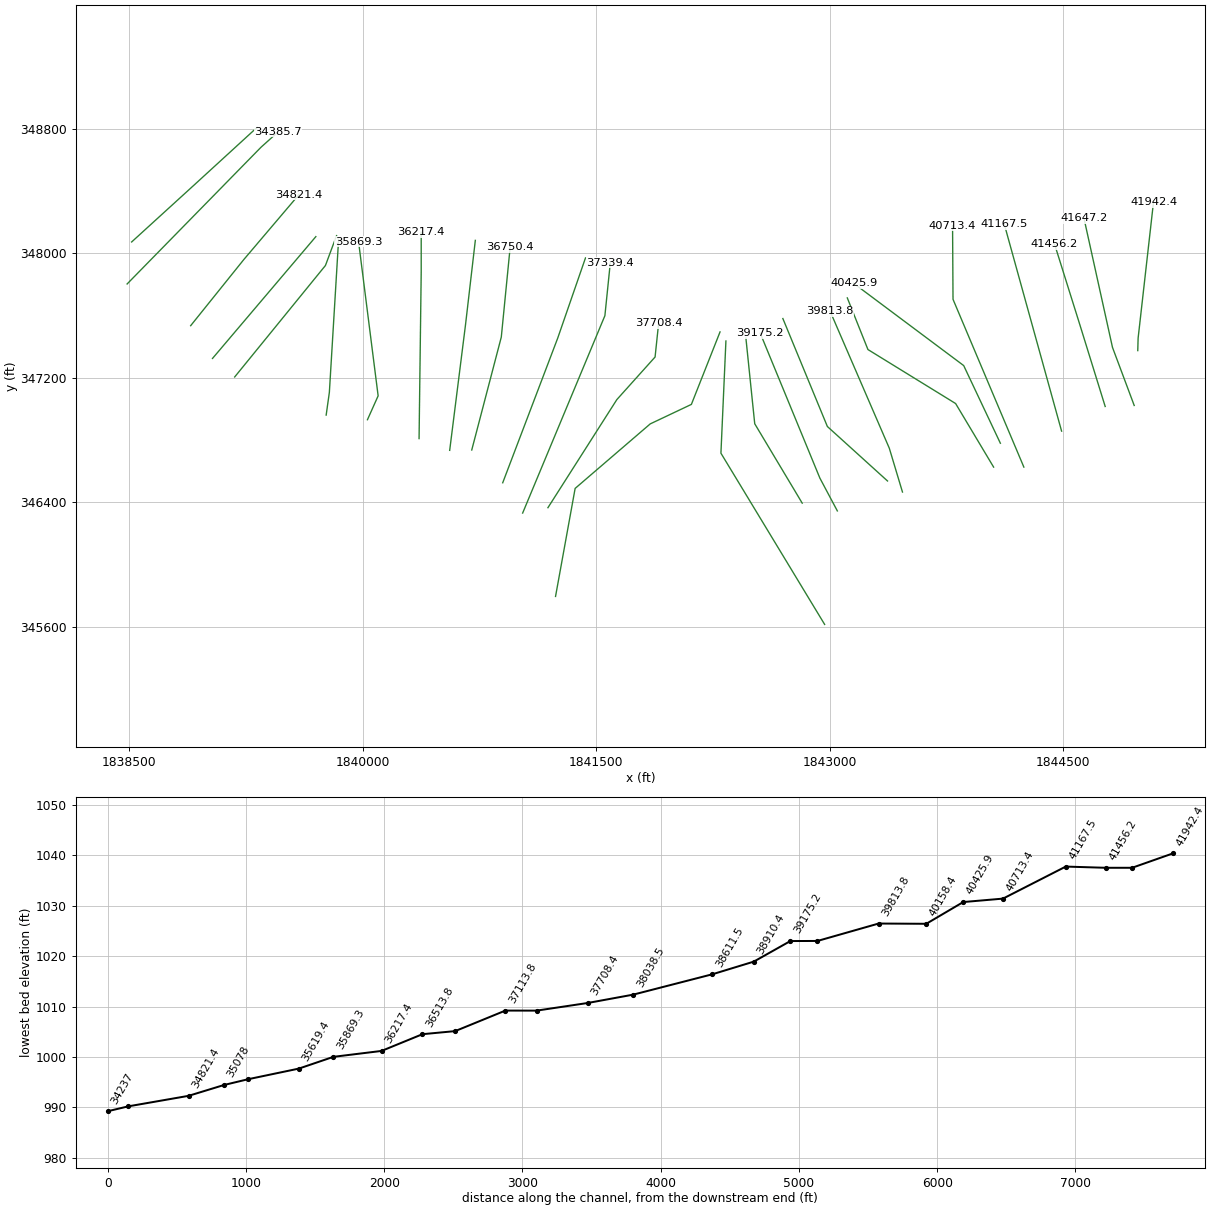
HEC-RAS study ClrFrk1.prj: ClrFrk1

--- ClrFrk1.g01 (geometry) --- (continued)

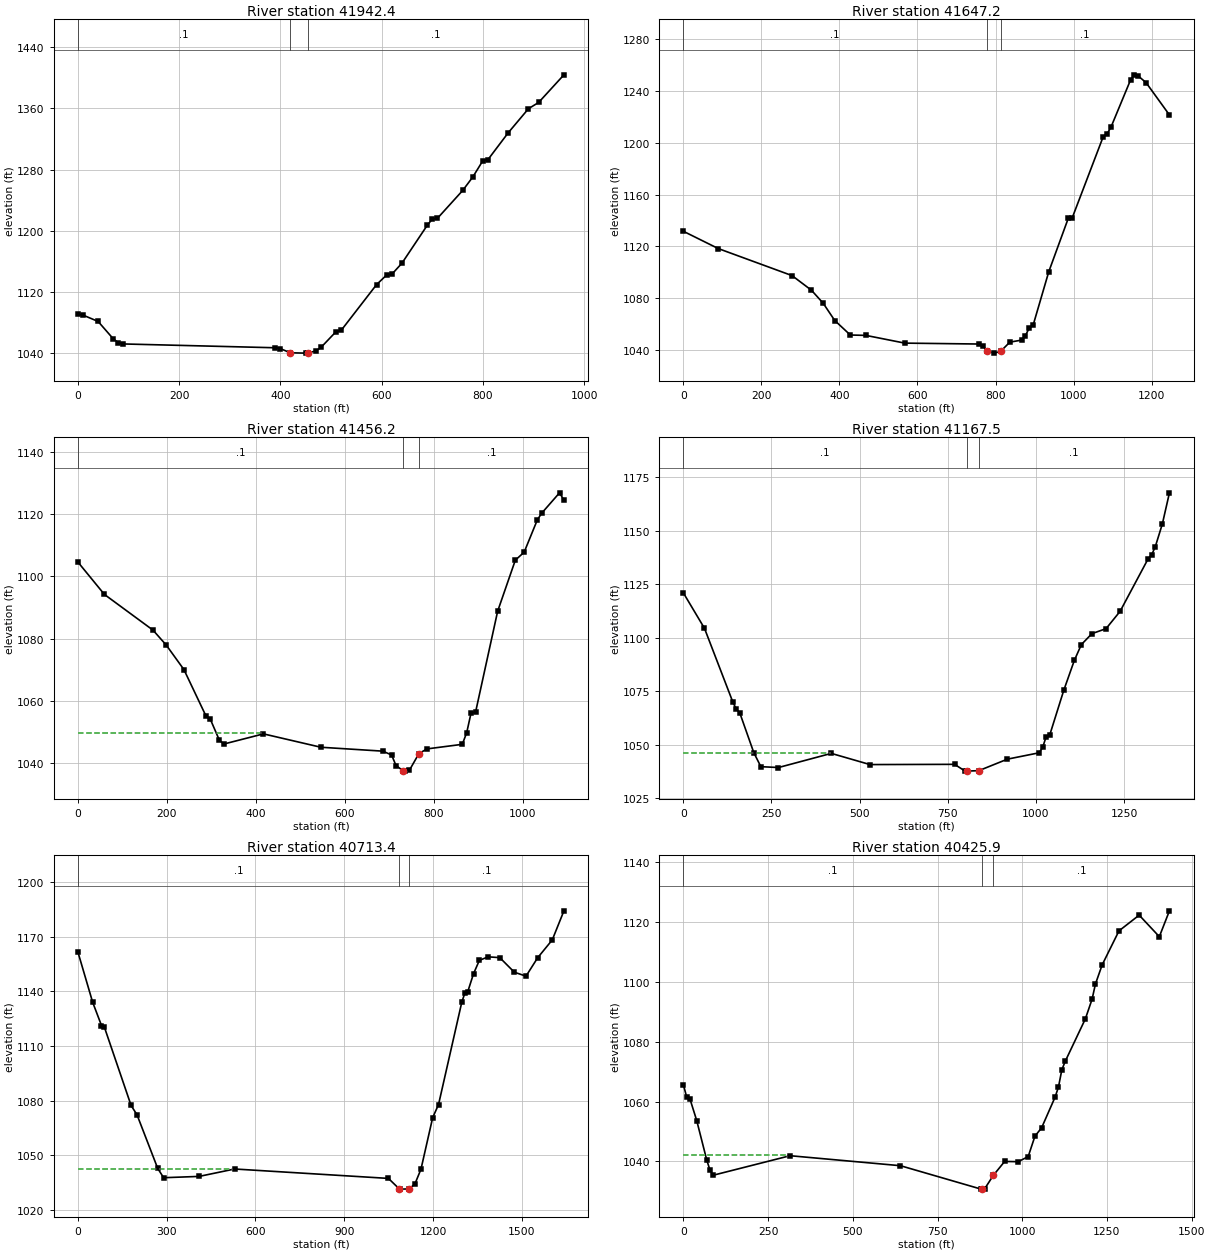
Type RM Length L Ch R = 1 ,41942.4 ,284.4,295.2,306
XS GIS Cut Line= 3
     1844978.693      347374.287     1844980.979      347454.318
     1845079.926      348328.608
#Sta/Elev= 30
       0 1091.04      10 1090.07      40 1081.72    70.1 1058.91    80.1 1053.94
    90.1 1052.33     390 1047.35     400 1046.23   419.5 1040.79     450 1040.35
   454.5 1040.54     470 1043.26     480 1047.71     510  1068.5     520 1070.05
     590 1129.91     610 1142.51     620 1143.28     640 1157.78     690 1207.27
     700 1215.52     710 1216.32     760 1252.77     780 1270.43     800 1291.83
     810 1293.16     850  1328.2   889.9 1359.57   909.9 1367.66   959.9 1403.78
#Mann= 3 , 0 , 0
       0      .1       0   419.5    .045       0   454.5      .1       0
Bank Sta=419.5,454.5
XS Rating Curve= 0 ,0
Exp/Cntr=0.3,0.1

Type RM Length L Ch R = 1 ,41647.2 ,188.2,191,193.8
XS GIS Cut Line= 3
     1844955.827      347022.152     1844816.345      347394.867
     1844633.417      348222.614
#Sta/Elev= 30
       0 1131.63    89.5 1118.27   278.6 1097.38   328.3 1086.08   358.2 1076.11
     388  1062.7   427.9  1051.5   467.8  1051.2   567.5 1045.23     757 1044.53
     767 1043.21   777.9 1039.52   796.9  1037.5   812.9 1038.81   836.8 1046.01
   866.7 1047.54   876.7 1051.02   886.6 1057.08   896.6  1059.3   936.5 1100.42
   986.4 1141.61   996.4 1141.84  1076.1 1204.79  1086.1 1206.96  1096.1 1212.21
    1146  1248.5  1155.9 1252.48  1165.9 1251.54  1185.8 1246.47  1245.7 1221.49
#Mann= 3 , 0 , 0
       0      .1       0   777.9    .045       0   812.9      .1       0
Bank Sta=777.9,812.9
XS Rating Curve= 0 ,0
Exp/Cntr=0.3,0.1

Type RM Length L Ch R = 1 ,41456.2 ,289.9,288.8,287.7
XS GIS Cut Line= 3
      1844769.43      347015.613     1844607.665      347537.104
     1844444.171       348058.05
#Sta/Elev= 30
       0  1104.6    59.6  1094.2   168.8 1082.74   198.6 1077.94   238.3 1070.08
   287.9 1055.17   297.8 1054.09   317.7  1047.5   327.6 1046.18     417 1049.45
     546 1045.16     685 1043.91   704.8 1042.69   714.8 1039.28   731.3 1037.57
   734.6  1037.5   744.6 1037.72   766.3 1043.14   784.3 1044.63   863.7  1046.1
   873.6 1049.85   883.5 1056.25   893.5 1056.43   943.1  1088.8   982.8 1105.18
  1002.7 1107.76  1032.4 1118.17  1042.4 1120.31  1082.1 1126.79    1092 1124.47
#Mann= 3 , 0 , 0
       0      .1       0   731.3    .045       0   766.3      .1       0
#XS Ineff= 2 , 0
          416.14 1049.82
Permanent Ineff=
       F       F
Bank Sta=731.3,766.3
XS Rating Curve= 0 ,0
Exp/Cntr=0.3,0.1

Type RM Length L Ch R = 1 ,41167.5 ,449.4,454.1,458.8
XS GIS Cut Line= 2
     1844489.362      346857.517      1844121.22      348186.028
#Sta/Elev= 30
       0 1120.96    59.9 1104.42   139.9 1070.18   149.8 1066.75   159.8 1065.04
   199.8 1046.37   219.8 1039.82   269.7 1039.42   419.6 1046.02   529.4  1040.8
   769.2 1040.91   799.2 1037.74   803.2 1037.74   838.2 1037.97     919 1043.33
    1009  1046.3    1019 1048.78  1028.9  1053.8  1038.9 1054.49  1078.9 1075.46
  1108.8  1089.4  1128.8 1096.82  1158.8 1101.93  1198.8 1104.25  1238.7 1112.35
  1318.6    1137  1328.6 1138.85  1338.6 1142.57  1358.6 1153.21  1378.6 1167.67
#Mann= 3 , 0 , 0
       0      .1       0   803.2    .045       0   838.2      .1       0
#XS Ineff= 2 , 0
          419.45 1046.02
Permanent Ineff=
       F       F
Bank Sta=803.2,838.2
XS Rating Curve= 0 ,0
Exp/Cntr=0.3,0.1

Type RM Length L Ch R = 1 ,40713.4 ,270.4,287.5,304.6
XS GIS Cut Line= 3
     1844246.983      346626.571     1843791.951      347703.557
      1843789.04      348176.521
#Sta/Elev= 30
       0  1161.8      50 1134.08    79.9 1121.29    89.9 1120.27   179.9 1077.35
   199.9 1072.22   269.8 1042.79   289.8 1037.66   409.7 1038.38   529.6 1042.45
  1049.2 1037.28  1085.1 1031.64  1089.2 1031.39  1120.1  1031.5  1139.2 1034.43
  1159.2 1042.37  1198.7 1070.68  1218.4 1077.81  1297.3 1134.28  1307.1 1138.92
    1317 1139.76  1336.7 1149.74  1356.4 1157.08    1386 1159.02  1425.4 1158.58
  1474.6 1150.57    1514 1148.41  1553.5 1158.54  1602.7 1168.32  1642.1  1184.3
#Mann= 3 , 0 , 0
       0      .1       0  1085.1    .045       0  1120.1      .1       0
#XS Ineff= 2 , 0
          519.79 1042.36
Permanent Ineff=
       F       F
Bank Sta=1085.1,1120.1
XS Rating Curve= 0 ,0
Exp/Cntr=0.3,0.1

Type RM Length L Ch R = 1 ,40425.9 ,264.4,267.3,270.2
XS GIS Cut Line= 3
     1844096.068      346779.773     1843860.548       347278.25
     1843153.082      347806.705
#Sta/Elev= 30
       0 1065.63     9.8  1061.5    19.7 1060.78    39.4 1053.65    68.9  1040.5
    78.8 1036.97    88.6 1035.37     315 1041.88   640.6 1038.54   878.7 1030.71
   879.9 1030.71   888.7 1030.74   914.9 1035.34   948.2 1039.97   987.9 1039.88
  1017.6 1041.59  1037.5  1048.4  1057.3 1051.23    1097 1061.47  1106.9 1064.83
  1116.9  1070.6  1126.8 1073.41  1186.3 1087.62  1206.2 1094.23  1216.1 1099.29
  1235.9 1105.68  1285.5 1117.04  1345.1  1122.3  1404.6  1115.1  1434.4 1123.74
#Mann= 3 , 0 , 0
       0      .1       0   879.9    .045       0   914.9      .1       0
#XS Ineff= 2 , 0
          305.48 1041.96
Permanent Ineff=
       F       F
Bank Sta=879.9,914.9
XS Rating Curve= 0 ,0
Exp/Cntr=0.3,0.1

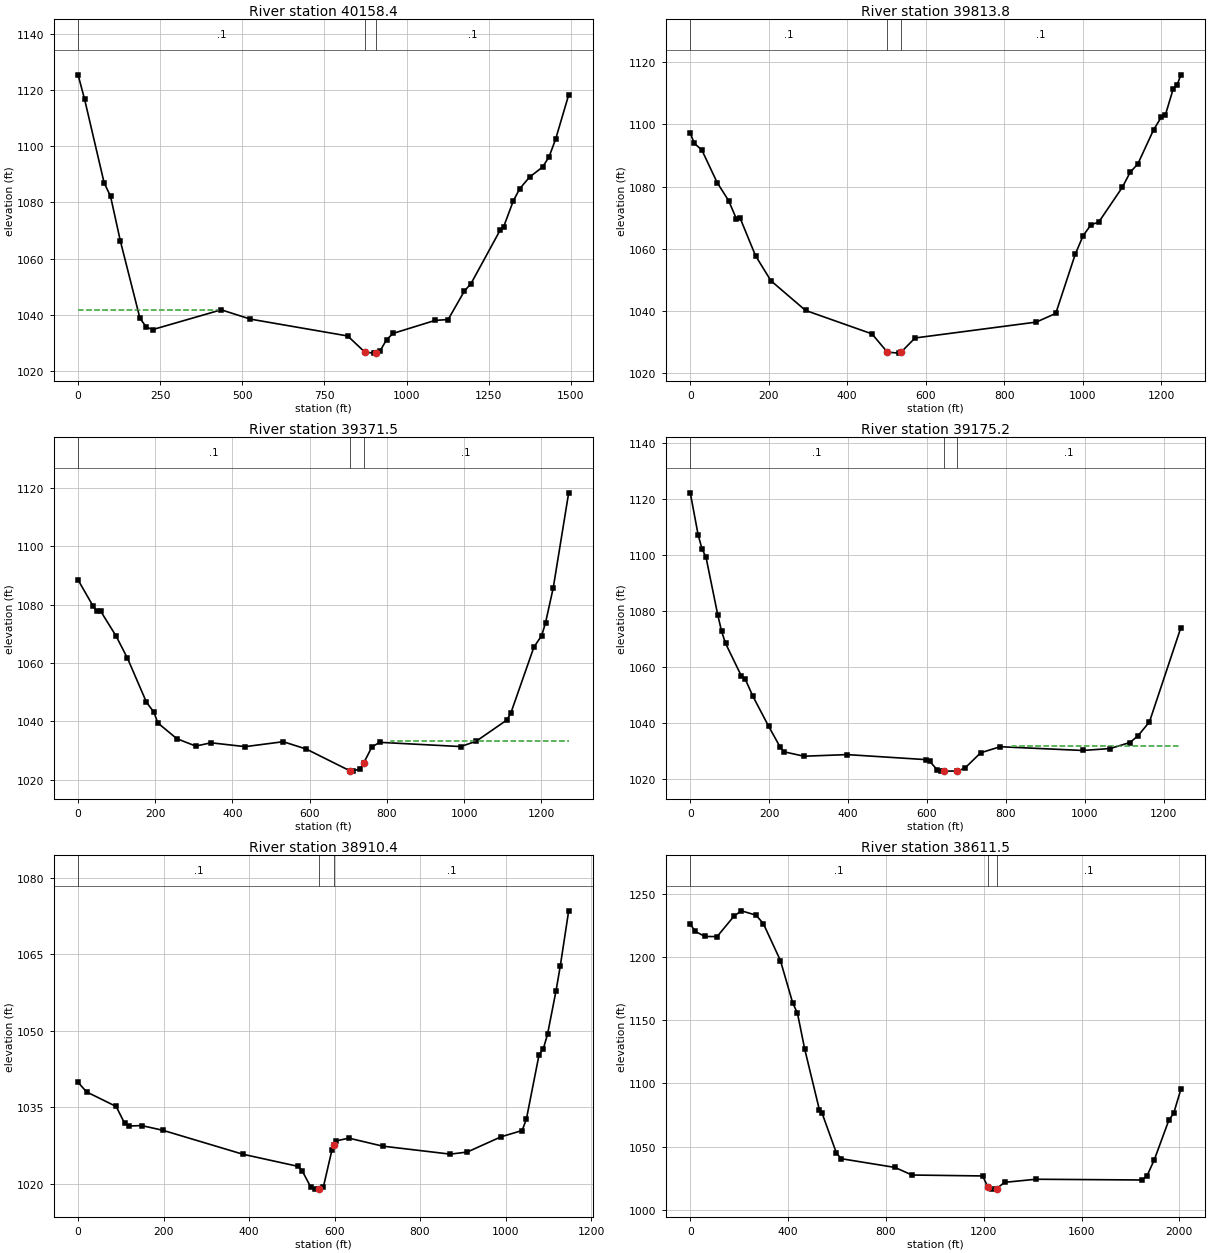
Type RM Length L Ch R = 1 ,40158.4 ,365.1,344.7,324.4
XS GIS Cut Line= 4
     1844052.622      346626.571     1843808.589      347034.612
     1843245.455      347381.147     1843112.832      347712.703
#Sta/Elev= 30
       0 1125.36    19.8 1116.68    79.2 1087.01      99  1082.1   128.8 1066.25
   188.2 1038.86     208 1035.61   227.8 1034.79   435.8  1041.8   524.8 1038.49
   820.9  1032.5   872.8 1026.79   899.8  1026.4   907.8 1026.43   919.6  1027.2
   939.3 1031.18     959 1033.41  1087.3 1038.04  1126.8 1038.34  1176.3 1048.48
  1196.2 1051.08  1285.4 1070.18  1295.4  1071.2  1325.1 1080.52    1345  1084.9
  1374.7 1089.01  1414.4 1092.56  1434.2 1096.24  1454.1 1102.51  1493.8 1118.23
#Mann= 3 , 0 , 0
       0      .1       0   872.8    .045       0   907.8      .1       0
#XS Ineff= 2 , 0
          430.12  1041.8
Permanent Ineff=
       F       F
Bank Sta=872.8,907.8
XS Rating Curve= 0 ,0
Exp/Cntr=0.3,0.1

Type RM Length L Ch R = 1 ,39813.8 ,448,442.3,441.7
XS GIS Cut Line= 3
     1843467.254       346466.51      1843382.65      346747.761
     1843002.897      347625.992
#Sta/Elev= 30
       0 1097.28     9.8 1093.97    29.4 1091.78    68.5 1081.31    97.9 1075.45
   117.5 1069.64   127.3 1069.79   166.4 1057.76   205.6 1049.72   293.7 1040.19
   463.1 1032.64   502.3 1026.76   532.9 1026.45   537.3 1026.75   572.8 1031.32
   881.8 1036.43   931.6 1039.22   981.4 1058.31  1001.4 1064.23  1021.3 1067.72
  1041.2  1068.6    1101 1079.73    1121 1084.55  1140.9 1087.33  1180.8 1098.23
  1200.7 1102.38  1210.6 1102.88  1230.6 1111.28  1240.6 1112.61  1250.5 1115.95
#Mann= 3 , 0 , 0
       0      .1       0   502.3    .045       0   537.3      .1       0
Bank Sta=502.3,537.3
XS Rating Curve= 0 ,0
Exp/Cntr=0.3,0.1

Type RM Length L Ch R = 1 ,39371.5 ,191,196.3,196.9
XS GIS Cut Line= 3
     1843371.217      346537.394     1842984.783      346887.243
     1842698.959      347580.081
#Sta/Elev= 30
       0 1088.45    39.3 1079.39    49.2 1077.67      59 1077.66    98.4 1069.25
   127.9 1061.67     177 1046.63   196.7  1043.1   206.5  1039.5   255.7 1034.11
   304.9 1031.57   344.2  1032.7   432.8 1031.38   531.3 1033.07   591.2 1030.55
     705 1023.05   711.1    1023   731.1  1023.8     740 1025.83   761.1 1031.27
   781.1 1032.86     991 1031.41  1030.9 1033.21  1110.9 1040.52  1120.9 1042.86
  1180.8 1065.48  1200.8 1069.37  1210.8 1073.79  1230.8 1085.74  1270.8 1118.27
#Mann= 3 , 0 , 0
       0      .1       0     705    .045       0     740      .1       0
#XS Ineff= 2 , 0
                          811.03         1033.43
Permanent Ineff=
       F       F
Bank Sta=705,740
XS Rating Curve= 0 ,0
Exp/Cntr=0.3,0.1

Type RM Length L Ch R = 1 ,39175.2 ,260.2,264.8,258
XS GIS Cut Line= 3
     1843048.808       346345.32     1842936.765      346555.687
     1842553.887      347485.335
#Sta/Elev= 30
       0  1122.3    19.9 1107.32    29.8 1102.26    39.7 1099.44    69.5 1078.84
    79.4 1072.87    89.4 1068.58   129.1 1057.06     139 1055.92   158.9 1049.65
   198.6 1039.01   228.4 1031.42   238.3 1029.86   288.1  1028.3   397.6 1028.88
   596.7 1027.09   606.7 1026.56   626.6 1023.33   636.5 1022.98   642.1 1022.99
   677.1 1023.01   696.2 1024.04   736.1 1029.52   785.8 1031.69   994.9 1030.35
  1064.6 1031.04  1114.3 1033.19  1134.2 1035.44  1164.1 1040.55  1243.8 1074.22
#Mann= 3 , 0 , 0
       0      .1       0   642.1    .045       0   677.1      .1       0
#XS Ineff= 2 , 0
                          815.95         1031.77
Permanent Ineff=
       F       F
Bank Sta=642.1,677.1
XS Rating Curve= 0 ,0
Exp/Cntr=0.3,0.1

Type RM Length L Ch R = 1 ,38910.4 ,298.8,298.9,310.1
XS GIS Cut Line= 3
     1842823.283      346395.084     1842518.234      346904.654
      1842461.39      347455.627
#Sta/Elev= 30
       0 1039.87    19.8 1037.99    89.1 1035.13   108.9 1031.82   118.8 1031.28
   148.5 1031.38     198 1030.46     386 1025.74   514.7 1023.37   524.6 1022.45
   544.4  1019.3   554.3  1018.9   564.5 1018.92   574.1  1019.4   593.9 1026.58
   599.5 1027.59   603.8 1028.37   633.5 1028.91   712.6 1027.34   870.8 1025.77
   910.4 1026.18   989.5 1029.17    1039 1030.41  1048.9 1032.67  1078.6 1045.33
  1088.4 1046.44  1098.3  1049.3  1118.1  1057.8    1128 1062.63  1147.8 1073.54
#Mann= 3 , 0 , 0
       0      .1       0   564.5    .045       0   599.5      .1       0
#XS Ineff= 2 , 0
                          633.56          1028.9
Permanent Ineff=
       F       F
Bank Sta=564.5,599.5
XS Rating Curve= 0 ,0
Exp/Cntr=0.3,0.1

Type RM Length L Ch R = 1 ,38611.5 ,629.6,572.9,515
XS GIS Cut Line= 3
     1842967.204       345616.67     1842301.092      346715.748
     1842333.104      347436.025
#Sta/Elev= 30
       0 1225.94    19.9 1220.18    59.8 1216.14   109.6 1216.03   179.3 1232.33
   209.2 1236.41     269 1232.97   298.9 1226.29   368.6  1197.1   418.4 1163.91
   438.4 1155.32   468.2 1126.86     528  1079.1     538 1076.93   597.8 1044.83
   617.7 1040.44   836.9 1033.56   906.6 1027.55  1195.5 1026.82  1217.5 1017.92
  1235.4  1016.4  1252.5 1016.78  1285.2 1021.76  1413.6 1024.21  1848.1 1023.63
  1867.9 1027.03  1897.5 1039.61  1956.8 1070.84  1976.5 1076.24  2006.2 1095.36
#Mann= 3 , 0 , 0
       0      .1       0  1217.5    .045       0  1252.5      .1       0
Bank Sta=1217.5,1252.5
XS Rating Curve= 0 ,0
Exp/Cntr=0.3,0.1

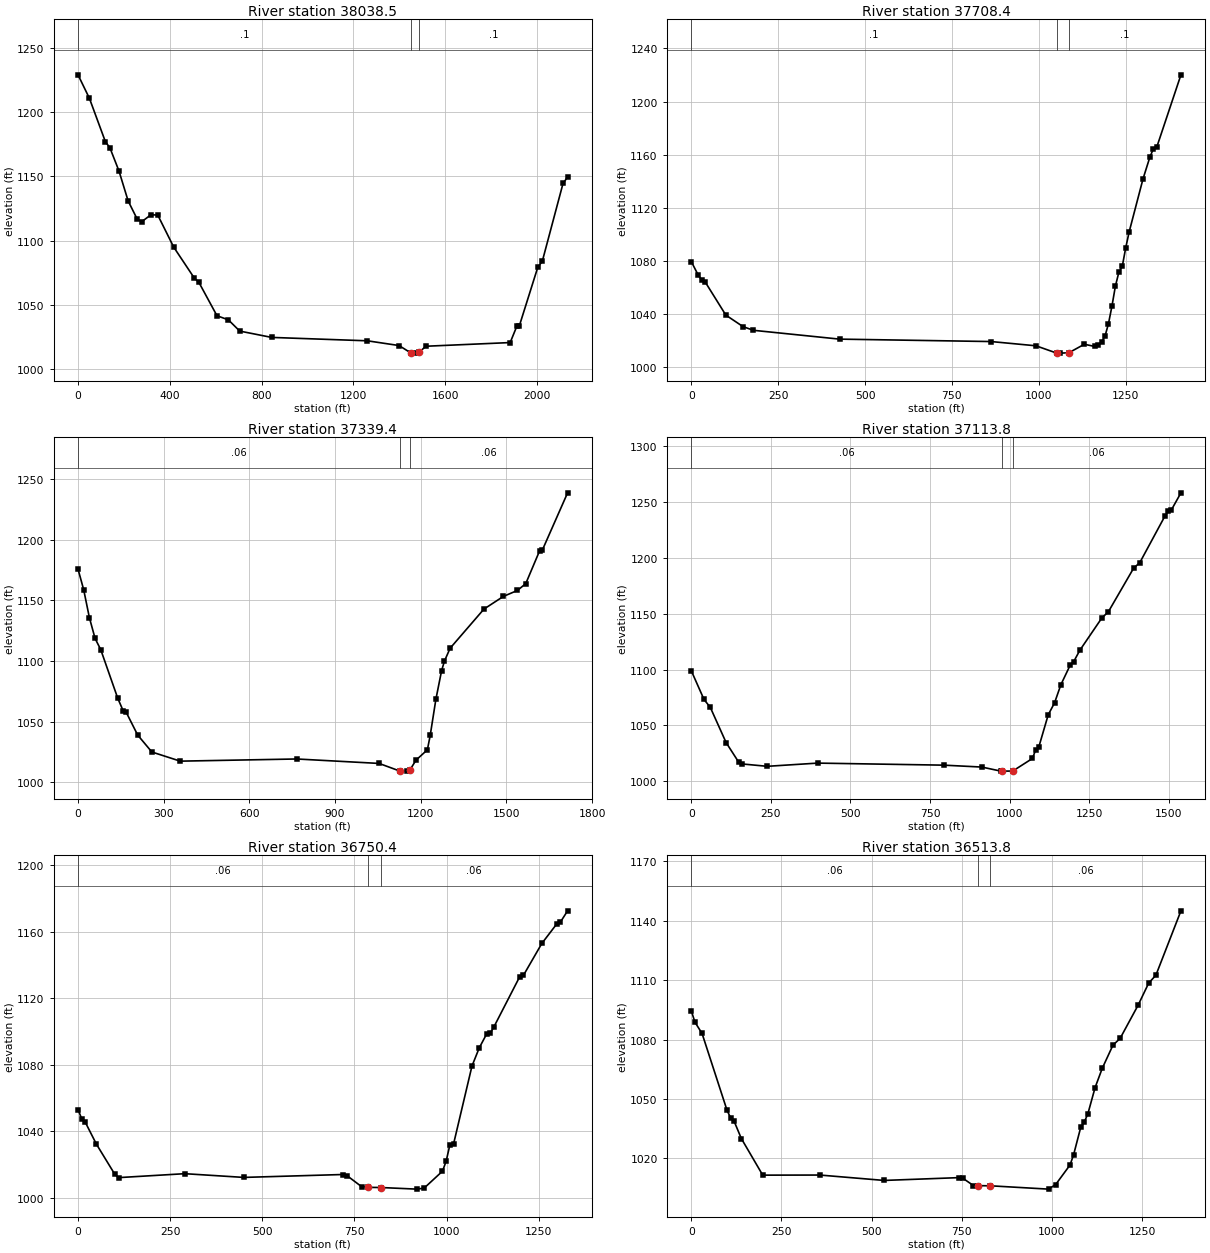
Type RM Length L Ch R = 1 ,38038.5 ,317.2,330.1,343.1
XS GIS Cut Line= 5
     1841238.668      345796.258     1841364.595      346489.759
     1841846.861      346903.844     1842111.305      347029.012
     1842295.396      347494.352
#Sta/Elev= 30
       0 1228.94    49.6 1210.68   119.1 1176.98     139 1172.13   178.7    1154
   218.4  1130.8   258.1 1116.55     278 1114.69   317.7 1120.02   347.5 1119.81
     417 1094.87   506.3 1070.88   526.2  1067.6   605.6 1041.45   655.2 1038.26
   704.8 1029.51   843.9 1024.59    1261 1021.95    1399 1018.26  1450.9 1012.46
  1467.3 1012.36  1485.9 1012.96    1516 1017.72  1883.3 1020.58  1913.3 1033.74
  1923.3 1033.63  2003.4 1079.07  2023.4 1083.94  2113.5 1144.37  2133.5 1149.42
#Mann= 3 , 0 , 0
       0      .1       0  1450.9    .045       0  1485.9      .1       0
Bank Sta=1450.9,1485.9
XS Rating Curve= 0 ,0
Exp/Cntr=0.3,0.1

Type RM Length L Ch R = 1 ,37708.4 ,358.1,369,380
XS GIS Cut Line= 4
     1841189.807        346365.9     1841632.458      347059.821
     1841878.072      347333.129     1841900.938      347550.355
#Sta/Elev= 30
       0 1079.52    19.8 1069.39    29.8 1065.86    39.7  1064.3    99.2 1039.32
   148.8 1030.64   178.5 1027.88   426.4 1021.24   862.8 1019.41   991.9 1016.21
  1051.4 1010.72  1061.4  1010.7  1086.4 1010.97    1131 1017.38  1160.8 1015.73
  1170.7 1016.48  1180.6 1019.07  1190.5  1023.5  1200.5 1032.94  1210.4    1046
  1220.3 1061.02  1230.2 1071.46  1240.2 1076.09  1250.1 1089.99    1260 1101.98
  1299.8 1141.79  1319.6 1158.22  1329.5 1164.38  1339.5  1165.8    1409 1220.16
#Mann= 3 , 0 , 0
       0      .1       0  1051.4    .045       0  1086.4      .1       0
Bank Sta=1051.4,1086.4
XS Rating Curve= 0 ,0
Exp/Cntr=0.3,0.1

Type RM Length L Ch R = 1 ,37339.4 ,224.5,225.6,227.6
XS GIS Cut Line= 3
     1841027.459      346331.601     1841555.662      347598.374
     1841590.517       347938.44
#Sta/Elev= 30
       0 1175.64    19.9 1158.61    39.8 1135.67    59.7 1118.54    79.6 1109.26
   139.2 1069.18   159.1 1058.36   169.1  1057.5   208.9 1038.91   258.6 1024.95
     358 1017.41   765.8  1019.2  1054.2 1015.53  1127.1 1009.23  1153.7 1009.19
  1162.1 1010.12  1183.5 1018.24  1223.3 1026.76  1233.2 1038.61  1253.1 1068.38
    1273 1091.89    1283 1099.82  1302.9 1110.45  1421.3  1142.7  1489.7  1153.2
  1538.5 1158.04  1567.8  1163.7  1616.7 1190.96  1626.4  1191.6  1714.3 1238.51
#Mann= 3 , 0 , 0
       0     .06       0  1127.1    .045       0  1162.1     .06       0
Bank Sta=1127.1,1162.1
XS Rating Curve= 0 ,0
Exp/Cntr=0.3,0.1

Type RM Length L Ch R = 1 ,37113.8 ,354.8,363.4,371.1
XS GIS Cut Line= 3
      1840899.41      346525.961     1841252.253      347453.391
     1841431.044      347969.288
#Sta/Elev= 30
       0 1098.79    39.7 1073.27    59.5 1066.19   109.2 1034.73   148.8 1017.17
   158.8 1015.64   238.2  1013.5   396.9 1016.37   793.8 1014.53   912.9 1012.83
   972.4  1009.2   974.8  1009.2  1009.8 1009.27  1071.7 1020.52  1081.6 1027.99
  1091.6 1030.66  1121.3 1059.57  1141.2 1070.22    1161 1086.41  1190.8 1104.21
  1200.8 1106.77  1220.6  1117.2  1290.1 1146.23    1310  1151.5  1389.4 1190.48
  1409.2 1195.65  1488.6 1237.48  1498.6 1241.59  1508.5 1242.78  1538.3 1257.95
#Mann= 3 , 0 , 0
       0     .06       0   974.8    .045       0  1009.8     .06       0
Bank Sta=974.8,1009.8
XS Rating Curve= 0 ,0
Exp/Cntr=0.3,0.1

Type RM Length L Ch R = 1 ,36750.4 ,237.4,236.5,236
XS GIS Cut Line= 3
     1840700.476      346736.328     1840890.264      347461.178
     1840947.097      348037.286
#Sta/Elev= 30
       0 1053.02      10 1047.42      20 1045.25      50 1032.14    99.9 1014.01
   109.9 1012.05   289.7 1014.42   449.6 1012.18   719.3 1013.93   729.3 1013.32
   769.2 1006.64   786.3 1006.19   821.3  1006.1     919 1005.13   938.9 1005.72
   988.8 1015.94   998.8    1022  1008.8 1031.76  1018.8 1032.27  1068.7 1079.13
  1088.6 1090.16  1108.6  1098.5  1118.6 1099.04  1128.6 1102.87  1198.4 1132.98
  1208.4 1133.76  1258.3 1152.94  1298.2 1164.52  1308.2 1165.63  1328.2 1172.57
#Mann= 3 , 0 , 0
       0     .06       0   786.3    .045       0   821.3     .06       0
Bank Sta=786.3,821.3
XS Rating Curve= 0 ,0
Exp/Cntr=0.3,0.1

Type RM Length L Ch R = 1 ,36513.8 ,292.4,296.4,300.1
XS GIS Cut Line= 3
     1840558.708      346734.041     1840660.311      347539.671
     1840723.425      348082.025
#Sta/Elev= 30
       0 1094.45     9.9 1088.84    29.7 1083.12      99  1044.3   108.9  1040.5
   118.8 1038.71   138.6 1030.08     198 1011.58   356.5 1011.63   534.7 1008.91
   742.7 1010.33   752.6 1010.08   782.3 1006.33   794.5 1006.28   829.5  1006.2
   990.7 1004.52  1010.6 1006.85  1050.3  1016.7  1060.2 1021.83    1080 1035.71
    1090 1038.43  1099.9 1042.59  1119.8 1055.75  1139.6 1065.47  1169.4 1077.21
  1189.3 1080.64  1238.9  1097.3  1268.7 1108.62  1288.5 1112.52    1358 1145.06
#Mann= 3 , 0 , 0
       0     .06       0   794.5    .045       0   829.5     .06       0
Bank Sta=794.5,829.5
XS Rating Curve= 0 ,0
Exp/Cntr=0.3,0.1

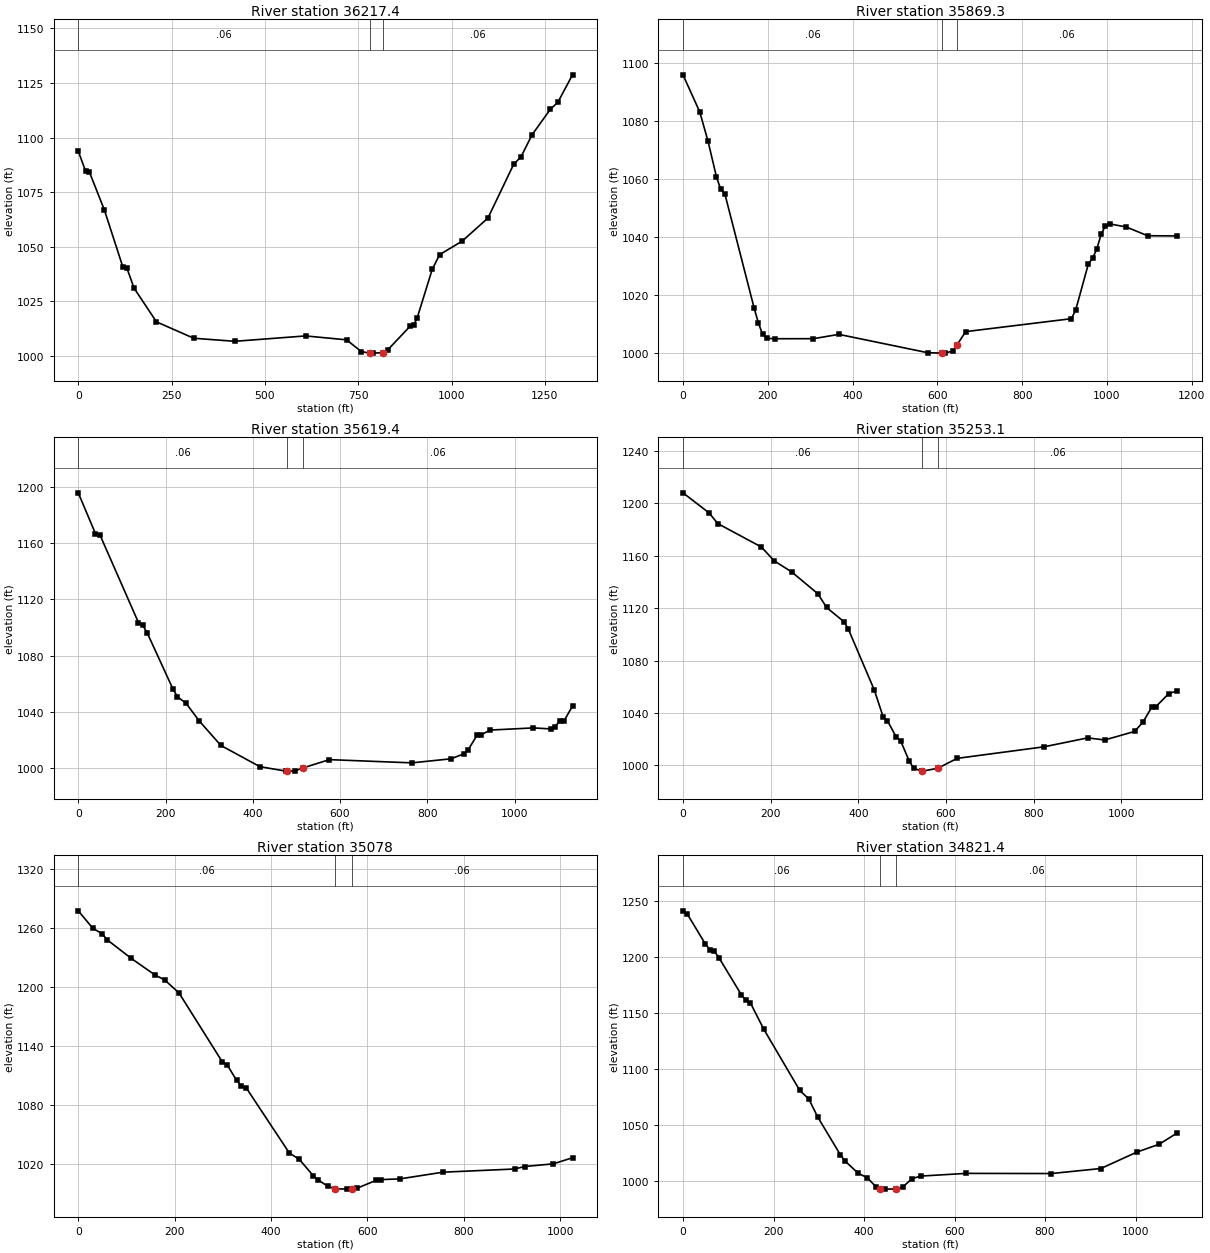
Type RM Length L Ch R = 1 ,36217.4 ,343.8,348.1,352.5
XS GIS Cut Line= 3
     1840362.061      346809.499      1840375.78      347877.338
      1840375.78      348133.436
#Sta/Elev= 30
       0 1093.76      20 1084.43    29.9 1084.16    69.9 1066.83   119.8  1040.5
   129.8 1040.36   149.7 1030.92   209.6 1015.52   309.4 1008.02   419.2 1006.62
   608.8 1009.08   718.6  1007.3   758.5 1001.89   780.3 1001.22   788.5  1001.2
   815.3 1001.41   828.4 1002.57   888.3 1013.41   898.3 1013.86   908.2 1017.52
   948.2 1039.57   968.1 1046.34    1028 1052.47  1097.5  1063.1  1166.4 1087.74
  1186.1 1091.19  1215.7 1101.26  1264.9 1112.99  1284.6  1116.1    1324 1128.72
#Mann= 3 , 0 , 0
       0     .06       0   780.3    .045       0   815.3     .06       0
Bank Sta=780.3,815.3
XS Rating Curve= 0 ,0
Exp/Cntr=0.3,0.1

Type RM Length L Ch R = 1 ,35869.3 ,256.3,249.9,243.5
XS GIS Cut Line= 3
     1840030.505      346930.688     1840099.102       347083.89
      1839973.34      348073.985
#Sta/Elev= 30
       0 1096.07    39.5 1083.28    59.2 1073.08      79  1060.8    88.9 1056.62
    98.7 1055.01   167.9 1015.54   177.8 1010.41   187.8 1006.55   197.8 1005.14
   217.8    1005   307.6 1005.01   367.5 1006.51   577.1 1000.18   610.6 1000.04
     617 1000.03   636.9 1000.78   645.6 1002.71   666.9 1007.45   916.4 1011.92
   926.4 1014.96   956.3 1030.85   966.3 1032.77   976.3 1036.04   986.3 1041.02
   996.2 1043.92  1006.2 1044.65  1046.1 1043.53    1096 1040.54  1165.9 1040.48
#Mann= 3 , 0 , 0
       0     .06       0   610.6    .045       0   645.6     .06       0
Bank Sta=610.6,645.6
XS Rating Curve= 0 ,0
Exp/Cntr=0.3,0.1

Type RM Length L Ch R = 1 ,35619.4 ,386.4,366.2,346.1
XS GIS Cut Line= 3
      1839765.26      346960.414     1839785.839      347106.756
      1839845.29      348089.991
#Sta/Elev= 30
       0 1195.84    39.4 1166.81    49.3 1166.17   137.9 1103.51   147.8 1101.56
   157.7 1096.34   217.4  1055.9   227.4 1050.65   247.3 1045.91   277.1  1033.5
   326.9 1015.97   416.4 1000.86   476.1   997.7     479   997.7     496  997.83
     514  999.89   575.6 1005.88   764.7 1003.59   854.2 1006.47   884.1 1010.05
     894 1013.05   913.9 1023.19   923.9 1023.59   943.8 1026.93  1043.3 1028.47
  1083.1 1027.75    1093 1029.36    1103  1033.3  1112.9  1033.2  1132.8 1044.07
#Mann= 3 , 0 , 0
       0     .06       0     479    .045       0     514     .06       0
Bank Sta=479,514
XS Rating Curve= 0 ,0
Exp/Cntr=0.3,0.1

Type RM Length L Ch R = 1 ,35253.1 ,175.8,175.1,174.4
XS GIS Cut Line= 3
     1839177.605      347205.079     1839760.687      347920.783
     1839832.028      348112.428
#Sta/Elev= 30
       0 1207.99    59.6 1192.62    79.4 1184.51   178.7 1166.66   208.4 1156.01
   248.2 1147.57   307.7 1130.96   327.6  1120.5   367.3 1109.57   377.2 1103.99
   436.8 1057.24   456.6    1037   466.5 1034.01   486.4 1021.67   496.3 1018.84
   516.2 1003.29   526.1  997.75     546   995.6   546.4   995.6   581.4   997.8
   625.4 1005.34   823.9 1014.17   923.2 1020.97   962.1 1019.38  1030.3 1025.87
  1049.8  1033.2  1069.2 1044.25    1079 1044.86  1108.2 1054.76  1127.6 1056.91
#Mann= 3 , 0 , 0
       0     .06       0   546.4    .045       0   581.4     .06       0
Bank Sta=546.4,581.4
XS Rating Curve= 0 ,0
Exp/Cntr=0.3,0.1

Type RM Length L Ch R = 1 ,35078   ,255.7,256.6,257.5
XS GIS Cut Line= 2
     1839035.137      347324.048     1839698.948      348105.997
#Sta/Elev= 30
       0 1277.25    29.9 1259.73    49.8 1253.75    59.8  1247.9   109.5 1229.09
   159.3 1212.03   179.2  1207.1   209.1 1193.78   298.8 1123.88   308.7    1121
   328.6    1105   338.6 1099.22   348.5 1097.45   438.2 1031.02   458.1 1025.01
     488 1007.92   497.9 1003.69   517.8  997.39   532.3  994.86   557.7  994.45
   567.3  994.55   577.6  995.18   617.4 1003.24   627.4 1004.13   667.2 1004.84
   756.8 1011.66   906.2 1014.92   926.1 1017.42   985.9 1020.15  1025.7 1026.34
#Mann= 3 , 0 , 0
       0     .06       0   532.3    .045       0   567.3     .06       0
Bank Sta=532.3,567.3
XS Rating Curve= 0 ,0
Exp/Cntr=0.3,0.1

Type RM Length L Ch R = 1 ,34821.4 ,438.9,435.7,432.5
XS GIS Cut Line= 3
      1838894.92      347534.375      1839237.04      347959.843
     1839590.846      348376.025
#Sta/Elev= 30
       0 1241.21     9.9  1238.1    49.6 1211.42    59.6 1206.43    69.5 1204.88
    79.4  1199.3     129 1166.11     139 1161.27   148.9 1158.88   178.7 1135.19
   258.1 1080.52   277.9 1073.02   297.8  1056.7   347.4 1023.26   357.4 1017.68
   387.1  1006.5     407  1002.5   426.8  994.32   436.1   992.8   446.7   992.3
   471.1  992.43   486.4  994.42   506.2 1001.77   526.1 1003.98   625.4 1006.38
   814.1 1006.24   923.4 1010.74  1002.8 1025.38  1052.5 1032.49  1092.2 1042.55
#Mann= 3 , 0 , 0
       0     .06       0   436.1    .045       0   471.1     .06       0
Bank Sta=436.1,471.1
XS Rating Curve= 0 ,0
Exp/Cntr=0.3,0.1

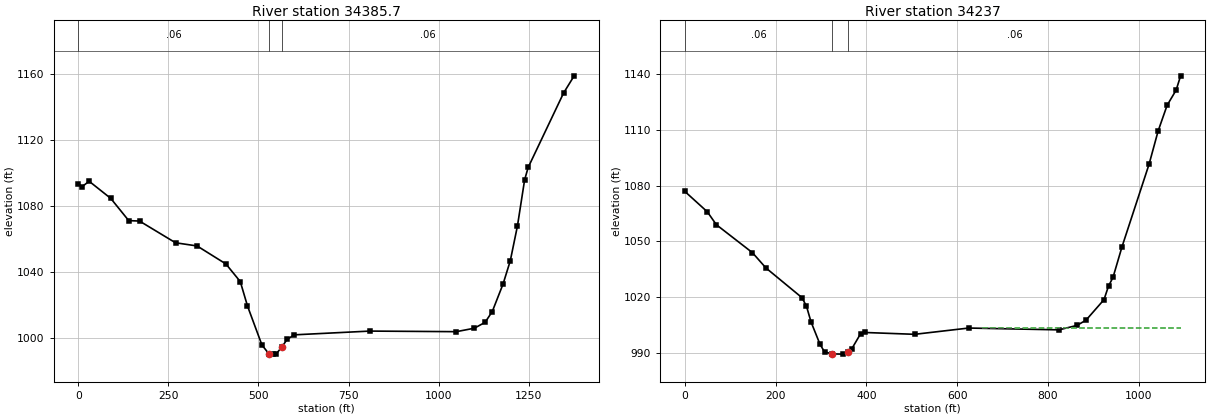
Type RM Length L Ch R = 1 ,34385.7 ,150.5,148.7,146.8
XS GIS Cut Line= 3
     1838486.618      347802.094     1839346.813      348679.932
      1839456.57      348778.256
#Sta/Elev= 30
       0 1093.55      10 1091.74      30 1095.08    89.9 1084.71   139.9 1071.21
   169.9 1070.94   269.8 1057.77   329.7 1055.84   409.7 1044.92   449.6 1034.21
   469.6  1019.4   509.6  995.79   529.2  990.34   539.6  990.22   549.6  990.51
   564.2  994.28   579.6  999.18   599.5 1001.92   809.4  1004.2  1049.2 1003.84
  1099.1 1005.93  1129.1 1009.49  1149.1 1016.06  1179.1  1032.8  1199.1 1046.86
    1219 1068.01  1238.9 1095.96  1248.7 1103.45  1346.9 1148.56  1376.4 1159.04
#Mann= 3 , 0 , 0
       0     .06       0   529.2    .045       0   564.2     .06       0
Bank Sta=529.2,564.2
XS Rating Curve= 0 ,0
Exp/Cntr=0.3,0.1

Type RM Length L Ch R = 1 ,34237   ,241,239.7,238.3
XS GIS Cut Line= 3
     1838515.627      348071.666     1838919.329      348439.284
     1839322.173      348807.839
#Sta/Elev= 30
       0 1076.89    49.6  1065.9    69.5 1058.95   148.9  1043.9   178.7 1035.66
   258.1 1019.65     268 1015.03     278 1006.61   297.8  994.52   307.8  990.44
     325  989.37   347.5  989.25     360  990.34   367.3  991.93   387.2 1000.24
   397.1  1000.9   506.3  999.92   625.4  1003.3     824 1002.32   863.7 1004.72
   883.5 1007.51   923.2 1018.58   933.2  1025.9   943.1  1030.6     963 1047.14
  1022.5 1091.53  1042.4 1109.37  1062.2 1123.23  1082.1 1131.44    1092 1139.13
#Mann= 3 , 0 , 0
       0     .06       0     325    .045       0     360     .06       0
#XS Ineff= 2 , 0
                          655.01         1003.39
Permanent Ineff=
       F       F
Bank Sta=325,360
XS Rating Curve= 0 ,0
Exp/Cntr=0.3,0.1