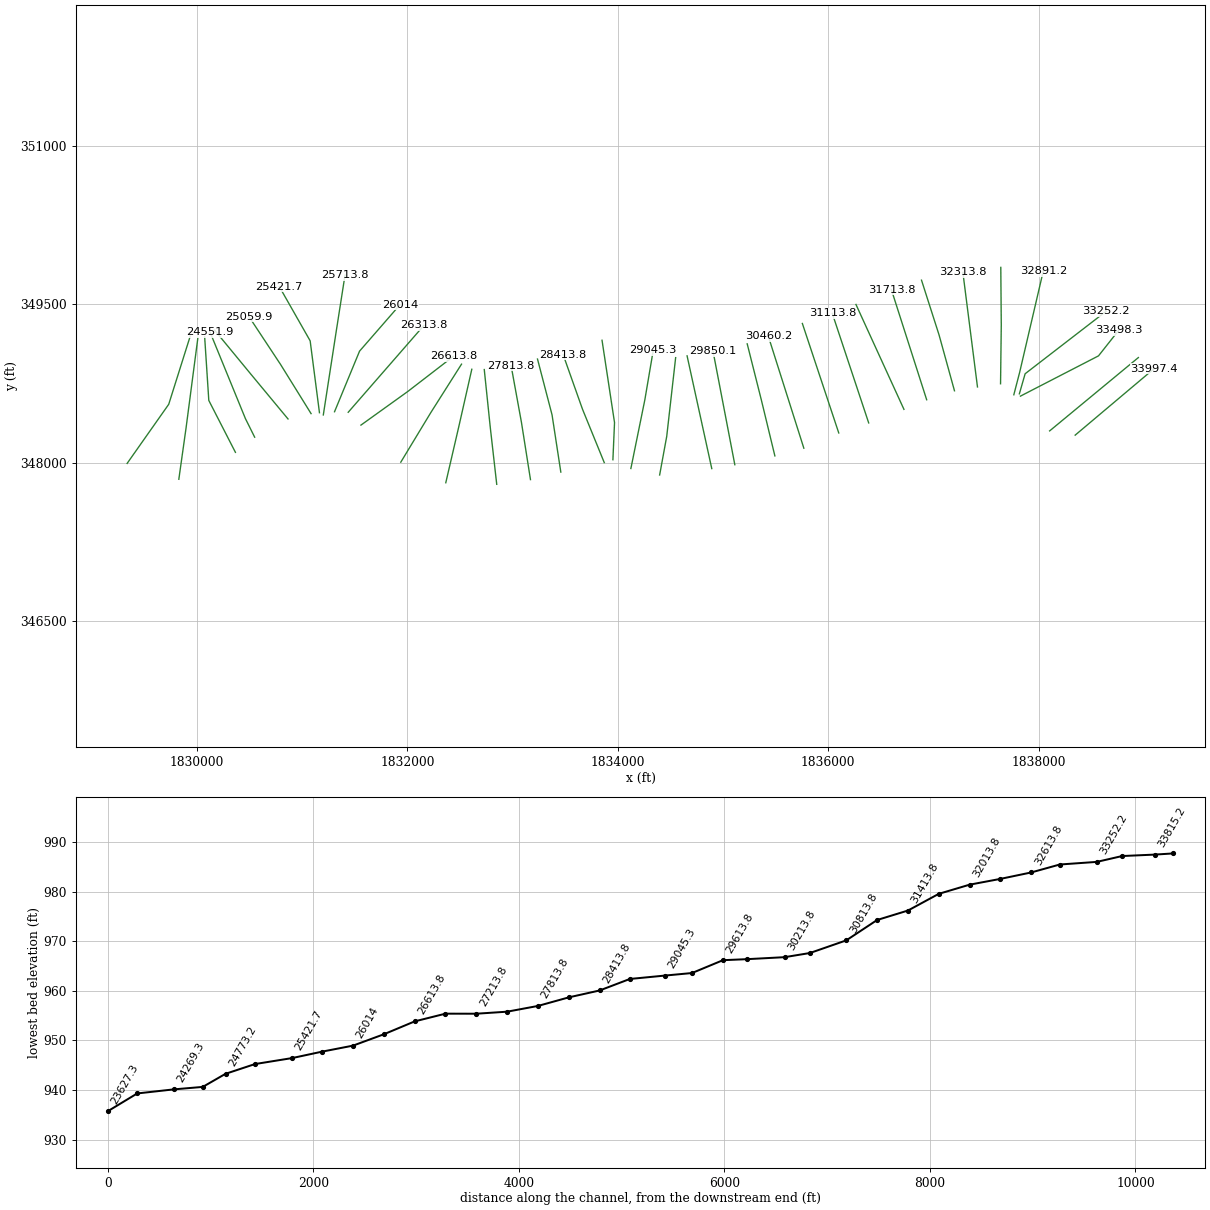
HEC-RAS study ClrFrk1.prj: ClrFrk1

--- ClrFrk1.g01 (geometry) --- (continued)

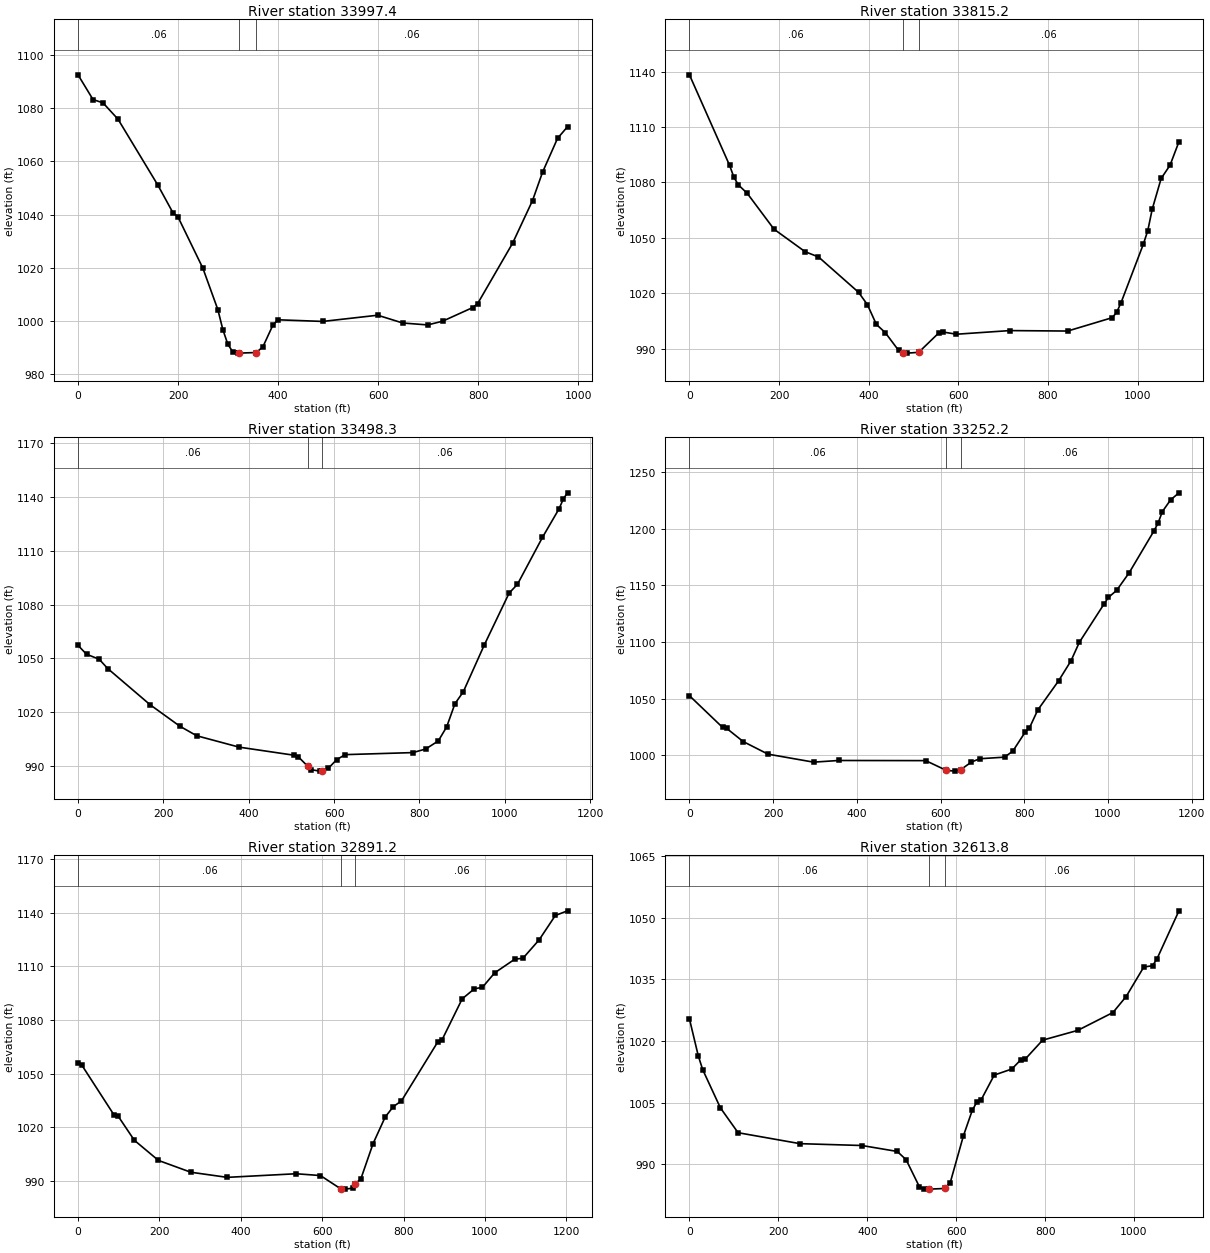
Type RM Length L Ch R = 1 ,33997.4 ,182.4,182.1,181.8
XS GIS Cut Line= 2
     1838347.572      348261.486     1839097.574      348890.299
#Sta/Elev= 30
       0 1092.66      30 1083.34    49.9  1082.1    79.9 1075.95   159.8 1051.02
   189.8 1040.67   199.7 1039.16   249.7 1019.73   279.6 1004.14   289.6   996.6
   299.6  991.05   309.6  988.19   319.6  987.74   321.2  987.74   356.2  987.97
   369.5  990.06   389.5  998.24   399.5 1000.31   489.4  999.69   599.2 1002.03
   649.2   999.1   699.1  998.37     729  999.78     789  1004.9     799  1006.4
   868.9 1029.18   908.8 1045.28   928.8 1055.95   958.8 1068.72   978.7 1073.09
#Mann= 3 , 0 , 0
       0     .06       0   321.2    .045       0   356.2     .06       0
Bank Sta=321.2,356.2
XS Rating Curve= 0 ,0
Exp/Cntr=0.3,0.1

Type RM Length L Ch R = 1 ,33815.2 ,323.9,316.9,309.9
XS GIS Cut Line= 3
     1838104.927      348301.539     1838526.564      348648.438
       1838948.2      348995.336
#Sta/Elev= 30
       0 1138.24    89.4  1089.3    99.3 1082.71   109.2 1078.61     129 1074.04
   188.6 1054.65   258.1 1042.43   287.9  1039.6   377.2 1020.46   397.1 1013.72
     417 1003.06   436.8  998.62   466.6  988.98   476.4  987.64   486.4   987.5
   511.4  987.93   555.9  998.35   565.8  998.93   595.6  997.74   714.8  999.71
   843.8  999.46   943.1  1006.7     953 1009.53     963 1014.91  1012.6 1046.52
  1022.5 1053.85  1032.4 1065.46  1052.3 1082.09  1072.2  1089.3    1092 1101.97
#Mann= 3 , 0 , 0
       0     .06       0   476.4    .045       0   511.4     .06       0
Bank Sta=476.4,511.4
XS Rating Curve= 0 ,0
Exp/Cntr=0.3,0.1

Type RM Length L Ch R = 1 ,33498.3 ,240.2,246.1,252
XS GIS Cut Line= 3
     1837827.129      348630.571     1838569.371      349011.488
     1838763.732      349256.154
#Sta/Elev= 30
       0 1057.29    19.9 1052.37    49.7 1049.55    69.5  1044.4   168.8 1024.23
   238.4 1012.27   278.1 1006.92   377.4 1000.58   506.5  996.06   516.5   995.1
   537.7  990.03   546.2  988.03   566.1  987.21   572.7  987.44     586  988.69
   605.8  993.55   625.7   996.4   784.6  997.54   814.4  999.52     844 1004.02
   863.6 1011.81   883.1 1024.79   902.6 1031.41   951.4  1057.3    1010 1086.42
  1029.6 1091.35  1088.2 1117.52  1127.2  1133.5    1137 1138.91  1146.8 1142.31
#Mann= 3 , 0 , 0
       0     .06       0   537.7    .045       0   572.7     .06       0
Bank Sta=537.7,572.7
XS Rating Curve= 0 ,0
Exp/Cntr=0.3,0.1

Type RM Length L Ch R = 1 ,33252.2 ,338.6,361,383.4
XS GIS Cut Line= 3
     1837817.082      348652.493      1837871.96       348842.28
     1838642.907      349434.117
#Sta/Elev= 30
       0 1052.61      79 1024.68    88.9 1023.78   128.4 1012.13   187.7 1001.02
   296.7  993.95   356.2  995.42   564.5   995.3   613.6  986.72   633.9  986.03
   648.6  987.42   673.6  994.03   693.4  996.95     753  998.38   772.8 1003.76
   802.5 1020.66   812.4 1024.23   832.3 1040.02   881.9 1065.69   911.6 1083.39
   931.5  1099.7     991 1133.79  1000.9 1139.32  1020.7 1145.59  1050.5 1161.07
    1110 1198.15  1119.9 1205.16  1129.8 1215.08  1149.6 1225.44  1169.5 1231.68
#Mann= 3 , 0 , 0
       0     .06       0   613.6    .045       0   648.6     .06       0
Bank Sta=613.6,648.6
XS Rating Curve= 0 ,0
Exp/Cntr=0.3,0.1

Type RM Length L Ch R = 1 ,32891.2 ,270.3,277.4,285.2
XS GIS Cut Line= 3
      1837764.49      348643.347     1837819.369      348853.713
     1838044.202      349813.024
#Sta/Elev= 30
       0 1055.77     9.9 1054.64    88.9 1026.82    98.8 1026.23   138.4 1012.81
   197.6 1001.55   277.1  994.95   366.7  992.08   535.9   994.1   595.6  993.09
   646.5  985.52   655.3   985.5   675.2  986.02   681.5  988.56   695.1  991.33
     725 1010.97   754.8 1025.84   774.8 1031.64   794.7 1034.83   884.2 1067.91
   894.2 1068.86     944 1091.92   973.8  1097.5   993.7 1098.34  1023.6  1106.4
  1073.3  1114.1  1093.2 1114.58    1133 1124.88  1172.8 1138.51  1202.7 1141.11
#Mann= 3 , 0 , 0
       0     .06       0   646.5    .045       0   681.5     .06       0
Bank Sta=646.5,681.5
XS Rating Curve= 0 ,0
Exp/Cntr=0.3,0.1

Type RM Length L Ch R = 1 ,32613.8 ,295.4,300,303.9
XS GIS Cut Line= 3
     1837638.242      348747.465     1837645.118      349304.461
     1837640.597      349848.495
#Sta/Elev= 30
       0 1025.38    19.9 1016.37    29.8 1013.02    69.6 1003.71   109.4  997.65
   248.7  994.98   387.9  994.53   467.5  993.08   487.4  991.07   517.2  984.49
   527.2   983.9   539.5   983.9   574.5  984.06   586.7   985.5   616.4  996.93
   636.2 1003.09   646.1 1005.05     656 1005.62   685.6 1011.69   725.2 1013.17
     745 1015.37   754.9 1015.53   794.4  1020.2   873.6 1022.59   952.7 1026.94
   982.4 1030.84    1022 1038.02  1041.7 1038.35  1051.6 1039.98  1101.1 1051.72
#Mann= 3 , 0 , 0
       0     .06       0   539.5    .045       0   574.5     .06       0
Bank Sta=539.5,574.5
XS Rating Curve= 0 ,0
Exp/Cntr=0.3,0.1

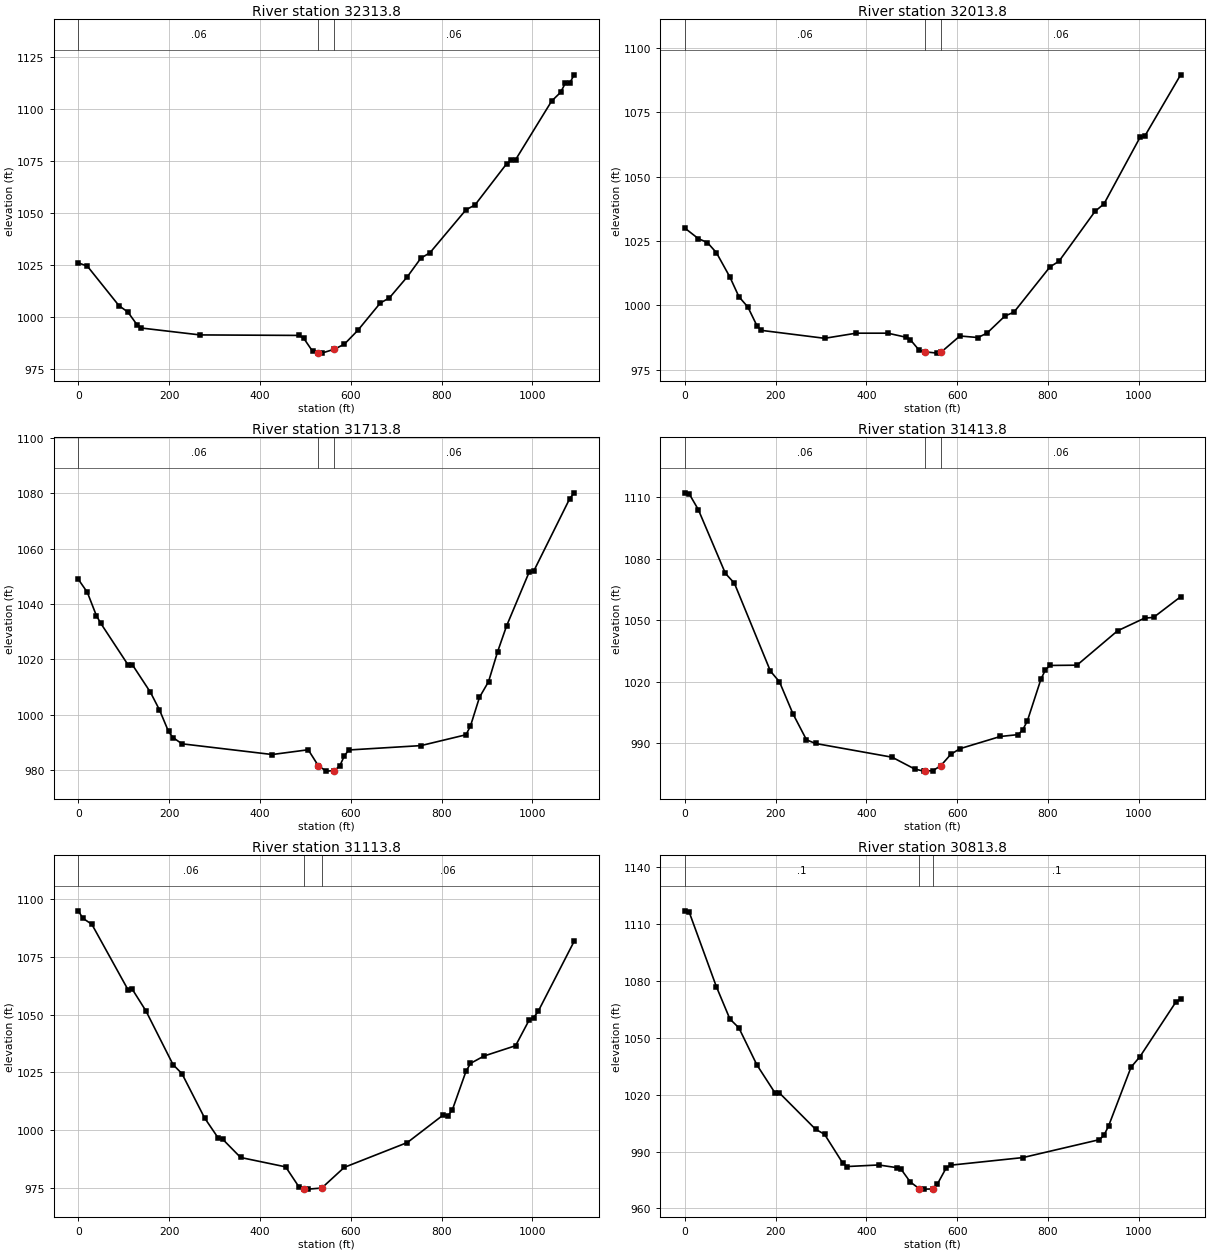
Type RM Length L Ch R = 1 ,32313.8 ,295.3,300,306
XS GIS Cut Line= 3
     1837418.858      348717.537      1837349.52      349259.116
     1837280.181      349800.696
#Sta/Elev= 30
       0 1026.06    19.8  1024.5    89.4 1005.48   109.2 1002.36     129  996.35
     139  994.68     268  991.37   486.4  991.13   496.4  989.76   516.2   983.4
   528.5  982.65   536.1   982.6   563.5  984.46   585.7  986.87   615.5  993.56
   665.1 1006.75     685 1009.19   724.7 1019.42   754.5 1028.37   774.3 1030.92
   853.8 1051.64   873.6 1053.96   943.1 1073.75     953 1075.49     963 1075.76
  1042.4    1104  1062.2 1108.21  1072.2 1112.48  1082.1 1112.65    1092 1116.64
#Mann= 3 , 0 , 0
       0     .06       0   528.5    .045       0   563.5     .06       0
Bank Sta=528.5,563.5
XS Rating Curve= 0 ,0
Exp/Cntr=0.3,0.1

Type RM Length L Ch R = 1 ,32013.8 ,298.7,300,300
XS GIS Cut Line= 3
     1837200.238      348681.248     1837054.211      349207.937
     1836886.916      349727.573
#Sta/Elev= 30
       0 1030.02    29.8 1025.91    49.7  1024.4    69.6 1020.47    99.4 1010.98
   119.2 1003.36   139.1   999.3     159  992.06   168.9  990.27   308.1  987.19
   377.6  989.18   447.2  989.18   486.9  987.63   496.9  986.64   516.8  982.49
   529.1  981.93   556.5  981.43   564.1   981.7   606.1  988.09   645.8  987.49
   665.7  989.17   705.4  995.85   725.2  997.33   804.6 1014.92   824.5 1017.14
   903.9  1036.5   923.7 1039.43  1003.1 1065.28  1013.1 1065.61  1092.5 1089.55
#Mann= 3 , 0 , 0
       0     .06       0   529.1    .045       0   564.1     .06       0
Bank Sta=529.1,564.1
XS Rating Curve= 0 ,0
Exp/Cntr=0.3,0.1

Type RM Length L Ch R = 1 ,31713.8 ,296.1,300,303.9
XS GIS Cut Line= 3
     1836935.971      348596.272     1836768.646      349116.001
     1836601.321       349635.73
#Sta/Elev= 30
       0 1048.88    19.8 1044.19    39.7  1035.8    49.6 1032.94   109.2 1018.05
   119.1    1018   158.8 1008.07   178.7 1001.71   198.6  993.91   208.5   991.7
   228.3  989.45   426.9  985.58   506.3   987.3   528.5  981.53     546  979.58
   563.5  979.74   575.8  981.46   585.7  985.04   595.6  987.22   754.5   988.8
   853.8  992.72   863.7  995.91   883.5 1006.26   903.4  1011.9   923.2 1022.62
   943.1 1032.02   992.7 1051.42  1002.6 1051.73  1082.1    1078    1092 1080.14
#Mann= 3 , 0 , 0
       0     .06       0   528.5    .045       0   563.5     .06       0
Bank Sta=528.5,563.5
XS Rating Curve= 0 ,0
Exp/Cntr=0.3,0.1

Type RM Length L Ch R = 1 ,31413.8 ,303.5,300,296.5
XS GIS Cut Line= 3
     1836719.859      348505.494     1836491.825      349001.595
     1836263.791      349497.696
#Sta/Elev= 30
       0  1112.2     9.9  1111.6    29.8 1103.99    89.4 1072.83   109.2 1068.03
   188.6 1025.07   208.5 1019.85   238.2 1004.23     268  991.51   287.9  989.72
   456.6  983.01   506.3  977.24   526.2  976.21   528.5  976.24     546  976.42
   563.5  978.78   585.7  984.38   605.6  987.15   694.9  993.14   734.6  994.06
   744.6  996.54   754.5 1000.78   784.2 1021.04   794.2  1025.7   804.1 1027.85
   863.7 1027.98     953 1044.76  1012.6 1050.97  1032.4 1051.33    1092 1061.42
#Mann= 3 , 0 , 0
       0     .06       0   528.5    .045       0   563.5     .06       0
Bank Sta=528.5,563.5
XS Rating Curve= 0 ,0
Exp/Cntr=0.3,0.1

Type RM Length L Ch R = 1 ,31113.8 ,300,300,300
XS GIS Cut Line= 3
     1836384.799      348377.183     1836211.824       348895.06
     1836038.849      349412.936
#Sta/Elev= 30
       0 1094.97     9.9 1091.76    29.8 1089.12   109.2 1060.83   119.1 1060.88
   148.9 1051.57   208.5 1028.32   228.3 1024.34     278 1005.19   307.8  996.54
   317.7  995.98   357.4  988.02   456.6  983.95   486.4  975.12   496.4  974.38
   506.3   974.3   536.1  974.77   585.7  983.74   724.7  994.51   804.1 1006.52
     814 1006.03     824 1008.82   853.8 1025.39   863.7 1028.82   893.4 1032.01
     963 1036.49   992.7 1047.55  1002.6 1048.63  1012.6 1051.32    1092 1081.76
#Mann= 3 , 0 , 0
       0     .06       0   496.4    .045       0   536.1     .06       0
Bank Sta=496.4,536.1
XS Rating Curve= 0 ,0
Exp/Cntr=0.3,0.1

Type RM Length L Ch R = 1 ,30813.8 ,354,353.6,353.1
XS GIS Cut Line= 3
     1836100.251      348282.142     1835927.276      348800.018
     1835754.302      349317.894
#Sta/Elev= 30
       0  1116.8     9.9 1115.98    69.5 1076.87    99.3 1059.82   119.1 1055.15
   158.8 1035.63   198.6  1020.9   208.5 1020.83   287.9 1001.76   307.8  999.07
   347.4  984.07   357.4  982.09   426.9  982.92   466.6  981.52   476.5  980.62
   496.4  974.01   516.2  970.44   526.2  970.19     546  970.28   555.9  972.67
   575.8  981.41   585.7  982.81   744.6  986.81   913.3  996.26   923.2  998.61
   933.2 1003.37   982.8 1034.43  1002.6 1040.03  1082.1 1068.96    1092 1070.26
#Mann= 3 , 0 , 0
       0      .1       0   516.2    .045       0     546      .1       0
Bank Sta=516.2,546
XS Rating Curve= 0 ,0
Exp/Cntr=0.3,0.1

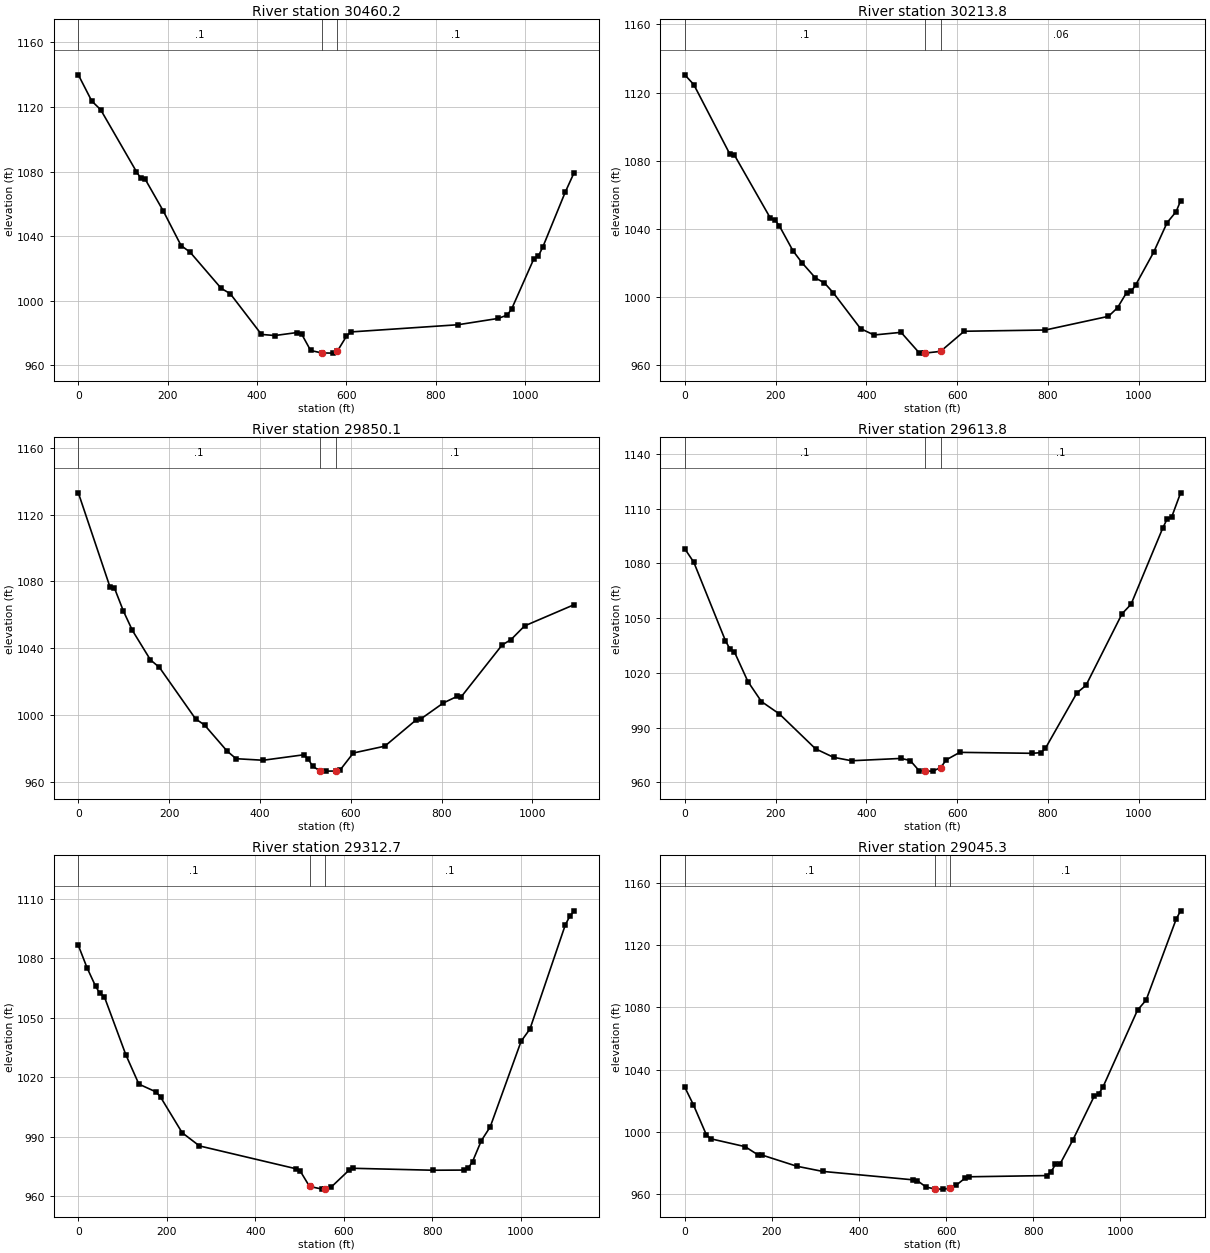
Type RM Length L Ch R = 1 ,30460.2 ,248.7,246.4,244.4
XS GIS Cut Line= 2
     1835768.294       348138.01     1835431.333      349195.092
#Sta/Elev= 30
       0 1139.88      30 1123.68      50 1118.28   129.9 1080.02   139.9 1075.83
   149.9 1075.13   189.9 1055.71   229.9  1034.2   249.9 1030.18   319.8  1007.7
   339.8 1004.46   409.8  979.21   439.8  978.53   489.8   980.4   499.8   979.4
   519.8  969.29   544.4  967.77   569.7  967.64   579.4  968.77   599.7  977.96
   609.7  980.75   849.6  985.21   939.6  989.12   959.6  991.18   969.6  994.96
  1019.5 1026.15  1029.5 1027.74  1039.5 1033.42  1089.5 1067.23  1109.5 1079.41
#Mann= 3 , 0 , 0
       0      .1       0   544.4    .045       0   579.4      .1       0
Bank Sta=544.4,579.4
XS Rating Curve= 0 ,0
Exp/Cntr=0.3,0.1

Type RM Length L Ch R = 1 ,30213.8 ,365.2,363.7,361.8
XS GIS Cut Line= 3
      1835492.93      348065.117     1835364.078      348595.566
     1835229.989      349125.232
#Sta/Elev= 30
       0 1130.41    19.8 1124.67    99.2 1083.82   109.2 1083.27   188.6 1046.12
   198.5 1045.06   208.4 1041.56   238.2    1027     258 1019.99   287.8 1010.99
   307.7 1008.03   327.5 1002.15   387.1  981.22   416.8  977.46   476.4  979.02
   516.1  967.04     526   966.8   528.4   966.8   563.4  967.83   615.4  979.66
   794.2  980.39   933.3  988.44   953.2  993.49     973  1002.3     983 1003.04
   992.9 1006.75  1032.6 1026.02  1062.4  1043.5  1082.3 1049.98  1092.2  1056.4
#Mann= 3 , 0 , 0
       0      .1       0   528.4    .045       0   563.4     .06       0
Bank Sta=528.4,563.4
XS Rating Curve= 0 ,0
Exp/Cntr=0.3,0.1

Type RM Length L Ch R = 1 ,29850.1 ,235.5,236.3,237.2
XS GIS Cut Line= 3
     1835112.261      347981.546     1835008.815      348517.657
     1834905.368      349053.768
#Sta/Elev= 30
       0 1132.98    69.5 1076.78    79.4 1076.08    99.3 1062.18   119.1  1050.6
   158.8    1033   178.7 1028.44   258.1  997.71     278  993.99   327.6  978.41
   347.4  973.84     407  972.91   496.4  976.18   506.3  973.64   516.2  969.24
   532.5  966.57     546   966.4   567.5  966.47   575.8   966.8   605.6  977.25
     675  981.34   744.6   997.2   754.5  997.68   804.1 1007.23   833.9  1011.1
   843.8 1011.06   933.2 1041.86     953 1045.15   982.8 1053.31    1092 1066.04
#Mann= 3 , 0 , 0
       0      .1       0   532.5    .045       0   567.5      .1       0
Bank Sta=532.5,567.5
XS Rating Curve= 0 ,0
Exp/Cntr=0.3,0.1

Type RM Length L Ch R = 1 ,29613.8 ,311.9,301.1,290.3
XS GIS Cut Line= 3
      1834893.04      347945.181     1834775.739      348478.432
     1834658.438      349011.683
#Sta/Elev= 30
       0 1088.05    19.8 1080.69    89.4 1037.74    99.3 1033.17   109.2 1031.56
     139 1015.29   168.8 1004.33   208.5  997.49   287.9  978.43   327.6  973.76
   367.3  971.88   476.5  973.16   496.4  972.01   516.2  966.38   528.5   966.2
     546  966.19   563.5  968.13   575.8  972.37   605.6  976.48   764.4  975.96
   784.2   976.3   794.2  978.69   863.7 1009.11   883.5 1013.18     963 1052.44
   982.8 1057.65  1052.3 1099.21  1062.2 1104.39  1072.2  1105.4    1092 1118.73
#Mann= 3 , 0 , 0
       0      .1       0   528.5    .045       0   563.5      .1       0
Bank Sta=528.5,563.5
XS Rating Curve= 0 ,0
Exp/Cntr=0.3,0.1

Type RM Length L Ch R = 1 ,29312.7 ,269.5,267,264.6
XS GIS Cut Line= 3
     1834397.654      347884.646     1834464.936      348250.053
     1834549.743      348994.588
#Sta/Elev= 30
       0 1086.53    19.6 1075.29    39.1 1065.88    48.9 1062.27    58.7  1060.7
   107.6 1031.25   136.9 1016.56     176 1012.59   185.8 1010.05   234.7  992.05
   273.8  985.39   491.4  973.91   501.4  972.81   522.6  964.96   551.4   963.6
   557.6   963.6   571.4  964.58   611.3  973.02   621.3  974.11   801.2  973.13
   871.1  973.21   881.1  974.08   891.1  977.44   911.1  988.07   931.1  994.99
    1001 1038.19    1021 1044.37  1100.9 1096.88  1110.9 1101.17  1120.9 1103.96
#Mann= 3 , 0 , 0
       0      .1       0   522.6    .045       0   557.6      .1       0
Bank Sta=522.6,557.6
XS Rating Curve= 0 ,0
Exp/Cntr=0.3,0.1

Type RM Length L Ch R = 1 ,29045.3 ,327.3,338.3,349.5
XS GIS Cut Line= 3
     1834124.234      347945.936     1834256.856      348595.328
     1834336.887       349064.08
#Sta/Elev= 30
       0 1028.63    19.8  1017.3    49.5  998.04    59.4  995.47   138.5   990.4
   168.2  985.08   178.1  984.92   257.2   977.8   316.6  974.48   524.3  969.05
   534.2  968.48     554  964.38   574.6   963.2   593.6  963.08   609.6  963.61
   623.2  965.62     643  970.06   652.9  971.02   831.2   971.8   841.1  974.35
     851  978.96   860.9  978.95   890.7  994.58   940.2 1023.03   950.1 1024.19
     960 1028.74  1039.3 1078.19  1059.1 1084.68  1128.4 1136.95  1138.3 1142.07
#Mann= 3 , 0 , 0
       0      .1       0   574.6    .045       0   609.6      .1       0
Bank Sta=574.6,609.6
XS Rating Curve= 0 ,0
Exp/Cntr=0.3,0.1

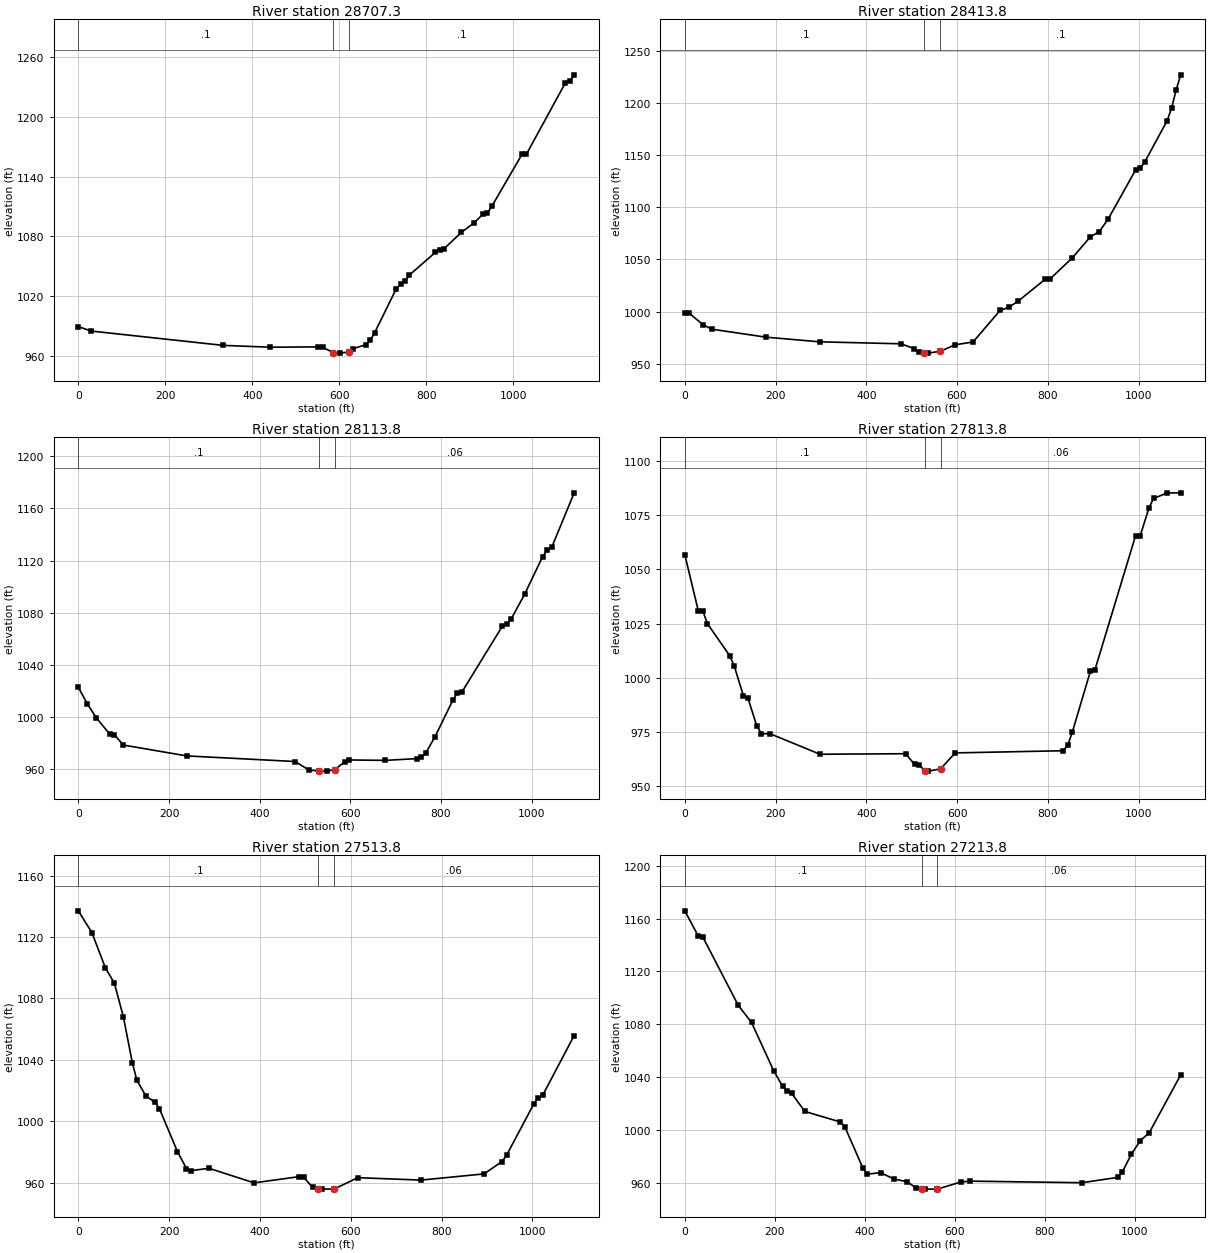
Type RM Length L Ch R = 1 ,28707.3 ,285.6,293.4,299.7
XS GIS Cut Line= 3
     1833953.357       348028.83     1833968.745      348380.388
     1833849.902      349159.154
#Sta/Elev= 30
       0  989.11    29.3  984.63   332.4  970.21   441.6  968.34   551.3   968.7
   561.3  968.23   586.3  962.95   601.2   962.4   621.3  963.53   631.1  966.78
     661  970.93     671  975.22     681  982.86   730.8 1027.16   740.8 1031.89
   750.8 1034.94   760.7 1040.88   820.6 1063.74   830.6 1066.36   840.5 1067.44
   880.4 1083.87   910.3 1093.74   930.3 1102.39   940.2 1103.34   950.2 1110.01
    1020 1162.59    1030 1162.59  1119.7 1234.54  1129.7 1235.81  1139.7 1242.47
#Mann= 3 , 0 , 0
       0      .1       0   586.3    .045       0   621.3      .1       0
Bank Sta=586.3,621.3
XS Rating Curve= 0 ,0
Exp/Cntr=0.3,0.1

Type RM Length L Ch R = 1 ,28413.8 ,307.9,300,296.9
XS GIS Cut Line= 3
     1833871.127      348001.827     1833664.236      348506.922
     1833480.545      349022.154
#Sta/Elev= 30
       0  998.69     9.9  998.38    39.7   987.5    59.5  983.07   178.6  975.42
   297.7  970.92   476.4  969.04   506.1  964.36     516  960.79   528.3  960.12
   535.9  960.08   563.3  961.87   595.6  968.05   635.3  970.78     695 1001.09
   714.9 1004.22   734.8 1010.05   794.5 1031.06   804.4 1031.05   854.1 1051.53
   893.9 1071.75   913.8 1076.84   933.7 1089.25   993.4 1135.83  1003.3 1137.83
  1013.3 1143.28    1063 1183.19  1072.9  1195.3  1082.9 1212.66  1092.8 1227.28
#Mann= 3 , 0 , 0
       0      .1       0   528.3    .045       0   563.3      .1       0
Bank Sta=528.3,563.3
XS Rating Curve= 0 ,0
Exp/Cntr=0.3,0.1

Type RM Length L Ch R = 1 ,28113.8 ,299.9,300,297.5
XS GIS Cut Line= 3
     1833458.218      347911.925     1833374.785      348453.593
     1833236.556      348981.431
#Sta/Elev= 30
       0 1022.95    19.9 1010.22    39.9  999.46    69.8  986.78    79.7  986.34
    99.6  978.66   239.2  970.35   478.3  966.05   508.2  959.62   530.6  958.79
   548.1  958.69   565.6   959.9   587.7  965.84   597.7  967.26     677  966.93
   746.5  968.26   756.4  969.24   766.3  972.54   786.2  984.66   825.8 1012.84
   835.8 1018.52   845.7 1019.08     935 1069.59   944.9 1071.31   954.8 1075.29
   984.6 1094.38  1024.2 1123.16  1034.2 1128.05  1044.1 1130.11  1093.7    1172
#Mann= 3 , 0 , 0
       0      .1       0   530.6    .045       0   565.6     .06       0
Bank Sta=530.6,565.6
XS Rating Curve= 0 ,0
Exp/Cntr=0.3,0.1

Type RM Length L Ch R = 1 ,27813.8 ,301.4,300,297.5
XS GIS Cut Line= 3
     1833169.772      347840.927     1833084.297      348380.161
     1832985.889      348917.413
#Sta/Elev= 30
       0 1056.77    29.8 1030.82    39.7 1030.79    49.6 1025.01    99.3 1010.08
   109.2 1005.21     129   991.8     139  990.68   158.8  977.67   168.8  974.25
   188.6  974.14   297.8  964.74   486.4  964.99   506.3  960.04   516.2   959.8
   528.5  957.21     536  956.96   563.5  957.98   595.6  965.36     834  966.36
   843.9   969.1   853.8  975.06   893.5 1003.05   903.5  1003.7   992.8  1065.4
  1002.8 1065.22  1022.6 1078.39  1032.6 1082.65  1062.4  1085.2  1092.2 1085.26
#Mann= 3 , 0 , 0
       0      .1       0   528.5    .045       0   563.5     .06       0
Bank Sta=528.5,563.5
XS Rating Curve= 0 ,0
Exp/Cntr=0.3,0.1

Type RM Length L Ch R = 1 ,27513.8 ,311.2,300,289.3
XS GIS Cut Line= 3
     1832848.992       347796.24     1832787.204      348338.727
     1832730.585      348881.814
#Sta/Elev= 30
       0 1137.09    29.8 1122.93    59.6 1099.92    79.4 1089.95    99.3 1067.91
   119.1 1037.84     129 1026.72   148.9 1016.38   168.8 1012.47   178.7 1008.15
   218.4  980.16   238.2  969.23   248.2  967.85   287.9  969.36   387.2  959.88
   486.4  963.94   496.4  963.46   516.2  956.91   528.5  955.87   536.1   955.8
   563.5  955.87   615.5  963.26   754.5  961.68   893.5  965.72   933.2  973.78
   943.1  977.85  1002.7 1011.06  1012.6 1015.48  1022.5 1016.84    1092 1055.85
#Mann= 3 , 0 , 0
       0      .1       0   528.5    .045       0   563.5     .06       0
Bank Sta=528.5,563.5
XS Rating Curve= 0 ,0
Exp/Cntr=0.3,0.1

Type RM Length L Ch R = 1 ,27213.8 ,310.3,300,288.8
XS GIS Cut Line= 3
     1832364.698      347811.181     1832488.157      348340.666
     1832612.085      348884.914
#Sta/Elev= 30
       0 1165.83    29.7 1146.88    39.5  1146.4   118.6 1094.48   148.3  1081.4
   197.7 1044.78   217.5 1033.03   227.4 1029.37   237.2 1027.92   266.9 1014.11
     346 1006.13   355.9 1002.33   395.4  971.58   405.3  966.72     435  967.82
   464.6   963.1   494.3  960.92     514  956.29   526.2  955.41   533.8  955.39
   561.2   955.4   613.5   960.8   633.4  961.44   882.6  960.23   962.3  964.28
   972.3  968.34   992.2  981.65  1012.2  992.01  1032.1  998.01  1101.9 1041.67
#Mann= 3 , 0 , 0
       0      .1       0   526.2    .045       0   561.2     .06       0
Bank Sta=526.2,561.2
XS Rating Curve= 0 ,0
Exp/Cntr=0.3,0.1

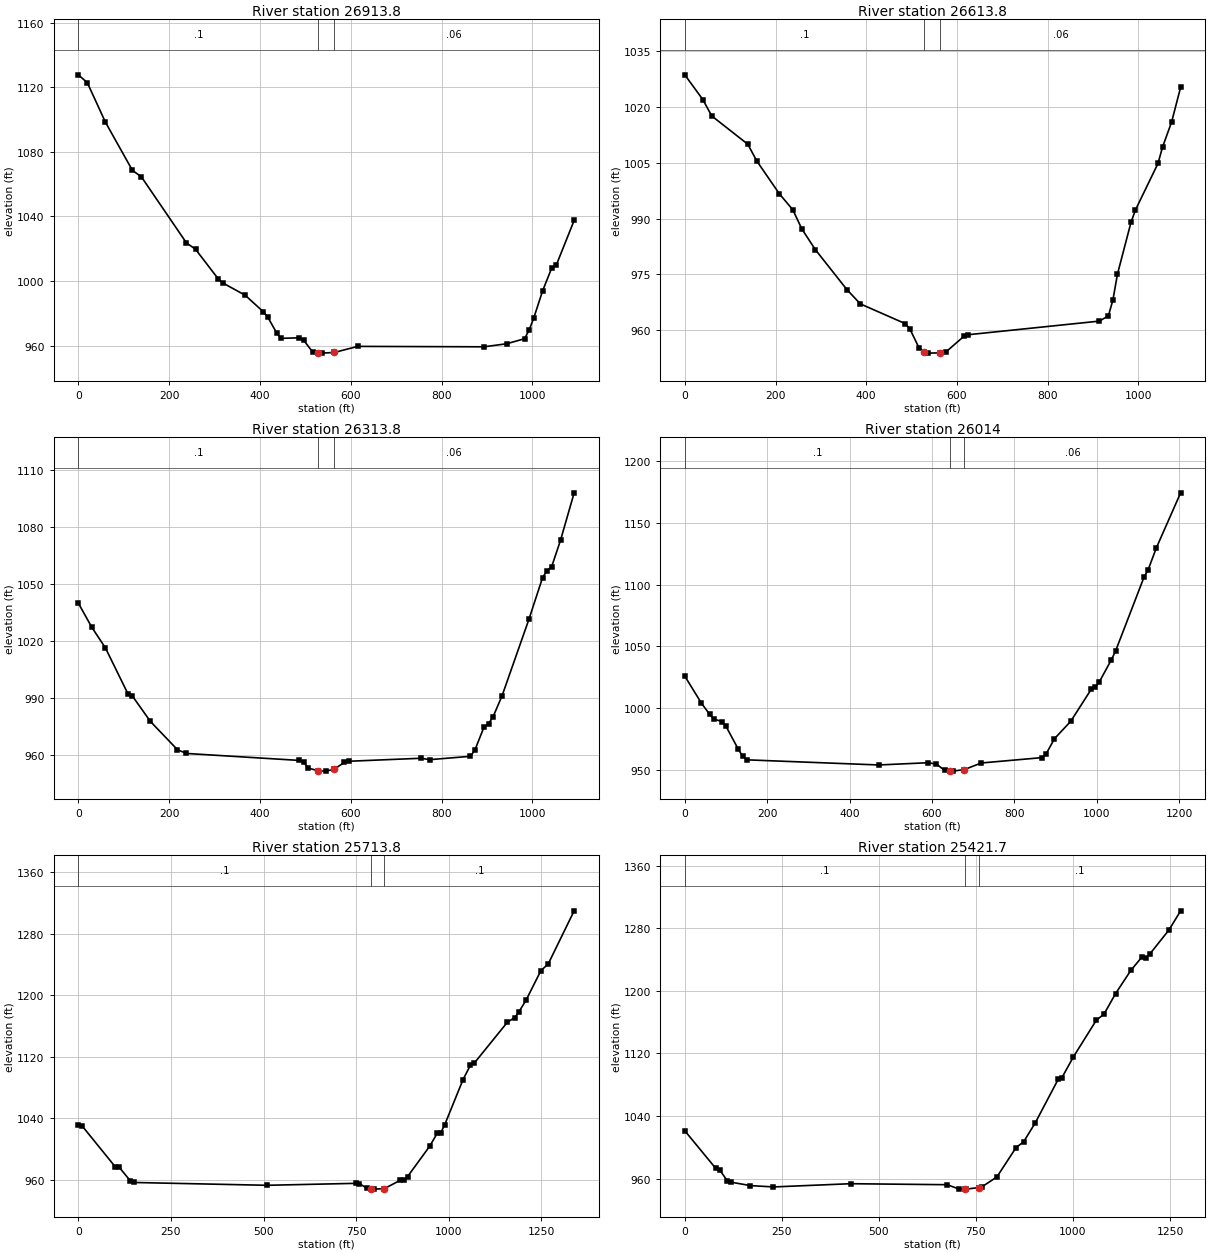
Type RM Length L Ch R = 1 ,26913.8 ,313.2,300,288.6
XS GIS Cut Line= 3
     1831937.118       348005.92     1832220.809      348472.405
     1832514.233      348933.025
#Sta/Elev= 30
       0 1127.63    19.8 1122.76    59.6 1098.36   119.1 1068.52     139 1064.45
   238.2 1023.58   258.1 1019.71   307.7 1001.51   317.7   998.9   367.3  991.26
     407  981.12   416.9  977.84   436.8  967.94   446.7  964.54   486.4  964.89
   496.3   963.4   516.2  956.07   528.5  955.41     536   955.4   563.5   955.8
   615.5  959.57   893.5  959.31   943.2  961.19   982.9  964.31   992.8  969.62
  1002.8  976.87  1022.6  993.93  1042.5 1007.98  1052.4 1009.65  1092.1 1037.54
#Mann= 3 , 0 , 0
       0      .1       0   528.5    .045       0   563.5     .06       0
Bank Sta=528.5,563.5
XS Rating Curve= 0 ,0
Exp/Cntr=0.3,0.1

Type RM Length L Ch R = 1 ,26613.8 ,292.3,299.9,306.4
XS GIS Cut Line= 3
     1831558.332      348356.453     1832002.454      348673.666
     1832436.708      349006.747
#Sta/Elev= 30
       0 1028.68    39.7 1022.03    59.5 1017.61   138.9 1010.01   158.8 1005.49
   208.4   996.7   238.2  992.37     258  987.24   287.8  981.67   357.2  970.95
     387  967.08   486.2  961.76   496.2  960.34     516  955.35   528.3  954.03
   535.8  953.84   563.3  953.91   575.6  954.14   615.4  958.37   625.4   958.8
     914  962.45   933.8  963.86   943.8  968.11   953.8  975.06   983.6  988.98
   993.6  992.36  1043.3 1004.88  1053.2 1009.25  1073.2 1015.98  1093.1 1025.34
#Mann= 3 , 0 , 0
       0      .1       0   528.3    .045       0   563.3     .06       0
Bank Sta=528.3,563.3
XS Rating Curve= 0 ,0
Exp/Cntr=0.3,0.1

Type RM Length L Ch R = 1 ,26313.8 ,299.8,299.8,299.8
XS GIS Cut Line= 3
     1831437.315      348477.997     1831796.982      348888.796
     1832156.649      349299.594
#Sta/Elev= 30
       0 1039.74    29.8 1026.98    59.6 1016.18   109.2     992   119.1  990.79
   158.8   977.4   218.4   962.5   238.2  960.55   486.4  956.88   496.4  955.83
   506.3  952.89   528.5  951.37     546  951.24   563.5  952.27   585.7  955.79
   595.6  956.44   754.5  958.02   774.3  957.29   863.7  959.05   873.6  962.46
   893.4  974.45   903.4   976.2   913.3  979.82   933.2  990.92   992.7 1031.46
  1022.5 1053.23  1032.4 1056.92  1042.4 1058.89  1062.2 1073.06    1092 1097.86
#Mann= 3 , 0 , 0
       0      .1       0   528.5    .045       0   563.5     .06       0
Bank Sta=528.5,563.5
XS Rating Curve= 0 ,0
Exp/Cntr=0.3,0.1

Type RM Length L Ch R = 1 ,26014   ,281.7,300.2,318.6
XS GIS Cut Line= 3
     1831307.151      348482.904     1831544.956      349056.077
     1831928.634      349494.585
#Sta/Elev= 30
       0 1025.91      40 1004.19      60  995.06    70.1  991.22    90.1  989.11
   100.1  985.18   130.1  966.51   140.1  961.13   150.1   958.1   470.4  953.94
   590.5  955.76   610.5  954.69   630.4  949.59   643.2  948.96   650.2  948.95
   678.2  950.19   719.3  955.54   867.4  959.91   877.3  963.22   897.1  975.25
   936.6  989.34     986  1015.1   995.8 1016.76  1005.7 1021.11  1035.3 1039.29
  1045.2 1046.14  1114.3 1106.04  1124.2  1111.9    1144 1129.58  1203.2 1174.41
#Mann= 3 , 0 , 0
       0      .1       0   643.2    .045       0   678.2     .06       0
Bank Sta=643.2,678.2
XS Rating Curve= 0 ,0
Exp/Cntr=0.3,0.1

Type RM Length L Ch R = 1 ,25713.8 ,269.9,292,314.1
XS GIS Cut Line= 3
     1831200.443      348452.416     1831324.507      349251.686
      1831406.76      349775.192
#Sta/Elev= 30
       0 1031.11      10 1030.03    99.9  976.63   109.8  976.52   139.8  958.83
   149.8  956.39   509.3  952.72   748.9  955.26   758.9  954.97   778.9  948.89
   791.3  948.48   798.9  947.74   826.3  948.39   868.8  959.12   878.8  959.21
   888.8  963.91   948.8 1003.56   968.8 1020.12   978.8 1021.26   988.8 1030.88
  1038.8 1090.18  1058.8 1108.96  1068.8 1111.36  1158.8 1164.87  1178.8 1170.79
  1188.8 1177.62  1208.8 1193.23  1248.8 1231.62  1268.8 1240.51  1338.8 1309.51
#Mann= 3 , 0 , 0
       0      .1       0   791.3    .045       0   826.3      .1       0
Bank Sta=791.3,826.3
XS Rating Curve= 0 ,0
Exp/Cntr=0.3,0.1

Type RM Length L Ch R = 1 ,25421.7 ,359.7,361.9,364
XS GIS Cut Line= 3
     1831163.858      348473.758     1831075.443      349153.638
     1830781.886      349667.332
#Sta/Elev= 30
       0 1021.07    79.5   973.1    89.4  971.27   109.3  957.25   119.2   955.3
   168.9  950.96   228.5  949.24   427.3  953.37   675.7  952.09   705.3   946.8
   722.6  946.45     725  946.44   757.6  948.44   764.5  949.07   803.9  961.97
   853.2  999.48     873 1007.06   902.6 1030.98   961.7 1086.66   971.6 1089.12
  1001.2 1115.66  1060.3 1162.59    1080 1170.25  1109.6 1196.45  1149.1  1226.2
  1178.6 1243.89  1188.5 1242.49  1198.4 1247.39  1247.7 1278.14  1277.3 1302.34
#Mann= 3 , 0 , 0
       0      .1       0   722.6    .045       0   757.6      .1       0
Bank Sta=722.6,757.6
XS Rating Curve= 0 ,0
Exp/Cntr=0.3,0.1

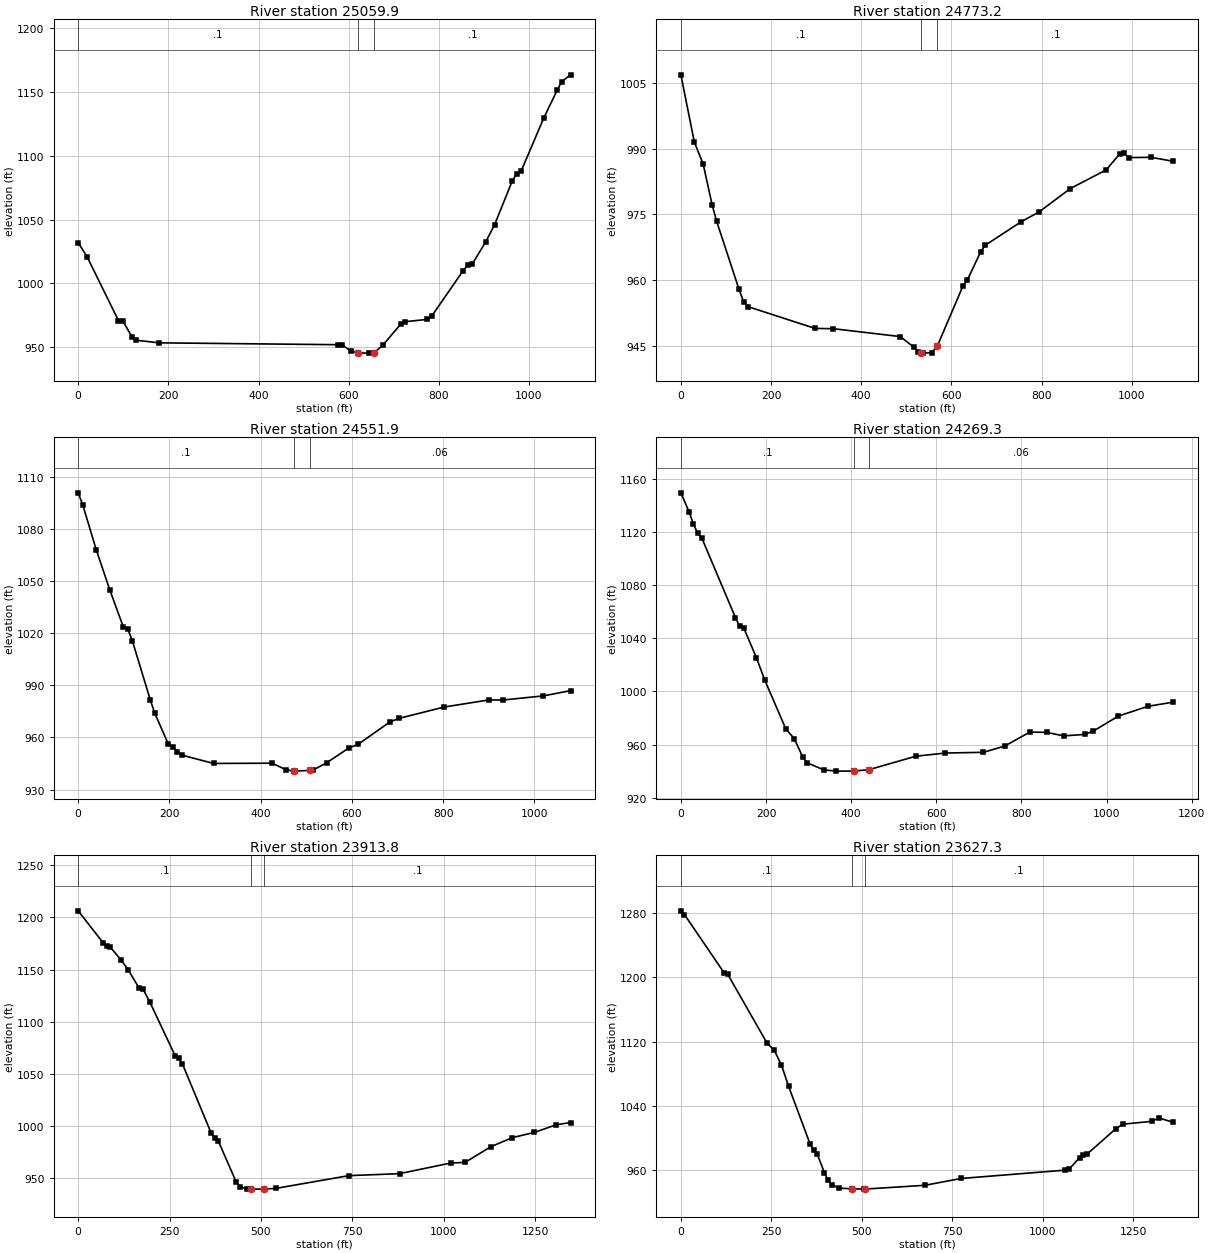
Type RM Length L Ch R = 1 ,25059.9 ,283.1,286.7,290.1
XS GIS Cut Line= 3
     1831084.217      348464.949     1830795.195      348928.495
     1830493.363      349383.423
#Sta/Elev= 30
       0 1031.95    19.9 1020.78    89.4  970.77    99.3  970.37   119.2   958.1
   129.1  955.36   178.8  953.31     576  951.84     586  951.45   605.8  946.72
   621.1  945.37   645.5  945.23   656.1  945.51   675.3  951.22     715  967.81
   724.9  969.88   774.6  971.71   784.5  974.45     854 1009.97   863.9 1014.28
   873.8 1014.95   903.6  1032.3   923.5 1045.83   963.2 1080.68   973.1 1086.04
     983 1088.45  1032.7 1129.72  1062.4 1151.56  1072.4 1158.29  1092.2 1163.64
#Mann= 3 , 0 , 0
       0      .1       0   621.1    .045       0   656.1      .1       0
Bank Sta=621.1,656.1
XS Rating Curve= 0 ,0
Exp/Cntr=0.3,0.1

Type RM Length L Ch R = 1 ,24773.2 ,231.6,221.3,211.1
XS GIS Cut Line= 3
     1830864.963      348414.586     1830515.434      348834.044
      1830167.24      349254.616
#Sta/Elev= 30
       0 1006.97    29.8   991.6    49.6  986.48    69.5  977.13    79.4  973.42
     129  957.84     139  955.04   148.9   953.9   297.8  948.91   337.5  948.86
   486.4  947.05   516.2  944.67   526.1   943.5   533.6  943.32   536.1  943.26
   555.9  943.36   568.6  944.85   625.4   958.6   635.4  960.02   665.1   966.5
     675  967.95   754.5  973.33   794.2  975.57   863.7  980.94   943.1   985.2
   972.9  988.82   982.8  989.01   992.7  988.02  1042.4  988.09    1092  987.17
#Mann= 3 , 0 , 0
       0      .1       0   533.6    .045       0   568.6      .1       0
Bank Sta=533.6,568.6
XS Rating Curve= 0 ,0
Exp/Cntr=0.3,0.1

Type RM Length L Ch R = 1 ,24551.9 ,283.5,282.5,282.4
XS GIS Cut Line= 3
     1830548.002       348242.05     1830459.587      348418.879
      1830124.58      349234.347
#Sta/Elev= 30
       0 1100.64     9.9 1093.84    39.5 1068.02    69.2 1044.94    98.8 1023.62
   108.7 1022.32   118.6 1015.68   158.2   981.5     168  973.86   197.7  956.17
   207.6  954.66   217.5  951.65   227.4  949.81   296.8  945.04   425.5  945.18
   455.2  941.41   472.2  940.66   475.1  940.62   507.2  941.03   514.7  941.22
   544.4  945.36   593.9  954.04   613.7  956.04   683.1  968.87   702.9  970.92
   801.9  977.46     901  981.59   930.7   981.5  1019.9  983.89  1079.3   986.9
#Mann= 3 , 0 , 0
       0      .1       0   472.2    .045       0   507.2     .06       0
Bank Sta=472.2,507.2
XS Rating Curve= 0 ,0
Exp/Cntr=0.3,0.1

Type RM Length L Ch R = 1 ,24269.3 ,372.6,355.4,337.7
XS GIS Cut Line= 3
     1830365.074      348098.756     1830112.025      348589.612
     1830072.451      349192.802
#Sta/Elev= 30
       0 1149.38    19.7 1134.77    29.6  1125.7    39.4 1119.09    49.3 1115.32
   128.2 1055.55   138.1    1049   147.9 1047.65   177.5 1025.36   197.2 1008.47
   246.5  971.89   266.3  964.57     286  950.92   295.8  946.52   335.3   941.1
   364.9  940.12   406.2   940.2   441.2  941.16   552.2  951.36   621.6  953.72
   710.8  954.27   760.4  958.94   819.8  969.48   859.4  969.27   899.1  966.62
   948.6  967.71   968.4  970.17  1027.9  981.52  1097.3  988.87  1156.7  991.99
#Mann= 3 , 0 , 0
       0      .1       0   406.2    .045       0   441.2     .06       0
Bank Sta=406.2,441.2
XS Rating Curve= 0 ,0
Exp/Cntr=0.3,0.1

Type RM Length L Ch R = 1 ,23913.8 ,302,286.5,270.7
XS GIS Cut Line= 3
     1829827.086      347844.121     1829895.939      348330.587
     1830007.743      349179.137
#Sta/Elev= 30
       0 1206.33    68.8 1175.45    78.6 1172.21    88.4 1171.29   117.9 1158.91
   137.6 1149.33     167 1132.01   176.9 1131.54   196.5 1118.49   265.3  1067.3
   275.1 1064.69     285 1059.64   363.6   993.3   373.4  988.34   383.2  985.63
   432.4  946.15   442.2  941.73   461.8   939.3   473.8   939.3   508.8  939.33
   541.1  940.02   740.1  952.22   879.4  954.15  1018.8  964.32  1058.6  964.94
  1128.2  979.84    1188  988.74  1247.7  993.66  1307.4    1001  1347.2  1003.2
#Mann= 3 , 0 , 0
       0      .1       0   473.8    .045       0   508.8      .1       0
Bank Sta=473.8,508.8
XS Rating Curve= 0 ,0
Exp/Cntr=0.3,0.1

Type RM Length L Ch R = 1 ,23627.3 ,339.3,323.1,307
XS GIS Cut Line= 3
     1829335.686      347994.197     1829730.926      348553.026
     1829935.265      349197.712
#Sta/Elev= 30
       0 1283.17     9.9 1278.52     119 1206.07     129 1204.28   238.1 1118.04
   257.9  1109.2   277.8 1090.74   297.6 1064.21   357.1  992.02     367  984.23
     377  979.29   396.8  956.11   406.7  946.79   416.6  941.34   436.5  937.03
   473.3  936.04   505.9  935.71   508.3  935.75   674.6   940.5     774  948.98
  1062.4  959.43  1072.4  960.41  1102.2  975.19  1112.1  978.77  1122.1  979.19
  1201.6 1011.02  1221.5 1016.79  1301.1 1020.32    1321 1024.58  1360.8 1019.08
#Mann= 3 , 0 , 0
       0      .1       0   473.3    .045       0   508.3      .1       0
Bank Sta=473.3,508.3
XS Rating Curve= 0 ,0
Exp/Cntr=0.3,0.1