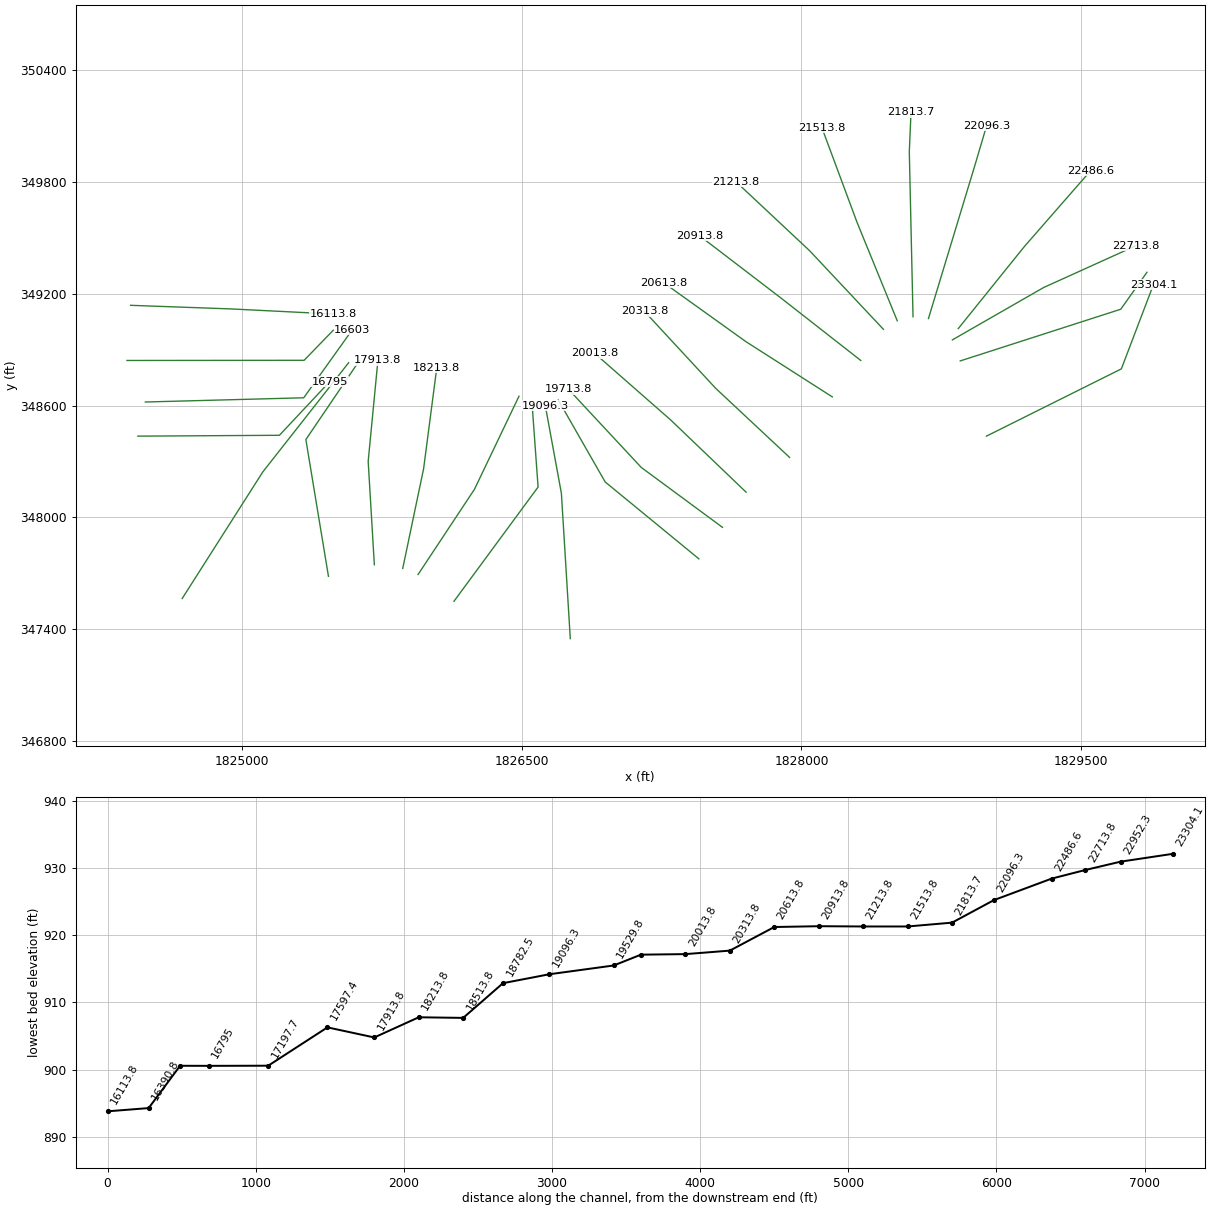
HEC-RAS study ClrFrk1.prj: ClrFrk1

--- ClrFrk1.g01 (geometry) --- (continued)

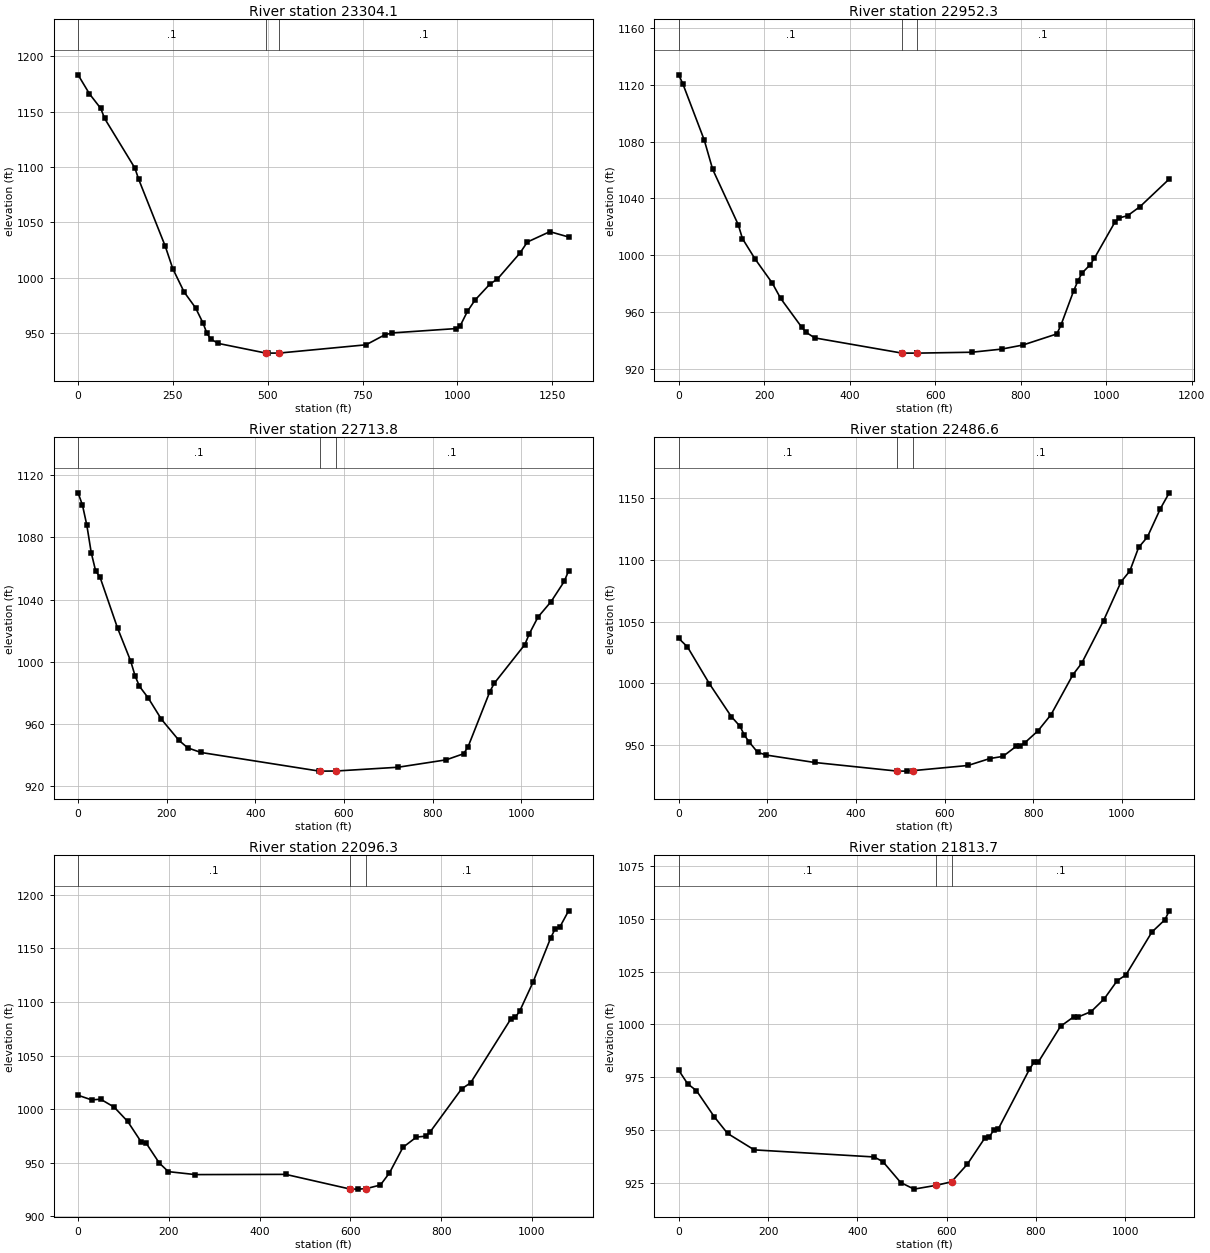
Type RM Length L Ch R = 1 ,23304.1 ,356.7,351.7,346.8
XS GIS Cut Line= 3
     1828991.801      348435.807     1829715.682       348796.93
     1829887.888      349249.437
#Sta/Elev= 30
       0 1183.14      30    1166    59.9 1152.77    69.9 1143.84   149.8 1099.02
   159.8 1088.88   229.7 1028.66   249.7 1008.28   279.6  987.21   309.6  973.02
   329.6   959.1   339.6     950   349.6  944.83   369.5  940.86   495.3  932.12
   499.4   932.1   530.3  932.16     759   939.6     809  948.69   828.7  950.35
   996.7  954.25  1006.6  956.21  1026.3  969.72  1046.1  979.82  1085.6  994.37
  1105.4  998.89  1164.7 1022.28  1184.4 1032.33  1243.7 1041.67  1293.1 1036.86
#Mann= 3 , 0 , 0
       0      .1       0   495.3    .045       0   530.3      .1       0
Bank Sta=495.3,530.3
XS Rating Curve= 0 ,0
Exp/Cntr=0.3,0.1

Type RM Length L Ch R = 1 ,22952.3 ,231.8,238.6,242.3
XS GIS Cut Line= 3
     1828851.707      348839.703     1829712.633      349117.053
     1829852.925      349315.363
#Sta/Elev= 30
       0 1127.03     9.9  1120.5    59.6  1081.2    79.5 1060.39   139.2 1021.48
   149.1 1011.62   178.9  997.15   218.7  980.37   238.6  969.44   288.2  949.01
   298.2  945.57   318.1  941.67   521.9  930.97   556.6  930.94   556.9  930.94
   685.8  931.57   755.4  933.78   805.1  936.65   884.6  944.48   894.6  951.05
   923.9  974.89   933.6  981.73   943.4  987.35   962.8  993.34   972.5  997.89
  1021.1 1023.66  1030.8 1026.21  1050.2 1027.82  1079.4 1034.25  1147.4 1053.61
#Mann= 3 , 0 , 0
       0      .1       0   521.9    .045       0   556.9      .1       0
Bank Sta=521.9,556.9
XS Rating Curve= 0 ,0
Exp/Cntr=0.3,0.1

Type RM Length L Ch R = 1 ,22713.8 ,215.1,227.2,242.5
XS GIS Cut Line= 3
     1828809.569      348952.536     1829298.921      349233.529
     1829793.167      349457.469
#Sta/Elev= 30
       0  1108.6     9.9 1100.73    19.8 1087.76    29.7 1070.14    39.6 1058.45
    49.5 1054.42    89.1 1021.66   118.8  1000.4   128.7  990.89   138.6  984.21
   158.4  976.69   188.1  963.03   227.7  949.46   247.5  944.65   277.2   941.7
   544.5   929.7   546.8   929.7   581.8  929.77   722.1   932.2   830.7  936.96
   870.1  940.89     880  945.32   929.3  980.88   939.2  986.18  1008.2 1011.07
  1018.1  1017.9  1037.8 1028.72  1067.4 1038.68    1097 1051.62  1106.9 1058.46
#Mann= 3 , 0 , 0
       0      .1       0   546.8    .045       0   581.8      .1       0
Bank Sta=546.8,581.8
XS Rating Curve= 0 ,0
Exp/Cntr=0.3,0.1

Type RM Length L Ch R = 1 ,22486.6 ,376.7,390.1,403.4
XS GIS Cut Line= 3
     1828840.994       349013.02      1829194.49       349452.07
     1829551.463      349861.081
#Sta/Elev= 30
       0 1036.31    19.8 1029.34    69.2  999.47   118.7  972.75   138.4  964.82
   148.3  957.56   158.2  952.48     178   943.7   197.8  941.47   306.6  935.45
   492.5  928.46   514.2  928.42   527.5  928.78   652.5  933.01   701.9  938.65
   731.5   940.4   761.1  948.54     771  949.08   780.8  951.48   810.4  961.14
     840  974.37   889.4 1006.82   909.1 1016.11   958.5 1050.81     998 1082.36
  1017.7 1091.04  1037.5 1110.19  1057.2 1118.61  1086.8 1141.85  1106.6 1154.59
#Mann= 3 , 0 , 0
       0      .1       0   492.5    .045       0   527.5      .1       0
Bank Sta=492.5,527.5
XS Rating Curve= 0 ,0
Exp/Cntr=0.3,0.1

Type RM Length L Ch R = 1 ,22096.3 ,273.2,282.7,292.3
XS GIS Cut Line= 3
     1828681.187      349067.206     1828929.094      349885.348
     1828993.118      350101.812
#Sta/Elev= 30
       0 1012.89    29.8 1008.57    49.7  1009.2    79.5 1001.81   109.3  988.43
   139.2  969.18   149.1  968.73   178.9  949.62   198.8  941.56   258.4  938.79
   457.3     939     599  925.31   616.3  925.22     634  925.62     666  929.04
   685.9   940.3   715.7  964.25   745.5  973.86   765.4  974.62   775.4  978.54
   844.9 1018.85   864.7 1024.47     953 1083.94   962.8 1085.55   972.6 1091.24
  1002.1 1118.36  1041.4 1160.12  1051.2 1168.45    1061 1169.77  1080.6 1185.14
#Mann= 3 , 0 , 0
       0      .1       0     599    .045       0     634      .1       0
Bank Sta=599,634
XS Rating Curve= 0 ,0
Exp/Cntr=0.3,0.1

Type RM Length L Ch R = 1 ,21813.7 ,287.9,299.9,310.8
XS GIS Cut Line= 3
     1828598.435      349076.722     1828578.483      349961.568
     1828587.629      350174.983
#Sta/Elev= 30
       0  978.23    19.9  971.81    39.8  968.54    79.6  956.18   109.4  948.28
   169.1  940.48   437.6  937.12   457.4  934.89   497.2     925   527.1  921.87
     576  923.65     611  925.32   646.4  933.66   686.2  946.27   696.1  946.72
   706.1  950.05     716  950.48   785.6  978.67   795.6  981.94   805.5  982.13
   855.2  999.04   885.1 1003.61   894.8 1003.48   923.9 1006.06     953 1012.04
   982.2  1020.7  1001.6  1023.4  1059.8 1043.72    1089 1049.58  1098.7  1053.8
#Mann= 3 , 0 , 0
       0      .1       0     576    .045       0     611      .1       0
Bank Sta=576,611
XS Rating Curve= 0 ,0
Exp/Cntr=0.3,0.1

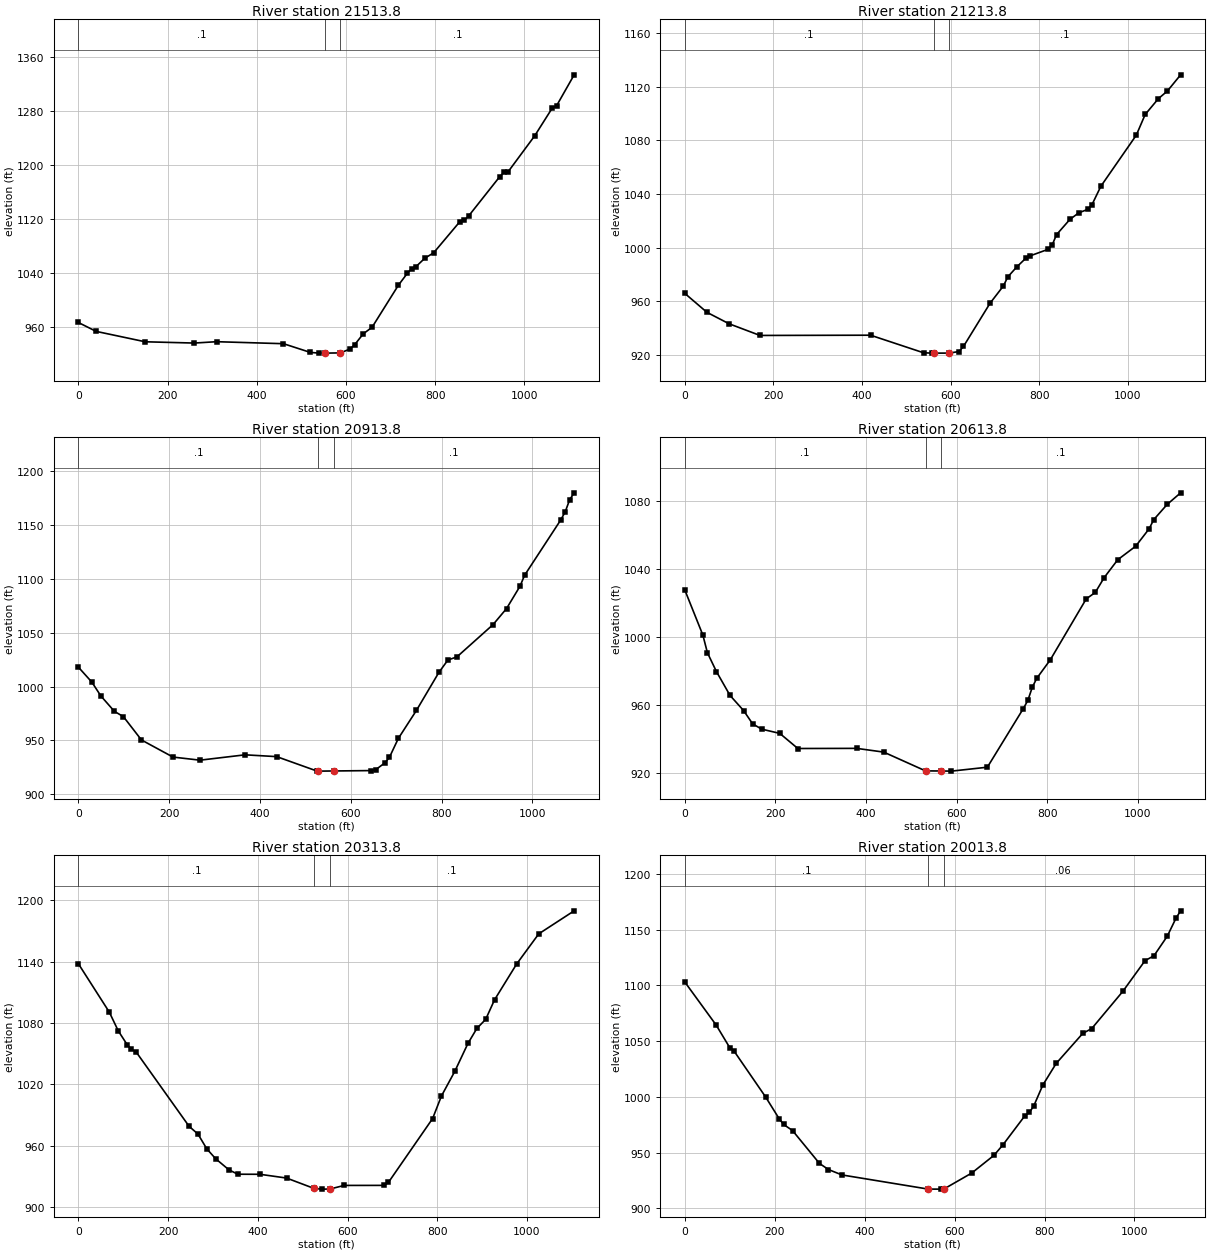
Type RM Length L Ch R = 1 ,21513.8 ,288,300,315.1
XS GIS Cut Line= 3
     1828513.835      349054.998     1828298.396      349582.772
     1828109.777      350090.632
#Sta/Elev= 30
       0  966.69      40   953.5     150  938.11     260  936.21     310  938.23
     460  935.26     520  922.41     540   921.3   552.6   921.3   587.6  921.65
   609.4  927.45   619.3  933.53     639  949.95   658.7  959.64   717.8 1022.02
   737.5 1039.32   747.4  1046.6   757.2 1049.45   776.9 1061.89   796.6  1069.8
   855.7  1116.2   865.6 1118.03   875.4 1124.65   944.4 1182.25   954.2 1188.99
   964.1 1190.29  1023.2 1243.07  1062.6 1284.25  1072.4 1287.76  1111.8 1333.54
#Mann= 3 , 0 , 0
       0      .1       0   552.6    .045       0   587.6      .1       0
Bank Sta=552.6,587.6
XS Rating Curve= 0 ,0
Exp/Cntr=0.3,0.1

Type RM Length L Ch R = 1 ,21213.8 ,294.9,300,303.4
XS GIS Cut Line= 3
     1828439.781      349009.229     1828043.601      349431.273
     1827649.583      349800.545
#Sta/Elev= 30
       0  965.87    49.9  951.75    99.8  943.21   169.7  934.49   419.2  934.67
   538.9  921.55   558.9   921.3   561.4   921.3   596.4  921.32   618.9   922.5
   628.9   926.3   688.9  958.54   718.9  971.38   728.9  978.15   748.9  985.52
   768.9  991.89   778.9  993.81   818.9  998.62   828.9 1001.86   838.9 1009.67
   868.9 1020.99   888.9 1025.92   908.9 1028.48   918.9 1032.05   938.9 1045.76
  1018.9 1083.89  1038.9  1099.3  1068.9 1111.17  1088.9 1116.76  1118.9 1128.88
#Mann= 3 , 0 , 0
       0      .1       0   561.4    .045       0   596.4      .1       0
Bank Sta=561.4,596.4
XS Rating Curve= 0 ,0
Exp/Cntr=0.3,0.1

Type RM Length L Ch R = 1 ,20913.8 ,296.9,300,301
XS GIS Cut Line= 3
     1828318.198      348842.125     1827888.235      349178.636
     1827454.679       349510.58
#Sta/Elev= 30
       0 1018.05    29.8 1004.06    49.6  991.24    79.4  976.92    99.3  971.97
     139  950.31   208.5   934.4     268  931.52   367.3   936.5   436.8  934.82
   526.1  921.34   528.5  921.34   563.5  921.49   645.3  921.85   655.2  922.75
   675.1  929.01     685  934.04   704.8  951.77   744.6  977.77   794.2 1013.21
     814 1024.64   833.9 1027.56   913.3 1057.52   943.1 1072.46   972.9 1093.36
   982.8 1103.38  1062.2 1154.67  1072.2 1162.32  1082.1 1173.62    1092 1180.05
#Mann= 3 , 0 , 0
       0      .1       0   528.5    .045       0   563.5      .1       0
Bank Sta=528.5,563.5
XS Rating Curve= 0 ,0
Exp/Cntr=0.3,0.1

Type RM Length L Ch R = 1 ,20613.8 ,305.9,300,293.4
XS GIS Cut Line= 3
     1828165.682      348646.597     1827703.382      348942.355
     1827259.971      349260.099
#Sta/Elev= 30
       0 1027.89    39.9 1001.29    49.9  990.93    69.8  979.84    99.8  965.79
   129.7   956.9   149.7  949.06   169.6  945.94   209.6  943.44   249.5  934.54
   379.2  934.62     439  932.42   531.3  921.36   566.3   921.3   588.5  921.22
   667.8  923.53   747.2  958.08   757.1  962.84     767  970.67   776.9  975.89
   806.7  986.76     886 1022.63   905.9  1026.4   925.7  1035.2   955.5 1045.66
   995.1 1053.63  1024.9 1063.92  1034.8 1069.22  1064.6 1078.24  1094.3 1085.06
#Mann= 3 , 0 , 0
       0      .1       0   531.3    .045       0   566.3      .1       0
Bank Sta=531.3,566.3
XS Rating Curve= 0 ,0
Exp/Cntr=0.3,0.1

Type RM Length L Ch R = 1 ,20313.8 ,300.4,300,303.4
XS GIS Cut Line= 3
     1827936.552      348321.717     1827539.896      348692.805
     1827158.231       349105.32
#Sta/Elev= 30
       0    1138    69.1 1090.61    88.9 1072.43   108.6 1059.01   118.5  1054.2
   128.4 1052.02   246.9  979.07   266.6  971.55   286.4  957.02   306.2  947.37
   335.8  936.52   355.5  932.28   404.9   932.2   464.2  928.53   525.7  918.34
   543.2  917.71   560.7  917.78   592.5  921.33   681.2  921.37   691.1  924.22
   789.7  986.68   809.4 1008.74     839 1032.67   868.5 1060.12   888.3 1074.71
     908 1083.62   927.7 1102.67     977 1137.68  1026.3 1167.15  1105.2 1189.64
#Mann= 3 , 0 , 0
       0      .1       0   525.7    .045       0   560.7      .1       0
Bank Sta=525.7,560.7
XS Rating Curve= 0 ,0
Exp/Cntr=0.3,0.1

Type RM Length L Ch R = 1 ,20013.8 ,295.8,300,296.6
XS GIS Cut Line= 3
     1827703.193      348135.395     1827299.558      348522.125
     1826890.833      348880.677
#Sta/Elev= 30
       0    1103    69.9 1064.27    99.8 1044.22   109.8 1040.88   179.7  999.88
   209.6  980.51   219.6  975.24   239.6  969.73   299.5  940.23   319.4  934.79
   349.4  929.92   541.5  917.21   568.9  917.19   576.5  917.35   638.1  931.61
   687.5  947.48   707.3  956.78   756.7  983.19   766.6  985.96   776.5   992.2
   796.2 1010.51   825.9 1029.94   885.2 1056.94     905 1061.21   974.2 1094.61
  1023.6 1122.16  1043.4 1126.53    1073 1144.08  1092.8 1160.58  1102.7 1166.84
#Mann= 3 , 0 , 0
       0      .1       0   541.5    .045       0   576.5     .06       0
Bank Sta=541.5,576.5
XS Rating Curve= 0 ,0
Exp/Cntr=0.3,0.1

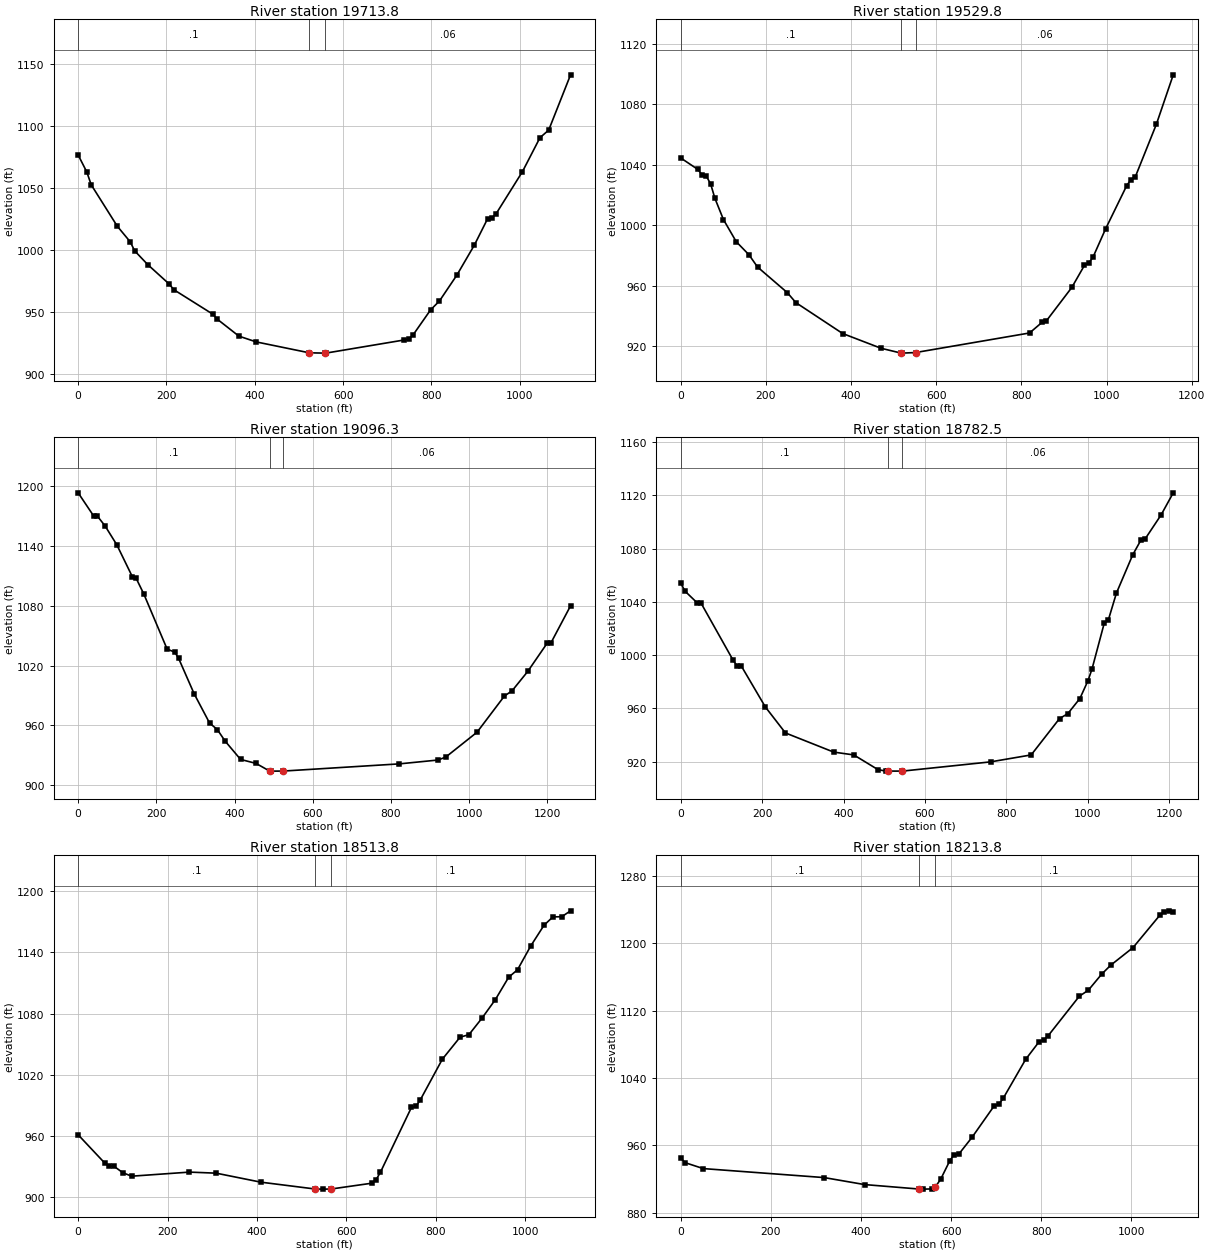
Type RM Length L Ch R = 1 ,19713.8 ,185.7,184,188.3
XS GIS Cut Line= 3
     1827576.393      347946.673     1827141.102      348267.977
     1826749.906      348688.238
#Sta/Elev= 30
       0 1076.58    19.7  1062.8    29.5 1052.63    88.5 1019.32     118 1006.65
   127.9  999.47   157.4  988.43   206.6  972.58   216.4  968.23     305  948.45
   314.8   944.5     364   930.8   403.3  926.14   523.5  917.36   558.5  917.12
   560.8  917.11     739  927.73   748.9   928.6   758.8  931.89   798.4  952.02
   818.2  959.04   857.8  979.94   897.4  1004.1   927.1 1025.13     937 1025.94
   946.9 1029.47  1006.3 1063.23  1045.9 1090.51  1065.7 1096.63  1115.2 1141.11
#Mann= 3 , 0 , 0
       0      .1       0   523.5    .045       0   558.5     .06       0
Bank Sta=523.5,558.5
XS Rating Curve= 0 ,0
Exp/Cntr=0.3,0.1

Type RM Length L Ch R = 1 ,19529.8 ,460.5,433.5,406.5
XS GIS Cut Line= 3
     1827449.969      347777.484     1826947.379       348190.22
     1826696.127       348629.68
#Sta/Elev= 30
       0 1044.56      40 1037.01      50 1033.34      60 1032.53      70 1027.39
      80 1017.91     100 1003.89   130.1  989.23   160.1  980.53   180.1  972.48
   250.1  955.51   270.1  948.93   380.2  928.45   470.2  918.72   516.6  915.57
   520.3   915.5   551.6   915.9   819.1  928.83   848.9  935.98   858.8  936.92
   918.3  958.94   948.1  973.62     958  975.02     968  978.91   997.8  997.77
  1047.4 1026.38  1057.3 1030.26  1067.2 1031.91  1116.9 1066.85  1156.6 1099.61
#Mann= 3 , 0 , 0
       0      .1       0   516.6    .045       0   551.6     .06       0
Bank Sta=516.6,551.6
XS Rating Curve= 0 ,0
Exp/Cntr=0.3,0.1

Type RM Length L Ch R = 1 ,19096.3 ,336.5,313.8,291.1
XS GIS Cut Line= 3
      1826760.36      347349.408     1826712.622      348129.244
     1826626.318      348599.596
#Sta/Elev= 30
       0 1193.11    39.6 1169.94    49.4 1169.68    69.2 1159.72    98.9    1141
   138.5  1109.1   148.4 1107.39   168.1 1091.57   227.5 1036.52   247.2  1033.4
   257.1 1027.09   296.7  991.71   336.2  962.37     356  955.83   375.8  944.34
   415.4  925.93   454.9  921.95   489.6  914.31   494.5   914.2   524.6  914.26
   821.2  921.46   920.8  925.34   940.7   928.4  1020.4  953.24  1090.1  989.36
  1110.1  994.79  1149.9 1014.07  1199.7 1042.44  1209.7 1042.99  1259.5 1079.85
#Mann= 3 , 0 , 0
       0      .1       0   489.6    .045       0   524.6     .06       0
Bank Sta=489.6,524.6
XS Rating Curve= 0 ,0
Exp/Cntr=0.3,0.1

Type RM Length L Ch R = 1 ,18782.5 ,267.1,268.7,274.9
XS GIS Cut Line= 3
     1826136.377      347549.653     1826587.622      348162.781
      1826555.25       348610.65
#Sta/Elev= 30
       0 1053.97     9.9  1048.1    39.6 1039.39    49.4 1039.16   128.5  996.13
   138.4  991.78   148.3  991.97   207.6   961.1   257.1  941.54   375.7  927.16
   425.1  925.04   484.4  914.02   504.2  912.87   509.7  912.91   544.7  912.89
   761.3  919.82   861.1  925.04   930.9  952.38   950.9  955.96   980.8  967.38
  1000.8  980.83  1010.8  989.73  1040.7 1024.01  1050.7 1026.31  1070.6 1046.53
  1110.5 1075.16  1130.5 1086.19  1140.5 1086.92  1180.4 1105.24  1210.3 1121.85
#Mann= 3 , 0 , 0
       0      .1       0   509.7    .045       0   544.7     .06       0
Bank Sta=509.7,544.7
XS Rating Curve= 0 ,0
Exp/Cntr=0.3,0.1

Type RM Length L Ch R = 1 ,18513.8 ,287.7,300,310.2
XS GIS Cut Line= 3
     1825944.069      347693.648      1826246.29      348150.547
     1826485.238      348650.188
#Sta/Elev= 30
       0  961.02    59.8  933.13    69.7  930.38    79.7  930.29    99.6  923.91
   119.5   920.4     249  924.41   308.8  923.37   408.4  914.56   530.3  907.82
   547.8  907.71   565.3  907.79   656.6   913.5   666.5  916.92   676.4  924.41
   745.6  987.89   755.5  988.83   765.4  995.24   814.8 1035.23   854.4 1056.82
   874.2 1059.26   903.8 1075.68   933.5 1093.77   963.2 1115.67     983    1123
  1012.6 1146.38  1042.3  1166.7  1062.1 1174.84  1081.9 1175.03  1101.6  1180.8
#Mann= 3 , 0 , 0
       0      .1       0   530.3    .045       0   565.3      .1       0
Bank Sta=530.3,565.3
XS Rating Curve= 0 ,0
Exp/Cntr=0.3,0.1

Type RM Length L Ch R = 1 ,18213.8 ,291.3,300,301.1
XS GIS Cut Line= 3
     1825861.763       347725.98     1825973.704      348261.335
     1826044.309      348802.661
#Sta/Elev= 30
       0  944.26     9.9  939.19    49.7  932.23   318.2  921.52   407.7  913.22
   529.4  907.87     537   907.8   556.9  908.02   564.4  910.11   576.7  919.63
   596.6  941.25   606.5  948.91   616.4  949.11   646.2  969.38   695.8 1007.14
   705.7 1008.66   715.7 1016.05   765.3 1062.16   795.1 1083.08     805 1085.32
   814.9    1090   884.4 1137.23   904.3  1144.3     934 1163.47   953.9 1174.02
  1003.5 1195.01  1063.1 1233.55    1073 1237.77  1082.9 1238.75  1092.8 1237.33
#Mann= 3 , 0 , 0
       0      .1       0   529.4    .045       0   564.4      .1       0
Bank Sta=529.4,564.4
XS Rating Curve= 0 ,0
Exp/Cntr=0.3,0.1

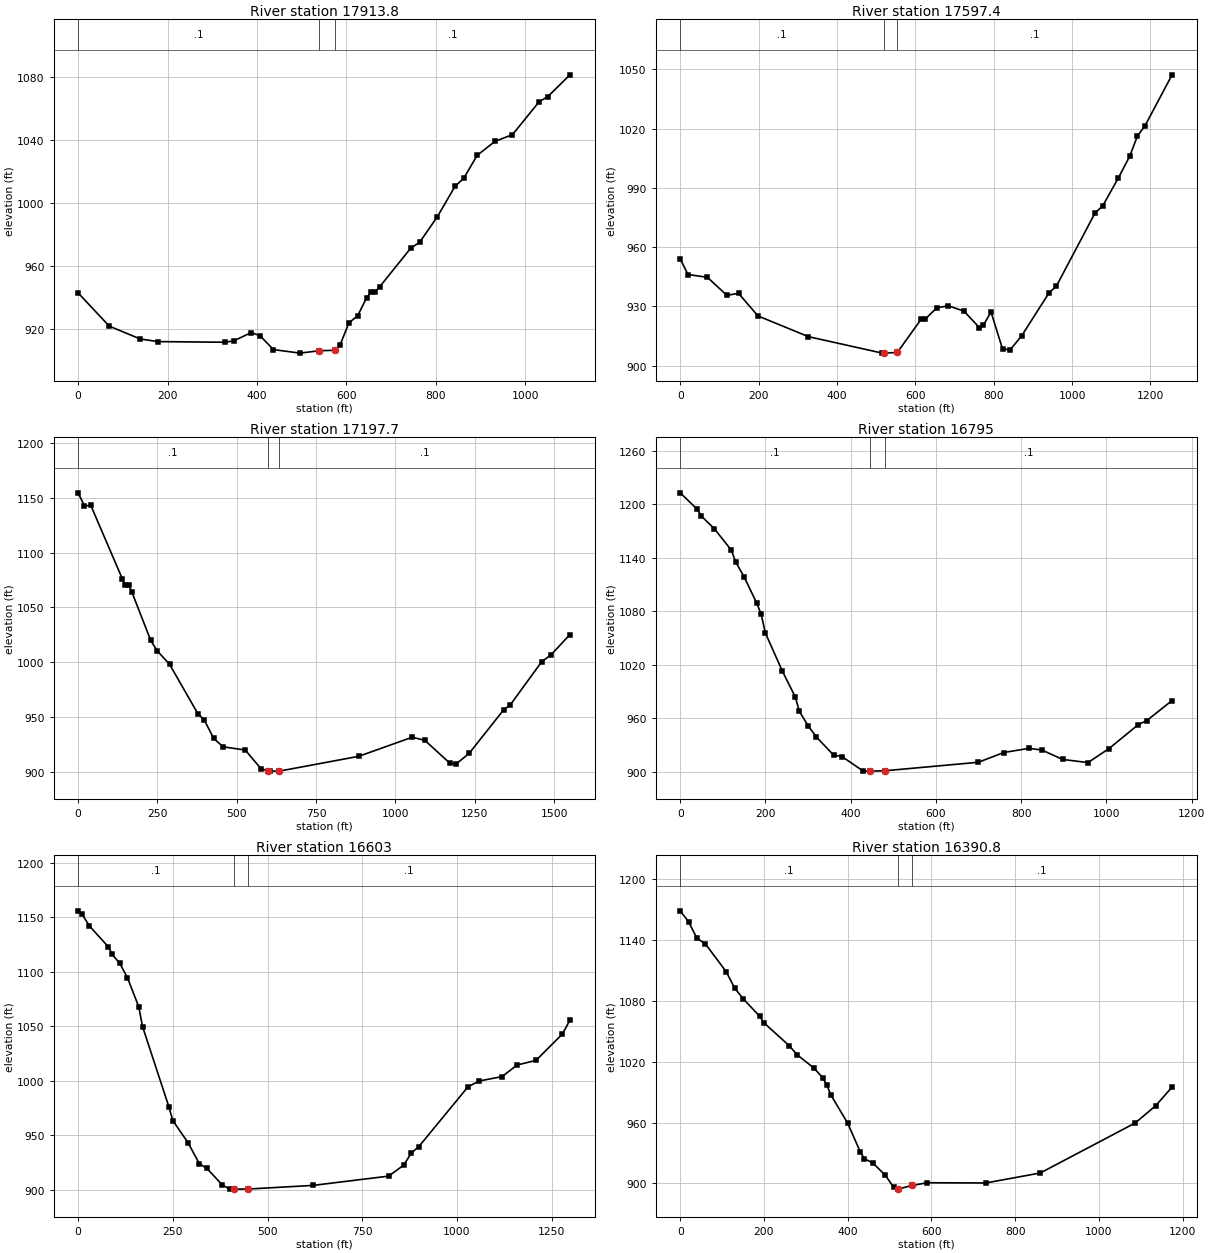
Type RM Length L Ch R = 1 ,17913.8 ,313.6,316.4,324.3
XS GIS Cut Line= 3
     1825709.501       347745.81     1825676.445      348300.918
      1825728.62      348842.536
#Sta/Elev= 30
       0  943.03    69.5  921.96     139  913.76   178.7  912.12   327.7  911.71
   347.6  912.52   387.3  917.86   407.1  915.79   436.9  907.03   496.5   904.8
   538.6   906.3   573.6  906.61   585.8  909.88   605.6  923.95   625.3  928.56
   645.1  939.82     655  943.54   664.9  943.91   674.8  947.02   744.1  971.47
   763.8  975.11   803.4  991.34     843 1010.65   862.8 1015.89   892.5 1030.32
     932 1039.17   971.6 1043.52    1031 1064.32  1050.8 1067.72  1100.2 1081.48
#Mann= 3 , 0 , 0
       0      .1       0   538.6    .045       0   573.6      .1       0
#XS Ineff= 2 , 0
          387.32  917.83
Permanent Ineff=
       F       F
Bank Sta=538.6,573.6
XS Rating Curve= 0 ,0
Exp/Cntr=0.3,0.1

Type RM Length L Ch R = 1 ,17597.4 ,423.7,399.7,375.7
XS GIS Cut Line= 3
      1825463.38       347683.74     1825342.191      348417.736
     1825629.027      348840.985
#Sta/Elev= 30
       0  954.05    19.8  946.12    69.4   944.7     119  935.57   148.8  936.58
   198.4  925.14   327.3  914.64   515.8   906.3   518.9   906.3   553.9  906.62
     615  923.51   624.9  923.48   654.7  929.25   684.4  930.27   724.1  927.56
   763.6  919.18   773.4  920.33   793.1   927.2   822.6  908.34   842.3  908.05
   871.8  915.19   940.6  936.66   960.2  940.33  1058.6  977.28  1078.2  980.89
  1117.6  994.86  1147.1 1006.04  1166.7 1016.24  1186.4 1021.59  1255.2 1047.28
#Mann= 3 , 0 , 0
       0      .1       0   518.9    .045       0   553.9      .1       0
Bank Sta=518.9,553.9
XS Rating Curve= 0 ,0
Exp/Cntr=0.3,0.1

Type RM Length L Ch R = 1 ,17197.7 ,434.9,402.8,370.6
XS GIS Cut Line= 3
     1824679.079      347564.837     1825111.245      348243.955
     1825571.663       348830.03
#Sta/Elev= 30
       0 1154.67    19.9 1142.71    39.8 1143.28   139.1 1076.29   149.1 1070.34
     159 1070.26   168.9 1064.48   228.6 1020.07   248.4  1010.7   288.2  998.12
   377.6  952.92   397.5  947.34   427.3  930.45   457.1   922.8   526.7  919.85
   576.4  902.81   599.1  900.62   606.2   900.6   634.1  900.62   884.5  914.12
  1053.4  931.58  1093.2  928.62  1172.6   907.6  1192.5  907.41  1232.3  916.75
  1341.6  956.69  1361.4  960.79  1460.8 1000.36  1490.6 1006.81  1550.3 1025.26
#Mann= 3 , 0 , 0
       0      .1       0   599.1    .045       0   634.1      .1       0
Bank Sta=599.1,634.1
XS Rating Curve= 0 ,0
Exp/Cntr=0.3,0.1

Type RM Length L Ch R = 1 ,16795   ,191.3,192,192.7
XS GIS Cut Line= 3
     1824441.273      348436.029     1825200.422      348440.602
      1825470.24      348728.713
#Sta/Elev= 30
       0 1212.86      40 1194.34    49.9 1186.59    79.9 1172.64   119.9 1148.58
   129.9 1135.45   149.8 1118.71   179.8 1088.73   189.8 1076.76   199.8  1055.5
   239.7  1012.7   269.7  984.05   279.7  967.59   299.7  951.67   319.6  938.75
   359.6  918.71   379.6  916.87   429.5  900.58   444.3   900.6   479.3  900.94
   699.2   910.5   759.2  921.48   818.4  926.15     848  924.32   897.3   913.7
   956.5  910.13  1005.9  925.88  1074.9  952.84  1094.7  957.34  1153.9  979.81
#Mann= 3 , 0 , 0
       0      .1       0   444.3    .045       0   479.3      .1       0
Bank Sta=444.3,479.3
XS Rating Curve= 0 ,0
Exp/Cntr=0.3,0.1

Type RM Length L Ch R = 1 ,16603   ,213,212.2,211.3
XS GIS Cut Line= 3
     1824481.317      348619.179     1825330.758      348641.822
     1825591.633      349007.144
#Sta/Elev= 30
       0 1156.06      10 1153.17      30 1142.07      80 1122.91      90 1116.06
     110 1107.78     130 1094.81     160 1068.06     170 1049.87   239.9  975.86
   249.9  963.58   289.9  943.37   319.9  924.01   339.9   919.6   379.9  904.72
   399.9  900.59   412.4   900.6   447.4  900.64   619.8     904   819.8  912.52
   859.7  922.64   879.7  933.74   899.6  939.67  1029.3  994.49  1059.2   999.9
  1119.1 1003.85    1159 1014.54  1208.9 1018.78  1278.7 1043.03  1298.6 1055.78
#Mann= 3 , 0 , 0
       0      .1       0   412.4    .045       0   447.4      .1       0
Bank Sta=412.4,447.4
XS Rating Curve= 0 ,0
Exp/Cntr=0.3,0.1

Type RM Length L Ch R = 1 ,16390.8 ,278.2,277,275.3
XS GIS Cut Line= 3
     1824382.926      348842.083     1825333.044      348843.043
     1825489.471      349004.541
#Sta/Elev= 30
       0 1168.74      20 1157.97      40 1141.62      60  1136.2     110 1108.62
     130 1092.56     150 1082.23     190 1064.68     200 1058.34     260 1035.85
     280 1026.56     320  1013.5     340 1004.21     350  997.25     360   987.1
     400  959.33     430  931.16     440  924.25   460.1  920.14   490.1  907.88
   510.1     896   519.5   894.4   520.1   894.3   554.5  898.01   590.1  900.59
   730.1  900.37   860.1  910.21    1087  959.56  1135.8  976.52    1175  994.93
#Mann= 3 , 0 , 0
       0      .1       0   519.5    .045       0   554.5      .1       0
Bank Sta=519.5,554.5
XS Rating Curve= 0 ,0
Exp/Cntr=0.3,0.1

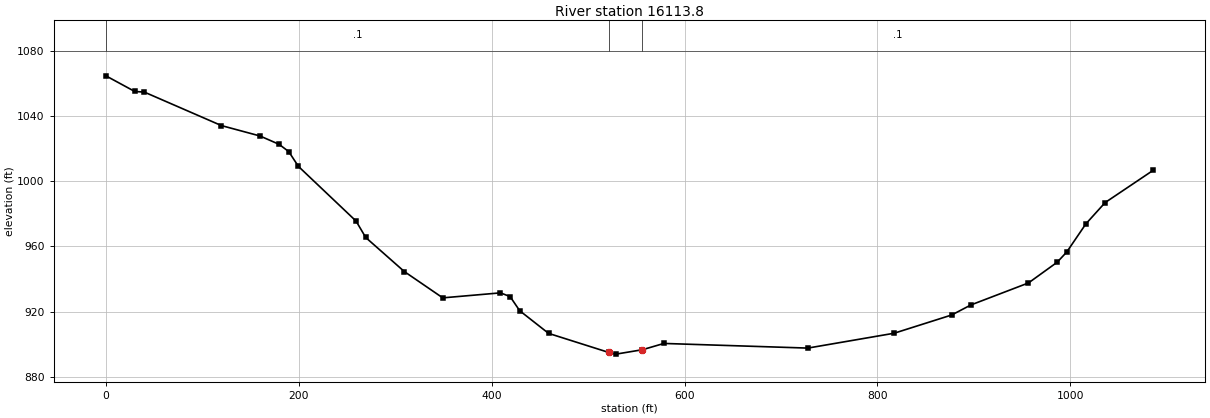
Type RM Length L Ch R = 1 ,16113.8 ,175.3,176.3,177.7
XS GIS Cut Line= 3
     1824402.401      349138.013      1824940.92      349118.688
     1825487.209      349091.325
#Sta/Elev= 30
       0  1064.9    29.9 1055.29    39.9 1054.89   119.8 1034.31   159.7 1027.94
   179.6 1022.79   189.6 1018.32   199.6 1009.23   259.4  975.61   269.4  965.53
   309.4   944.6   349.3  928.41   409.1  931.48   419.1  929.21   429.1  920.49
     459  906.58   521.4  894.86   528.9  893.82   556.4  896.54   578.6  900.39
   727.8  897.53   817.3  906.66     877  917.88   896.9  924.05   956.6  937.58
   986.4  950.32   996.3   956.6  1016.2  973.94  1036.1  986.98  1085.8 1006.77
#Mann= 3 , 0 , 0
       0      .1       0   521.4    .045       0   556.4      .1       0
Bank Sta=521.4,556.4
XS Rating Curve= 0 ,0
Exp/Cntr=0.3,0.1