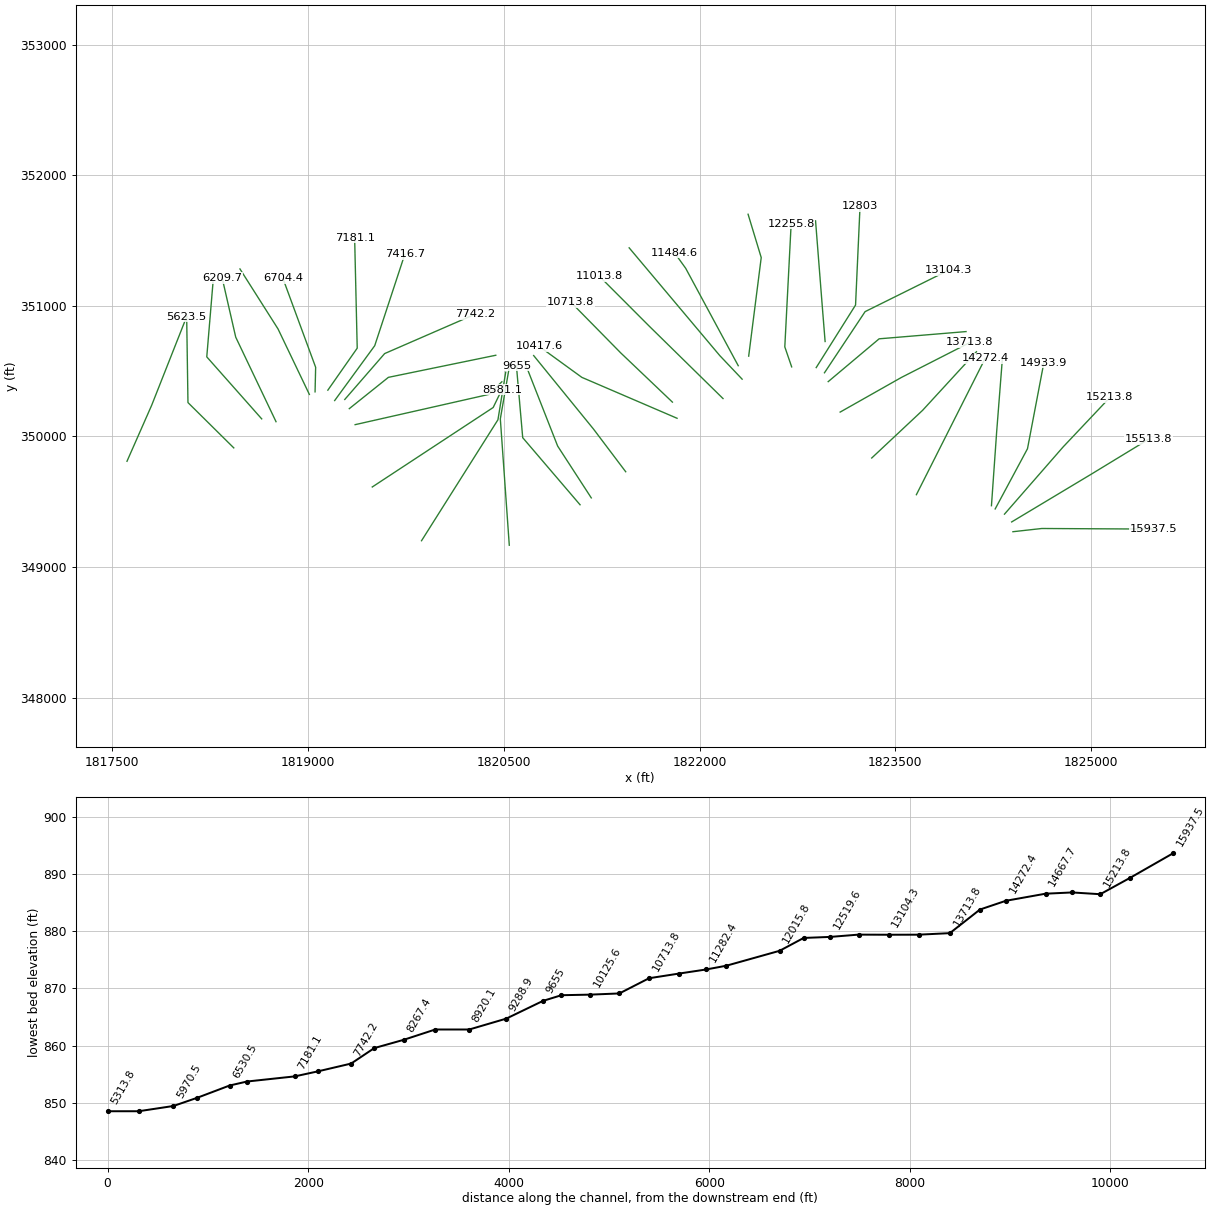
HEC-RAS study ClrFrk1.prj: ClrFrk1

--- ClrFrk1.g01 (geometry) --- (continued)

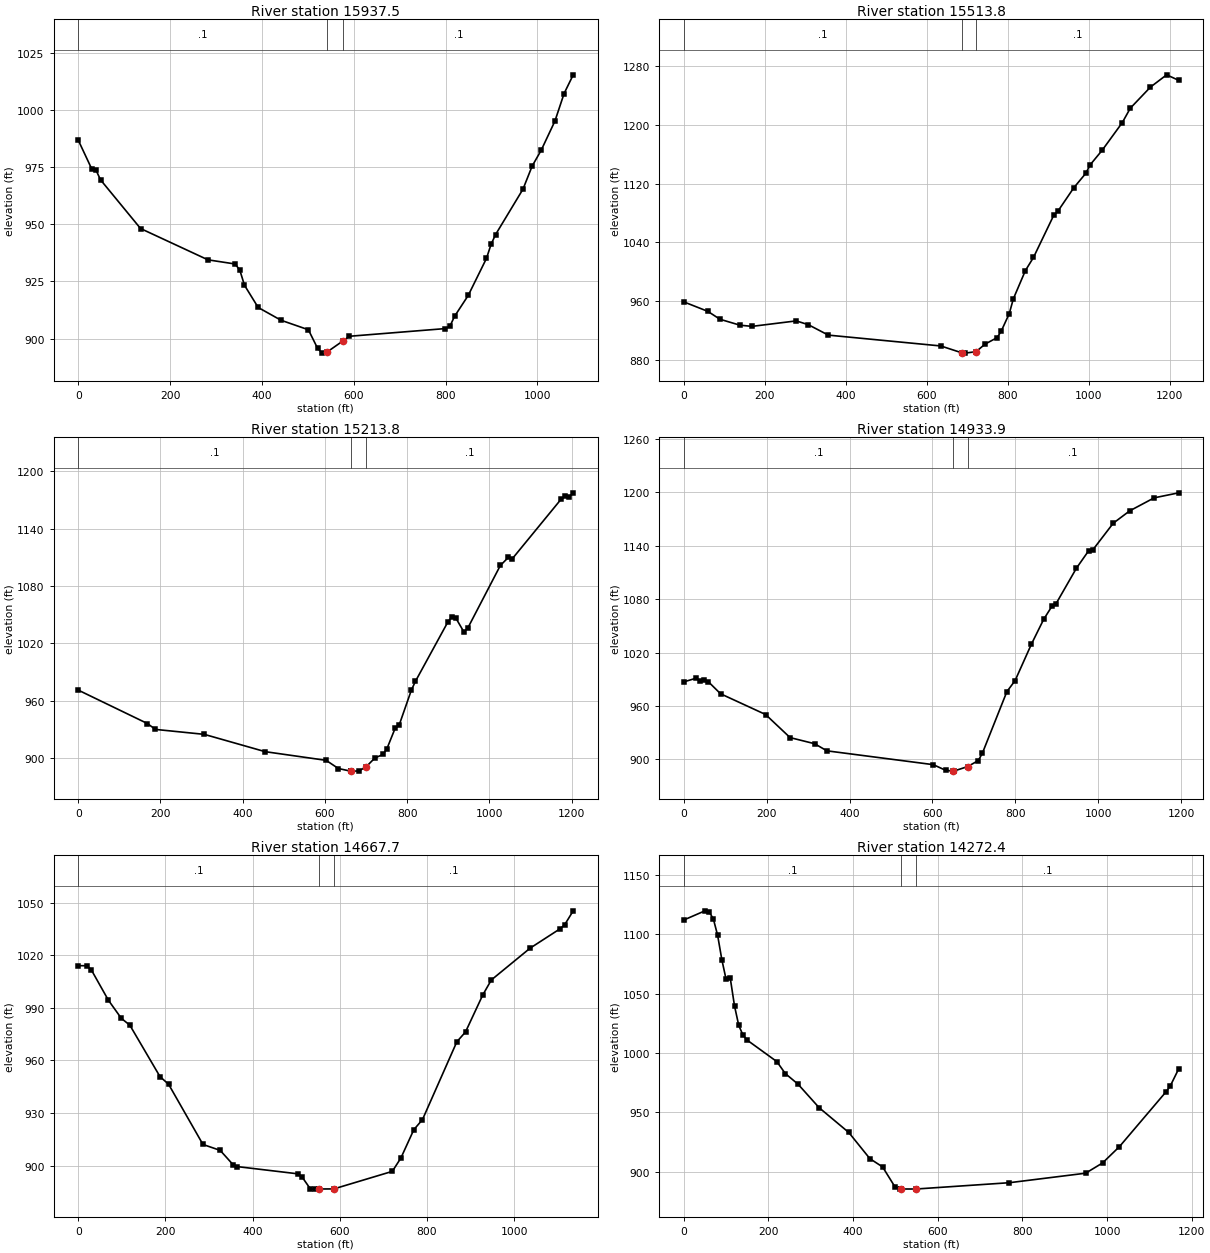
Type RM Length L Ch R = 1 ,15937.5 ,405.6,423.7,442.1
XS GIS Cut Line= 3
     1824400.581      349271.116     1824621.914      349295.788
       1825477.1      349291.215
#Sta/Elev= 30
       0  986.76      29  974.32    38.7  973.62    48.4  969.45   135.6  948.13
   282.4  934.43     342   932.6     352  929.78   361.9  923.32   391.8  913.58
   441.5     908   501.1  903.84     521  895.78     531  893.61   542.5  894.19
   577.5  899.11   590.6  900.99   799.5  904.35   809.4  905.38   819.4  909.69
   849.2  918.84     889  935.08   898.9  941.17   908.8  945.49   968.5  965.36
   988.4  975.43  1008.3  982.45  1038.1  995.16    1058  1007.2  1077.9 1015.38
#Mann= 3 , 0 , 0
       0      .1       0   542.5    .045       0   577.5      .1       0
Bank Sta=542.5,577.5
XS Rating Curve= 0 ,0
Exp/Cntr=0.3,0.1

Type RM Length L Ch R = 1 ,15513.8 ,289.7,300,308.7
XS GIS Cut Line= 3
     1824390.989      349345.974     1824994.938      349708.039
     1825437.496      349977.406
#Sta/Elev= 30
       0  959.07    59.5  946.13    89.3  935.43   138.8  927.34   168.6  925.75
   277.7  933.19   307.4  928.08     357  913.84   634.7  899.11   686.7  889.78
   694.2  889.36   721.7  891.31     744   901.6   773.9  910.47   783.9  919.28
   803.8   943.1   813.8  963.14   843.6 1001.61   863.6 1019.51   913.4 1076.56
   923.4    1082   963.2 1114.27   993.1 1134.08  1003.1 1145.12    1033 1165.08
  1082.8 1202.76  1102.7 1222.44  1152.5 1251.16  1192.4  1267.8  1222.2 1260.33
#Mann= 3 , 0 , 0
       0      .1       0   686.7    .045       0   721.7      .1       0
Bank Sta=686.7,721.7
XS Rating Curve= 0 ,0
Exp/Cntr=0.3,0.1

Type RM Length L Ch R = 1 ,15213.8 ,262.7,279.9,298.5
XS GIS Cut Line= 3
     1824336.037      349405.674     1824784.615      349919.504
     1825143.234      350298.793
#Sta/Elev= 30
       0  971.15     168  936.26   187.8  930.08   306.4  924.92   454.7  906.81
     603  897.74   632.7  889.21   662.3  886.47   664.6  886.48   682.1  886.59
   699.6  890.69   721.5   900.2   741.2  903.88     751  910.05   770.7  931.12
   780.6  934.57   810.1  970.89     820  980.19   898.8 1042.13   908.6 1047.68
   918.5 1046.49   938.2 1031.94     948 1036.36  1026.8 1101.47  1046.5 1109.98
  1056.3 1108.73  1174.5  1170.7  1184.4 1173.78  1194.2 1172.75  1204.1 1177.42
#Mann= 3 , 0 , 0
       0      .1       0   664.6    .045       0   699.6      .1       0
Bank Sta=664.6,699.6
XS Rating Curve= 0 ,0
Exp/Cntr=0.3,0.1

Type RM Length L Ch R = 1 ,14933.9 ,262.7,266.2,269.5
XS GIS Cut Line= 3
     1824264.644      349445.461     1824512.157      349906.308
     1824637.756      350565.776
#Sta/Elev= 30
       0  987.04    29.6  991.21    39.5  988.06    49.4  989.44    59.2  987.27
    88.8  973.71   197.4  950.41   256.6  924.45   315.8  917.58   345.4  909.59
   602.1  894.05   631.7  887.76     650  886.83   651.4  886.78     685  891.88
   710.7  898.64   720.6  906.91   779.8  976.19   799.5  988.46     839 1029.52
   868.6 1057.42   888.4 1071.99   898.3 1074.87   947.6 1114.84   977.2 1134.52
   987.1 1135.41  1036.5 1165.41    1076 1179.22  1135.2 1193.89  1194.4 1199.52
#Mann= 3 , 0 , 0
       0      .1       0     650    .045       0     685      .1       0
Bank Sta=650,685
XS Rating Curve= 0 ,0
Exp/Cntr=0.3,0.1

Type RM Length L Ch R = 1 ,14667.7 ,408.1,395.3,382.8
XS GIS Cut Line= 3
     1824236.089      349470.087     1824276.402      350040.918
     1824320.402      350602.719
#Sta/Elev= 30
       0 1014.14    19.7  1014.1    29.6 1011.88    69.1  994.41    98.7   984.1
   118.4  980.12   187.5   950.8   207.2  946.44   286.1  912.06   325.6  908.69
   355.2  900.52   365.1  899.41   503.2  895.32     513   893.7   532.8  886.61
   542.6  886.56   551.4  886.63   586.4  886.68   720.6   896.7   740.3  904.31
     770   920.5   789.8  926.23   868.8  970.72   888.6  976.28   928.2  997.41
   947.9 1005.99  1036.9 1024.14  1106.1 1035.27    1116 1037.45  1135.8 1045.45
#Mann= 3 , 0 , 0
       0      .1       0   551.4    .045       0   586.4      .1       0
Bank Sta=551.4,586.4
XS Rating Curve= 0 ,0
Exp/Cntr=0.3,0.1

Type RM Length L Ch R = 1 ,14272.4 ,269.9,258.5,249.5
XS GIS Cut Line= 2
     1823661.161      349554.568     1824188.202      350598.328
#Sta/Elev= 30
       0  1112.1      50 1119.84      60 1119.02      70 1112.87      80 1099.18
    89.9 1078.75    99.9 1062.22   109.9 1062.96   119.9 1039.63   129.9 1023.26
   139.9 1015.11   149.9 1010.84   219.9  992.78   239.8  982.75   269.8  973.81
   319.8  953.94   389.8  933.07   439.7  910.99   469.7  904.04   499.7  886.79
   509.7  885.32   513.6  885.44   548.6  885.41   769.5  890.74   949.4  898.74
   989.4  907.38  1029.4  921.18  1139.3  967.31  1149.3   972.2  1169.3   986.7
#Mann= 3 , 0 , 0
       0      .1       0   513.6    .045       0   548.6      .1       0
Bank Sta=513.6,548.6
XS Rating Curve= 0 ,0
Exp/Cntr=0.3,0.1

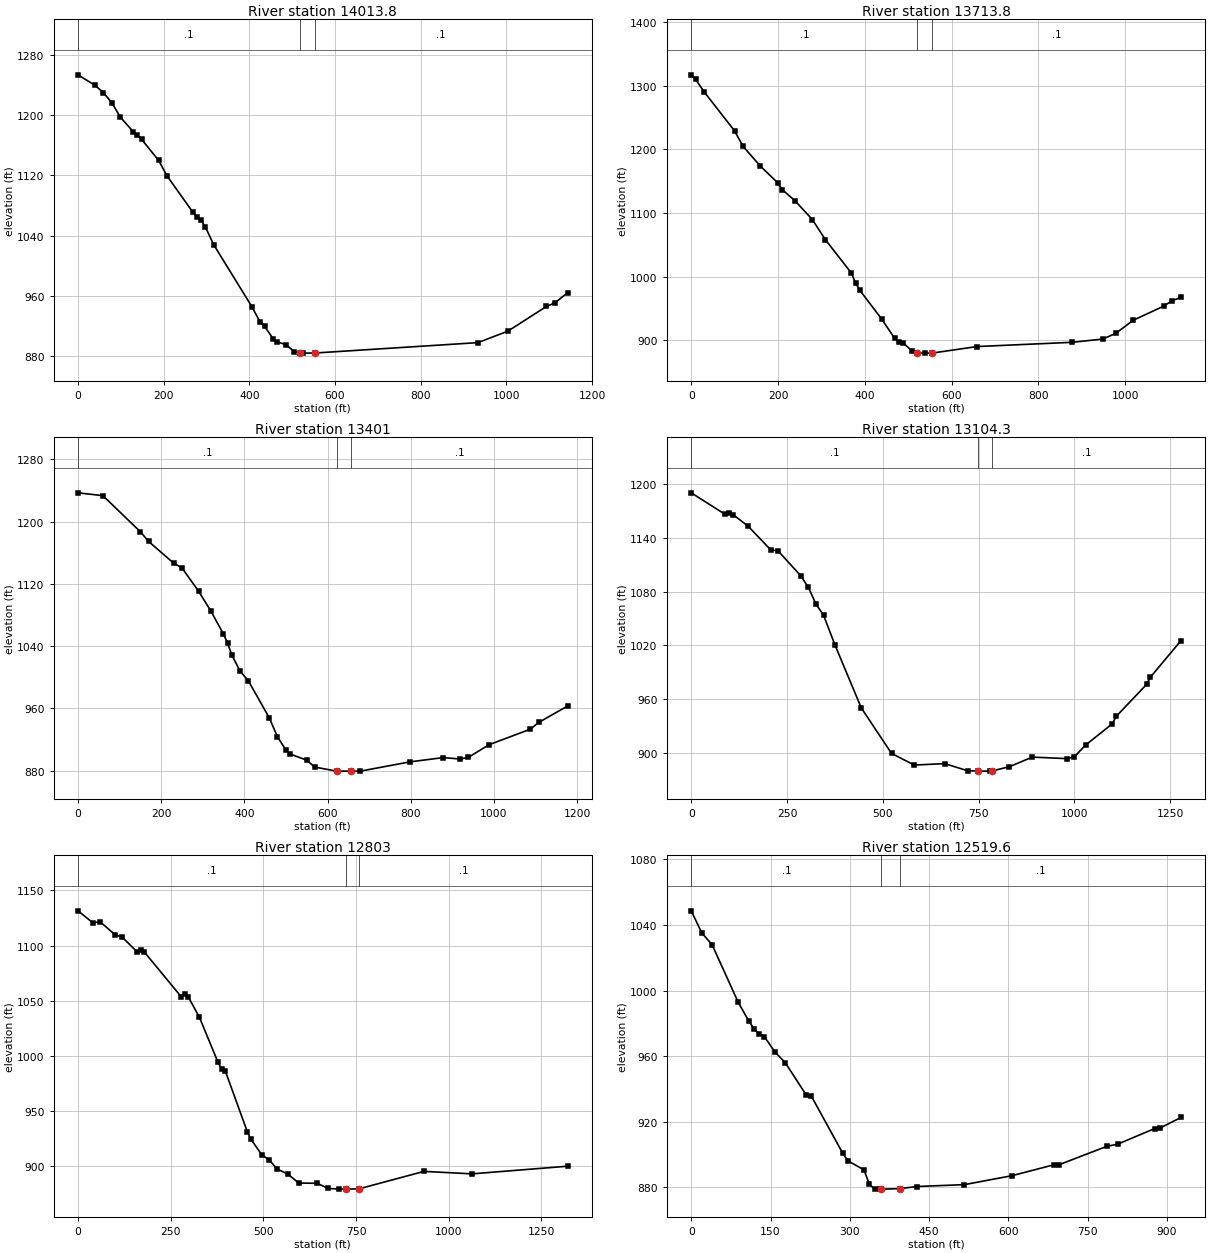
Type RM Length L Ch R = 1 ,14013.8 ,307.8,300,288.4
XS GIS Cut Line= 3
     1823319.009      349835.402      1823709.22      350200.875
     1824121.043      350648.977
#Sta/Elev= 30
       0 1253.77    39.6 1239.84    59.4 1229.99    79.2 1216.46      99 1197.37
   128.7  1178.3   138.6 1174.09   148.5 1167.95   188.1 1140.06   207.9 1119.35
   267.3 1071.75   277.2 1065.14   287.1  1060.5     297 1051.86   316.8 1027.89
   405.9  945.47   425.7  924.57   435.6  919.31   455.4  903.02   465.3  898.89
   485.1  894.97   504.9  885.89   517.1  884.05   524.7  883.79   552.1   883.9
   933.7  897.76  1003.6  913.03  1093.4  945.81  1113.3   950.6  1143.2   964.2
#Mann= 3 , 0 , 0
       0      .1       0   517.1    .045       0   552.1      .1       0
Bank Sta=517.1,552.1
XS Rating Curve= 0 ,0
Exp/Cntr=0.3,0.1

Type RM Length L Ch R = 1 ,13713.8 ,326.9,312.8,300.1
XS GIS Cut Line= 3
     1823077.192      350186.928     1823545.776      350451.764
     1824071.411      350719.595
#Sta/Elev= 30
       0 1317.06      10 1309.76    29.9 1290.14    99.7 1229.06   119.6 1204.44
   159.5 1173.39   199.4 1147.16   209.3 1136.78   239.2    1119   279.1  1089.5
     309 1057.99   368.8 1005.59   378.8  989.41   388.7  978.11   438.6  933.33
   468.5   903.1   478.4  897.54   488.4  895.32   508.3  883.51   520.7  880.08
   538.2  879.66   555.7  879.82   658.2  889.98   878.2  896.69   948.2  901.81
   978.2  910.76  1018.2  931.29  1088.2  953.45  1108.2  962.16  1128.2  967.15
#Mann= 3 , 0 , 0
       0      .1       0   520.7    .045       0   555.7      .1       0
Bank Sta=520.7,555.7
XS Rating Curve= 0 ,0
Exp/Cntr=0.3,0.1

Type RM Length L Ch R = 1 ,13401   ,284.5,296.7,309
XS GIS Cut Line= 3
     1822985.619      350419.996      1823375.72      350747.775
     1824041.243      350803.117
#Sta/Elev= 30
       0 1237.01    59.9 1233.36   149.9 1186.97   169.8 1174.48   229.8 1146.73
   249.8 1140.64   289.7  1110.7   319.7 1084.87   349.7  1055.5   359.7 1043.87
   369.7  1028.7   389.6 1007.94   409.6  995.38   459.6   948.1   479.6   923.4
   499.5  906.85   509.5  901.52   549.4  893.52   569.3  884.56   621.9  879.41
   656.9   879.4     679  879.39   798.6  891.35   878.3  896.78   918.2  894.96
   938.1  896.92     988  913.27  1087.6  933.28  1107.6  941.94  1177.4  963.14
#Mann= 3 , 0 , 0
       0      .1       0   621.9    .045       0   656.9      .1       0
Bank Sta=621.9,656.9
XS Rating Curve= 0 ,0
Exp/Cntr=0.3,0.1

Type RM Length L Ch R = 1 ,13104.3 ,266.5,301.3,336.1
XS GIS Cut Line= 3
     1822956.998      350487.752     1823268.251      350955.855
     1823909.722      351273.847
#Sta/Elev= 30
       0  1190.6    88.8  1166.4    98.6 1168.16   108.5 1166.36   147.9 1153.53
   207.1 1126.96   226.8 1125.58     286 1097.77   305.7 1084.78   325.4 1066.24
   345.2 1053.85   374.8 1020.76   443.8  950.08   522.7   899.2     582  886.17
   661.6  887.78   721.2  879.81   749.3   879.4   780.9  879.38   784.3  879.47
   830.6  884.38   890.3  895.06   979.8  893.38   999.7   895.3  1029.5  908.59
  1099.1  932.36    1109  940.52  1188.6  976.45  1198.6  984.55  1278.1 1025.25
#Mann= 3 , 0 , 0
       0      .1       0   749.3    .045       0   784.3      .1       0
Bank Sta=749.3,784.3
XS Rating Curve= 0 ,0
Exp/Cntr=0.3,0.1

Type RM Length L Ch R = 1 ,12803   ,279.4,283.3,287.2
XS GIS Cut Line= 3
     1822893.625      350527.373      1823195.08       351006.16
     1823229.378      351760.736
#Sta/Elev= 30
       0 1131.44    39.7 1120.65    59.6 1121.51    99.3 1109.95   119.1  1107.6
   158.8 1094.51   168.7 1096.31   178.7 1094.22   277.9 1053.85   287.9 1056.42
   297.8 1053.29   327.6 1034.91   377.2  994.66   387.1  988.29     397  986.74
   456.6  931.48   466.5  924.55   496.3  910.25   516.2   905.9     536  897.83
   565.8  893.06   595.6  884.91   645.3  884.69   675.1  880.03   704.9   879.4
   722.8  879.43   757.8  879.65   933.5  895.47  1062.7  893.23  1321.1  900.16
#Mann= 3 , 0 , 0
       0      .1       0   722.8    .045       0   757.8      .1       0
Bank Sta=722.8,757.8
XS Rating Curve= 0 ,0
Exp/Cntr=0.3,0.1

Type RM Length L Ch R = 1 ,12519.6 ,267.9,263.9,259.8
XS GIS Cut Line= 3
     1822961.847      350727.195     1822941.268      350983.294
     1822888.676      351650.979
#Sta/Elev= 30
       0 1048.62    19.8 1035.25    39.5  1027.9    88.9  992.86   108.7  981.56
   118.6  976.87   128.5  973.49   138.3  971.98   158.1  962.68   177.9  956.06
   217.4  936.45   227.3  935.65   286.9  900.75   296.9  896.15   326.9  890.76
   336.9  882.03   346.9  879.01   356.9     879   359.8     879   394.8  879.29
   426.9   880.6   516.8  881.73   606.8  887.18   686.8  893.88   696.8  893.97
   786.7  905.12   806.7  906.36   876.7  915.88   886.7  916.18   926.7  922.66
#Mann= 3 , 0 , 0
       0      .1       0   359.8    .045       0   394.8      .1       0
Bank Sta=359.8,394.8
XS Rating Curve= 0 ,0
Exp/Cntr=0.3,0.1

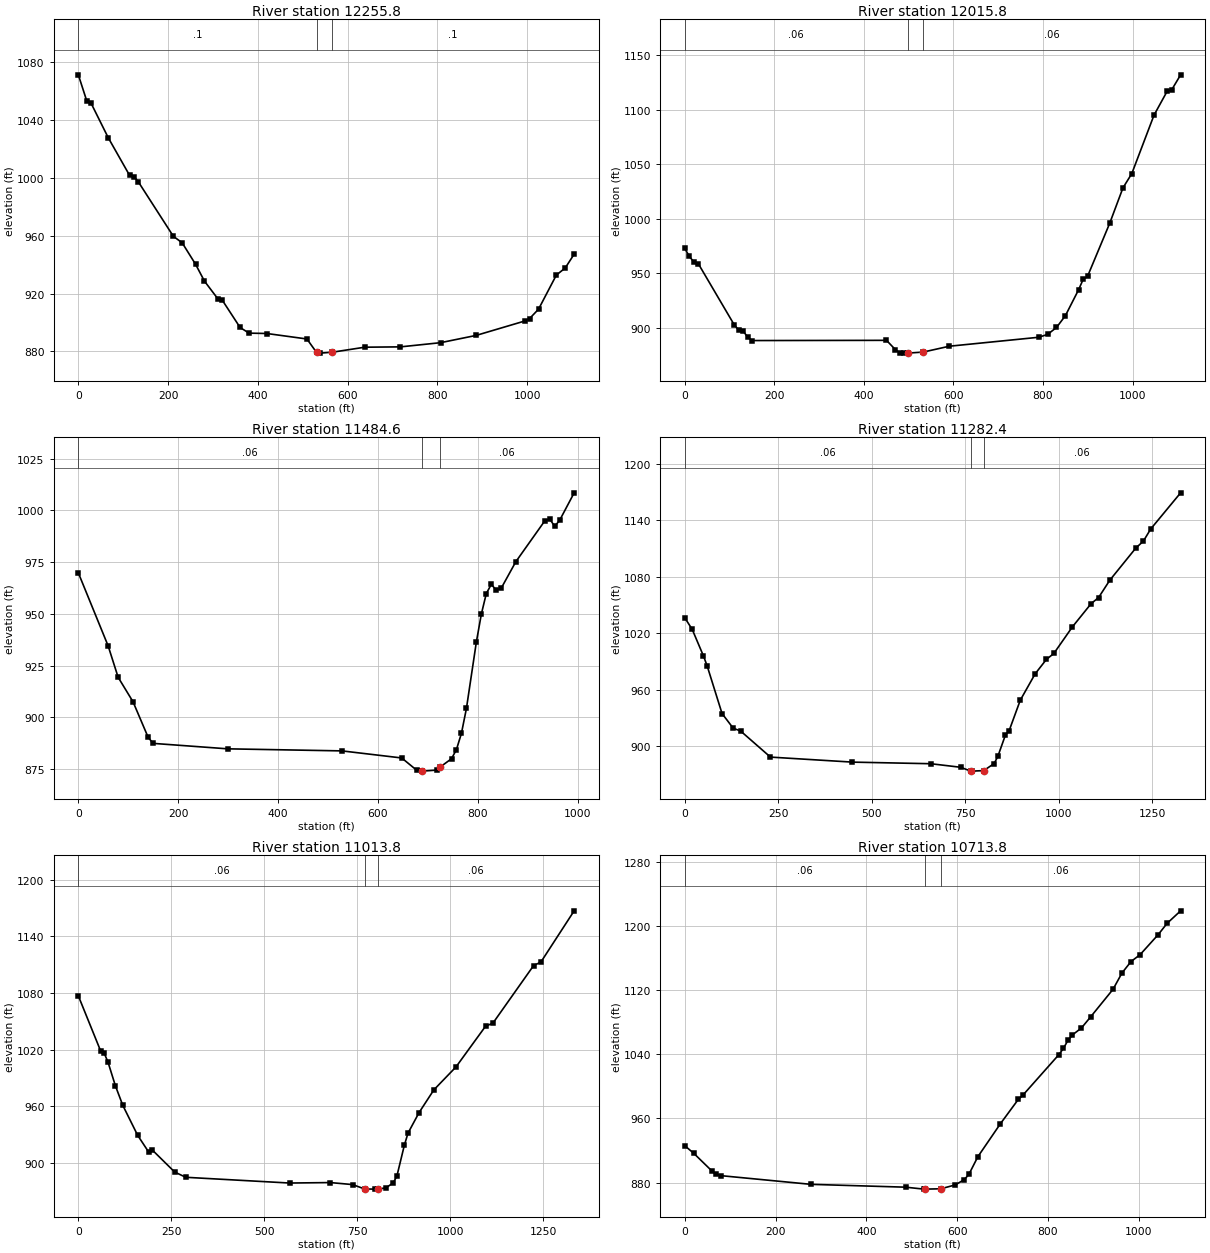
Type RM Length L Ch R = 1 ,12255.8 ,241.6,240,238.3
XS GIS Cut Line= 3
     1822705.749      350532.835     1822653.157      350686.037
     1822701.763      351627.465
#Sta/Elev= 30
       0 1071.29    19.1 1052.93    28.6 1051.53    66.7 1027.75   114.3  1001.7
   123.9 1000.89   133.4  997.42   211.6  959.67   231.4  955.08   261.2  940.28
     281  928.62   310.8   916.4   320.7  915.44   360.4  896.56   380.3  892.65
     420  892.39   509.3   888.6   530.7  879.32     539  878.82   565.7  879.45
   638.3  882.92   717.7  883.15     807  886.04   886.4  891.08   995.5  901.11
  1005.4  902.73  1025.3   909.2    1065  932.79  1084.8  937.72  1104.7  947.26
#Mann= 3 , 0 , 0
       0      .1       0   530.7    .045       0   565.7      .1       0
Bank Sta=530.7,565.7
XS Rating Curve= 0 ,0
Exp/Cntr=0.3,0.1

Type RM Length L Ch R = 1 ,12015.8 ,511.6,531.2,550.8
XS GIS Cut Line= 3
     1822376.479      350615.152     1822472.516      351369.728
     1822371.906      351701.284
#Sta/Elev= 30
       0  972.59      10  965.33      20  960.28      30   958.7   110.1  902.73
   120.1  897.73   130.1  896.92   140.1  891.38   150.1   888.1   450.4   888.3
   470.4  879.72   480.4  876.78   490.4  876.57   497.3  876.59   532.3  877.52
   590.5  882.89   790.4  891.12   810.2  893.75     830  900.09   849.8  910.86
   879.5  934.81   889.4  944.12   899.3  946.94   948.8  995.63   978.4  1028.1
   998.2 1041.24  1047.8 1094.84  1077.4 1116.96  1087.4 1118.16  1107.2  1131.8
#Mann= 3 , 0 , 0
       0     .06       0   497.3    .045       0   532.3     .06       0
Bank Sta=497.3,532.3
XS Rating Curve= 0 ,0
Exp/Cntr=0.3,0.1

Type RM Length L Ch R = 1 ,11484.6 ,195.6,202.3,209
XS GIS Cut Line= 3
     1822296.448      350541.981     1821894.008      351287.411
     1821808.642      351405.933
#Sta/Elev= 30
       0   969.8    59.8  934.44    79.7  919.34   109.6  907.46   139.5   890.5
   149.5  887.38     299  884.74   528.2  883.74   647.8  880.32   677.7  874.41
   687.7  873.96   688.9  873.96   717.6  874.45   723.9  875.78   747.5  879.95
   757.4  884.38   767.4  892.23   777.4  904.25   797.3  936.38   807.3  949.88
   817.2   959.8   827.2  964.23   837.2  961.44   847.1  962.38   876.3  975.17
   934.8  995.08   944.5  995.74   954.2   992.3     964  995.15   993.2 1008.49
#Mann= 3 , 0 , 0
       0     .06       0   688.9    .045       0   723.9     .06       0
Bank Sta=688.9,723.9
XS Rating Curve= 0 ,0
Exp/Cntr=0.3,0.1

Type RM Length L Ch R = 1 ,11282.4 ,265.3,268.5,271.3
XS GIS Cut Line= 3
     1822326.174      350439.085      1822154.68      350619.726
     1821461.027      351444.154
#Sta/Elev= 30
       0 1036.37    19.9 1024.02    49.8  995.91    59.8  985.25    99.6  934.59
   129.5  918.97   149.4  915.94   229.2  888.22   448.6  882.88   658.1  881.18
   737.9   877.4   764.7  873.37   767.8   873.3   799.7  873.85   827.7  881.38
   837.7   889.2   857.6   911.5   867.6   916.2   897.5  948.71   937.4  976.85
   967.4  992.12   987.3  998.44  1037.2 1026.86  1087.1 1051.46    1107 1057.92
    1137 1076.36  1206.8 1110.66  1226.7 1117.85  1246.7 1130.97  1326.5 1169.32
#Mann= 3 , 0 , 0
       0     .06       0   764.7    .045       0   799.7     .06       0
Bank Sta=764.7,799.7
XS Rating Curve= 0 ,0
Exp/Cntr=0.3,0.1

Type RM Length L Ch R = 1 ,11013.8 ,299.5,300,299.7
XS GIS Cut Line= 3
     1822179.832      350290.456     1821617.691      350841.762
      1821231.62      351227.853
#Sta/Elev= 30
       0 1076.98    59.8 1018.89    69.8 1016.08    79.7 1007.03    99.7  981.84
   119.6  961.16   159.5  929.52   189.4  911.66   199.3  913.82   259.1  890.67
     289  885.11   568.1  879.03   677.7  879.52   737.5  877.41   769.9  872.76
   797.3  872.59   804.9  872.61   827.1  873.95   846.9  879.21   856.8  886.58
   876.7  918.94   886.6  931.84   916.4   953.6   956.1  977.56  1015.7 1001.86
  1095.1 1044.85    1115 1048.15  1224.2 1108.93    1244 1112.74  1333.4  1166.9
#Mann= 3 , 0 , 0
       0     .06       0   769.9    .045       0   804.9     .06       0
Bank Sta=769.9,804.9
XS Rating Curve= 0 ,0
Exp/Cntr=0.3,0.1

Type RM Length L Ch R = 1 ,10713.8 ,284.6,296.2,308.8
XS GIS Cut Line= 3
     1821792.178      350263.239     1821396.423      350639.907
     1821013.449      351028.981
#Sta/Elev= 30
       0  925.98    19.9   916.4    59.6   894.5    69.5  890.26    79.5   888.6
   278.1  877.74   486.8  874.19   526.5  871.77   528.9  871.77   563.9  872.19
     596  877.05   615.8  883.71   625.8  890.15   645.6  912.23   695.2  953.36
     735  984.03   744.9  989.14   824.3 1039.83   834.2 1047.63   844.1 1057.53
   854.1 1064.37   873.9 1073.05   893.8 1086.68   943.4 1121.29   963.2 1141.73
   983.1 1155.96    1003 1164.52  1042.7 1189.41  1062.5 1203.63  1092.3 1219.26
#Mann= 3 , 0 , 0
       0     .06       0   528.9    .045       0   563.9     .06       0
Bank Sta=528.9,563.9
XS Rating Curve= 0 ,0
Exp/Cntr=0.3,0.1

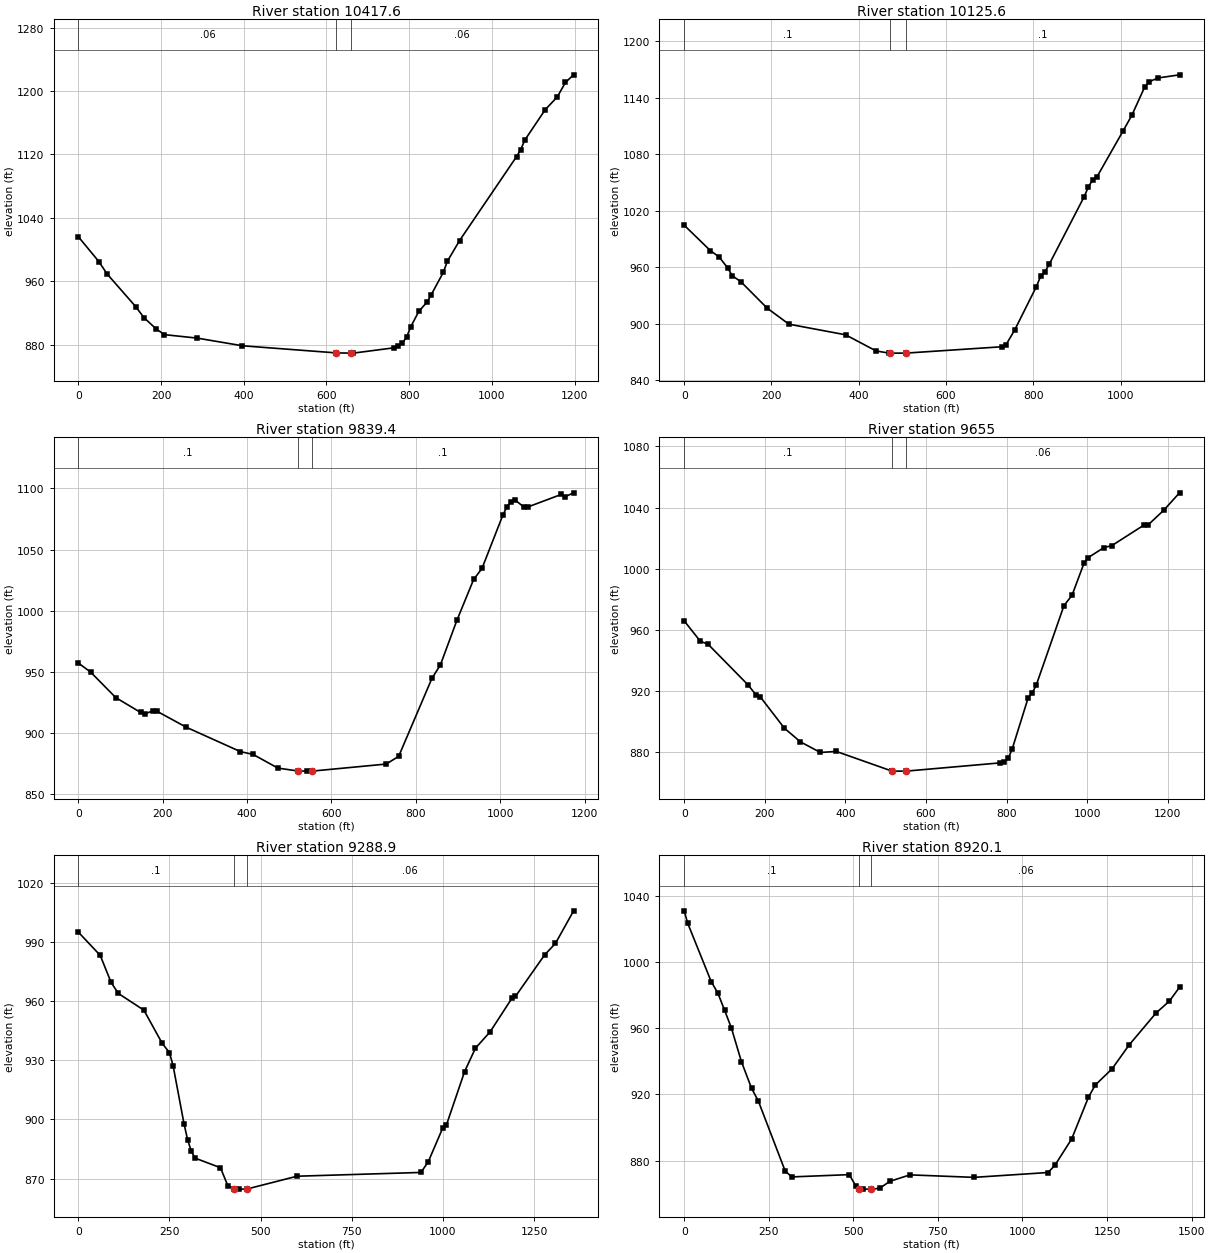
Type RM Length L Ch R = 1 ,10417.6 ,307.8,292,275.2
XS GIS Cut Line= 3
     1821827.697      350139.541     1821098.273      350452.804
     1820771.397      350690.005
#Sta/Elev= 30
       0 1016.08    49.6  984.76    69.5  969.12   138.9  927.73   158.8  913.88
   188.5  899.54   208.4  892.44   287.8  888.04   396.9  878.38   624.3  869.38
   659.3  869.13   664.8  869.11   764.1  875.88     774  877.48   783.9  882.04
   793.8  889.39   803.7  902.18   823.4  921.88   843.1   933.4     853  942.45
   882.5  970.98   892.4  985.04   921.9  1011.2  1059.8 1117.23  1069.7 1125.92
  1079.5 1137.92  1128.8 1176.26  1158.3 1192.65    1178 1210.89  1197.7 1220.43
#Mann= 3 , 0 , 0
       0     .06       0   624.3    .045       0   659.3     .06       0
Bank Sta=624.3,659.3
XS Rating Curve= 0 ,0
Exp/Cntr=0.3,0.1

Type RM Length L Ch R = 1 ,10125.6 ,296.4,286.1,276.7
XS GIS Cut Line= 3
     1821434.403      349730.241     1821187.451      350057.224
     1820729.392      350619.605
#Sta/Elev= 30
       0 1004.56      60  977.63      80  970.95    99.9  959.13   109.9  951.11
   129.9  944.64   189.9  916.71   239.9  899.61   369.8  888.34   439.6  871.24
   469.4   868.9   472.4   868.9   507.4   868.9   727.7  875.64   737.6  877.84
   757.5  893.58   807.2  939.58   817.1  950.92   827.1  955.44     837  963.63
   916.5  1034.8   926.4 1045.38   936.4  1052.9   946.3 1056.23  1005.9 1104.71
  1025.8  1121.2  1055.6 1151.53  1065.5 1156.78  1085.4 1160.77  1135.1 1164.13
#Mann= 3 , 0 , 0
       0      .1       0   472.4    .045       0   507.4      .1       0
Bank Sta=472.4,507.4
XS Rating Curve= 0 ,0
Exp/Cntr=0.3,0.1

Type RM Length L Ch R = 1 ,9839.4  ,173.6,184.4,195.3
XS GIS Cut Line= 3
     1821170.697      349530.066     1820913.059      349926.888
     1820656.664      350579.266
#Sta/Elev= 30
       0  957.25    29.6  949.65    88.7  928.95   147.8  916.75   157.7  915.64
   177.4  918.18   187.3   917.6   256.3  904.64   384.4  884.74     414  882.51
   473.1  871.28     520  868.94   542.2   868.8     555  868.84   729.8  874.58
   759.4  880.88   838.4   944.8   858.2  955.58   897.6  992.28   937.1 1025.55
   956.9 1034.57  1006.2 1078.03  1016.1  1085.1    1026  1088.8  1035.9 1090.35
  1055.6 1084.92  1065.5 1084.81  1144.5 1095.04  1154.3 1093.29  1174.1 1096.39
#Mann= 3 , 0 , 0
       0      .1       0     520    .045       0     555      .1       0
Bank Sta=520,555
XS Rating Curve= 0 ,0
Exp/Cntr=0.3,0.1

Type RM Length L Ch R = 1 ,9655    ,387.1,366,344.9
XS GIS Cut Line= 3
     1821084.764      349477.373     1820645.528      349990.912
     1820597.197      350542.312
#Sta/Elev= 30
       0     966    39.8  952.75    59.6  950.64     159     924   178.9  917.37
   188.8  916.35   248.4  895.93   288.2  886.97   337.9  880.01   377.6  880.66
   515.8  867.81   516.8   867.8   550.8   867.8   784.5   873.2   794.4  873.67
   804.2  876.17   814.1  882.34   853.7  915.77   863.6  918.92   873.4  923.78
   942.6  976.05   962.4  982.67     992 1003.51  1001.9 1007.24  1041.5 1013.89
  1061.2 1015.19  1140.3  1028.5  1150.2 1028.46  1189.7 1038.19  1229.3  1049.7
#Mann= 3 , 0 , 0
       0      .1       0   515.8    .045       0   550.8     .06       0
Bank Sta=515.8,550.8
XS Rating Curve= 0 ,0
Exp/Cntr=0.3,0.1

Type RM Length L Ch R = 1 ,9288.9  ,389.1,368.8,348.5
XS GIS Cut Line= 3
     1820542.631      349167.739     1820474.033      350134.968
     1820540.513      350518.037
#Sta/Elev= 30
       0  994.92      60  983.15      90   969.4     110  963.81   179.9  955.36
   229.9  938.61   249.9  933.87   259.9  927.29   289.9  897.81   299.9  889.62
   309.9  883.92   319.9  880.44   389.9  875.54   409.9  866.48   426.9  864.72
   439.8   864.7   461.9  864.73   599.8  871.24   939.7  873.15   959.7  878.56
   999.6  895.73  1009.5  897.16  1059.4  924.26  1089.3  936.14  1129.2  944.34
    1189  961.34    1199  962.36  1278.7  983.32  1308.6   989.2  1358.4 1005.69
#Mann= 3 , 0 , 0
       0      .1       0   426.9    .045       0   461.9     .06       0
Bank Sta=426.9,461.9
XS Rating Curve= 0 ,0
Exp/Cntr=0.3,0.1

Type RM Length L Ch R = 1 ,8920.1  ,352.7,339,325.2
XS GIS Cut Line= 3
     1819870.373      349202.038     1820455.741      350128.108
     1820515.192      350492.034
#Sta/Elev= 30
       0 1030.82      10 1023.49    79.7  988.14    99.6  981.09   119.5  970.73
   139.4  960.14   169.3  939.67   199.2  923.64   219.1     916   298.8  873.56
   318.7  870.18     488  871.55   507.9  864.44   518.1  862.94   527.9   862.8
   553.1   862.8   577.7  863.27   607.5  867.47   667.3  871.41   856.5   869.9
  1075.6  872.83  1095.6   877.1  1145.4  893.07  1195.2  918.33  1215.2  925.64
    1265  935.44  1314.8  949.71  1394.6  969.07  1434.4  976.32  1464.3  984.69
#Mann= 3 , 0 , 0
       0      .1       0   518.1    .045       0   553.1     .06       0
Bank Sta=518.1,553.1
XS Rating Curve= 0 ,0
Exp/Cntr=0.3,0.1

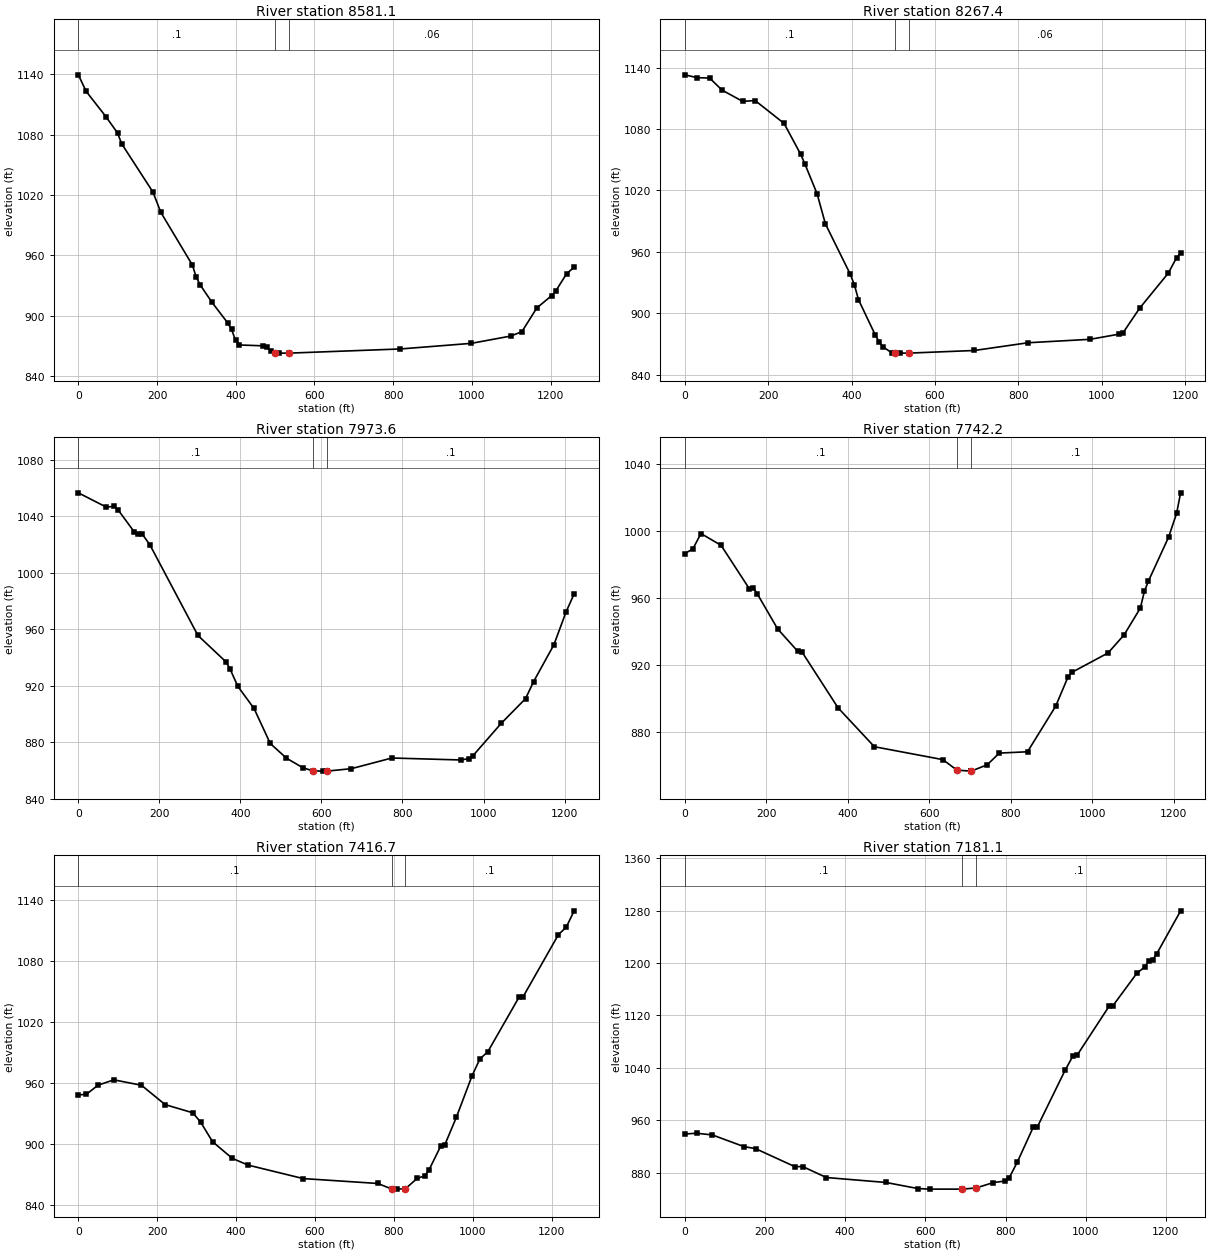
Type RM Length L Ch R = 1 ,8581.1  ,325.5,313.7,301.8
XS GIS Cut Line= 3
     1819493.085      349613.624     1820419.155      350221.858
     1820485.609      350358.268
#Sta/Elev= 30
       0 1139.67      20 1123.15    69.9 1098.15    99.8 1081.73   109.8 1071.27
   189.6 1023.02   209.6 1002.83   289.5  950.62   299.4  938.62   309.4  930.78
   339.4   913.4   379.3  892.99   389.3  886.36   399.3  875.63   409.2  870.92
   469.1  870.07   479.1  868.53   489.1  864.84   500.7  862.86   509.1   862.8
   535.7   862.8   818.5  866.95   998.2  872.52    1098  879.74  1126.9  884.13
  1164.8  907.73  1202.8  920.12  1212.3  924.21  1240.7  941.88  1259.7  948.26
#Mann= 3 , 0 , 0
       0      .1       0   500.7    .045       0   535.7     .06       0
Bank Sta=500.7,535.7
XS Rating Curve= 0 ,0
Exp/Cntr=0.3,0.1

Type RM Length L Ch R = 1 ,8267.4  ,294.5,293.9,293.3
XS GIS Cut Line= 3
     1819361.821      350090.642     1820387.143      350322.468
     1820485.609       350418.72
#Sta/Elev= 30
       0 1132.91    29.8 1130.11    59.5 1129.79    89.2 1118.01   138.8 1106.95
   168.6  1107.8     238 1085.45   277.7 1055.43   287.6 1046.19   317.3 1016.59
   337.2  987.22   396.7  938.13   406.6  927.75   416.5  913.18   456.2  879.17
   466.1  871.78     476  866.95   495.8  861.44   502.9  861.14   515.7     861
   537.9  861.02   694.2  863.58   823.1  871.14   971.9   874.5  1041.3  879.54
  1051.2   881.1  1090.5  904.82  1159.4   939.2  1179.1  954.18  1188.9  958.78
#Mann= 3 , 0 , 0
       0      .1       0   502.9    .045       0   537.9     .06       0
Bank Sta=502.9,537.9
XS Rating Curve= 0 ,0
Exp/Cntr=0.3,0.1

Type RM Length L Ch R = 1 ,7973.6  ,224.6,231.4,238.2
XS GIS Cut Line= 3
     1819316.976      350213.045     1819616.561      350452.804
     1820439.306      350621.941
#Sta/Elev= 30
       0 1056.53    68.9 1046.44    88.6 1046.95    98.4 1044.35   137.7    1029
   147.6 1027.33   157.4 1027.52   177.1 1019.44   295.2  955.56     364     937
   373.9  932.18   393.7  919.54   433.7  903.88   473.7  879.11   513.7  868.71
   553.7  862.02   578.2  859.78   603.7  859.55   613.2  859.55   673.7  861.28
   773.7  868.84   943.7  867.44   963.7  868.39   973.7  870.38  1043.7  893.37
  1103.7  910.85  1123.7  922.97  1173.7  948.99  1203.7  972.23  1223.7  985.02
#Mann= 3 , 0 , 0
       0      .1       0   578.2    .045       0   613.2      .1       0
Bank Sta=578.2,613.2
XS Rating Curve= 0 ,0
Exp/Cntr=0.3,0.1

Type RM Length L Ch R = 1 ,7742.2  ,297.7,325.4,353.1
XS GIS Cut Line= 3
     1819282.447      350283.559     1819587.836      350634.803
     1820277.243      350934.489
#Sta/Elev= 30
       0  986.49    19.8  989.22    39.6  998.42    89.1  991.38   158.4  965.51
   168.4  965.87   178.2  962.38   227.8  941.61   277.3  928.24   287.2  928.04
   376.3  894.54   465.4  871.38   633.6  863.69   668.1  857.42   702.8  856.84
   703.1  856.85   742.4  860.62   772.1  867.59   841.3  868.37   910.5  895.55
   940.2  912.64   950.1  915.68  1039.1  927.26  1078.7  938.12  1118.3     954
  1128.2  963.92    1138  970.01  1187.5  996.16  1207.3 1010.43  1217.2 1022.67
#Mann= 3 , 0 , 0
       0      .1       0   668.1    .045       0   703.1      .1       0
Bank Sta=668.1,703.1
XS Rating Curve= 0 ,0
Exp/Cntr=0.3,0.1

Type RM Length L Ch R = 1 ,7416.7  ,224.5,235.6,246.7
XS GIS Cut Line= 3
     1819205.117      350275.238     1819511.949      350695.255
     1819742.375      351394.957
#Sta/Elev= 30
       0  948.19      20  948.65      50  957.72      90  962.97     160  957.65
   220.1  938.59   290.1  930.57   310.1  921.35   340.1  902.17   390.1   885.8
   430.1  879.15   569.9  865.88   759.1  861.06   794.2  855.62   808.8   855.5
   829.2  855.91   858.6  865.97   878.5  868.66   888.5  874.12   918.4  897.68
   928.3  898.46   958.2  926.11     998  966.94  1017.9  983.57  1037.8  990.51
  1117.4 1044.44  1127.4 1044.65    1217  1105.8  1236.9 1113.16  1256.8 1129.16
#Mann= 3 , 0 , 0
       0      .1       0   794.2    .045       0   829.2      .1       0
Bank Sta=794.2,829.2
XS Rating Curve= 0 ,0
Exp/Cntr=0.3,0.1

Type RM Length L Ch R = 1 ,7181.1  ,465.9,476.7,487.6
XS GIS Cut Line= 3
     1819152.887      350354.738     1819377.755      350676.176
     1819358.015      351520.381
#Sta/Elev= 30
       0  938.82    29.4  940.01    68.6  937.44   147.1  919.67   176.5  916.47
   274.6  888.93   294.2  889.06   353.1  872.33   501.6  864.79     581   855.5
   610.8   854.6   691.6   854.6   726.6  856.42   769.8  864.65   799.6  867.05
   809.5  872.28   829.4  895.94   869.1  949.22   879.1  949.36   948.6 1036.31
   968.5 1058.56   978.4 1059.17  1057.9 1133.77  1067.8 1134.86  1127.4 1184.46
  1147.3 1194.22  1157.2 1203.26  1167.2 1205.39  1177.1 1214.28  1236.7 1279.95
#Mann= 3 , 0 , 0
       0      .1       0   691.6    .045       0   726.6      .1       0
Bank Sta=691.6,726.6
XS Rating Curve= 0 ,0
Exp/Cntr=0.3,0.1

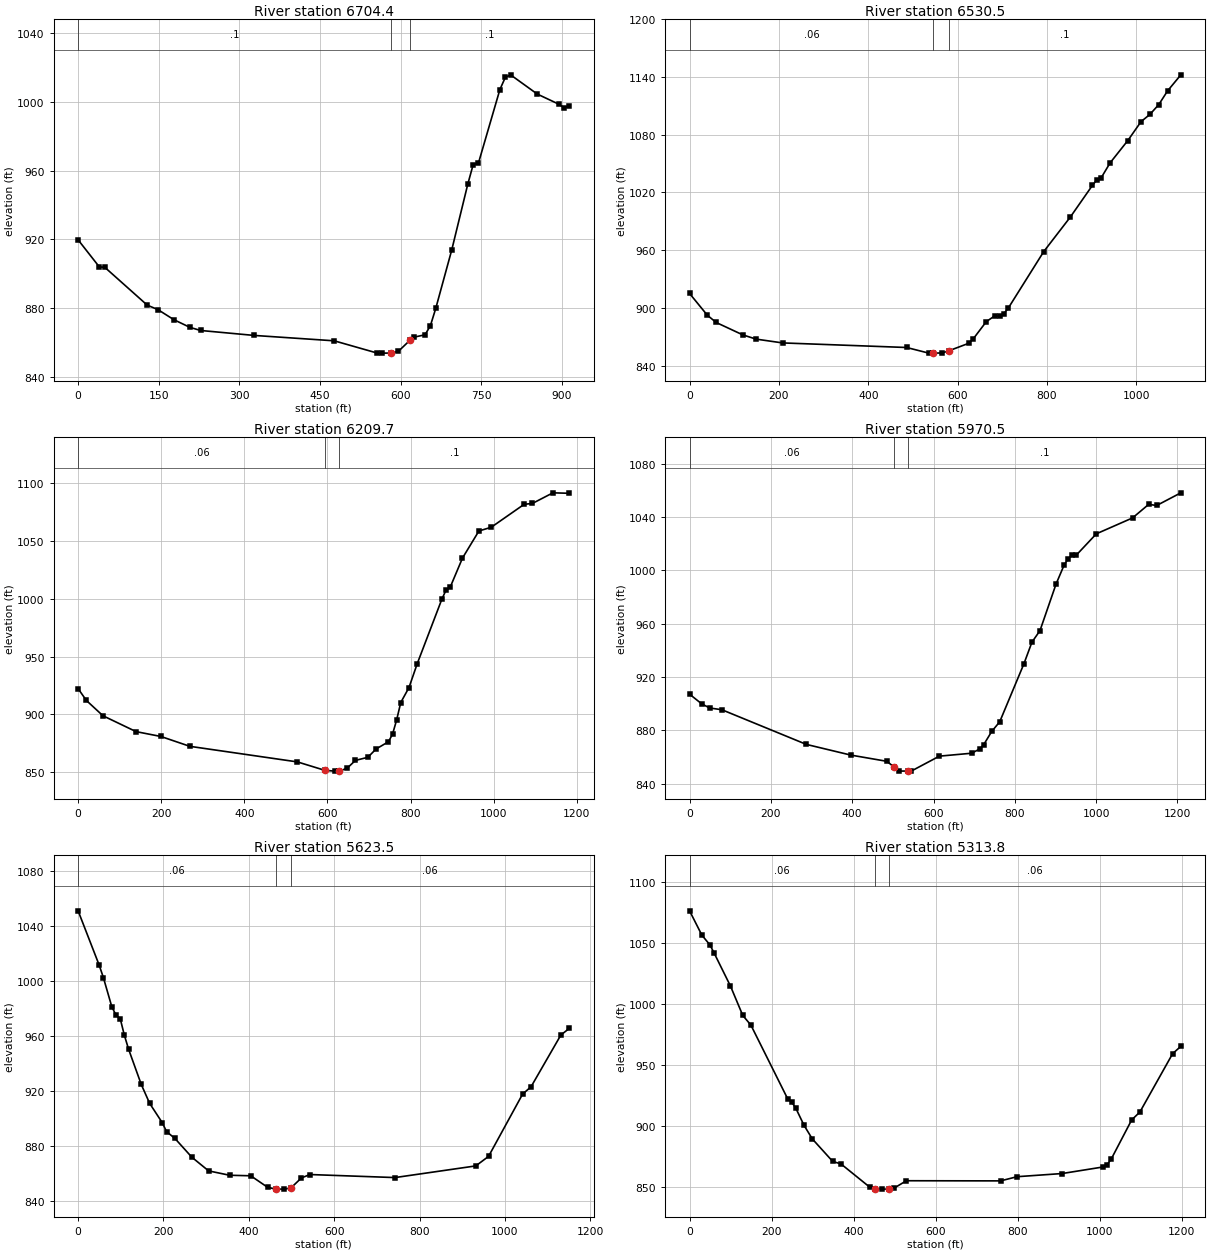
Type RM Length L Ch R = 1 ,6704.4  ,169.9,173.9,180.8
XS GIS Cut Line= 3
     1819054.894      350341.879     1819059.347      350529.834
     1818808.393      351210.953
#Sta/Elev= 30
       0  919.65    39.6  903.84    49.5   903.7   128.6  881.63   148.4  879.04
   178.1  873.18   207.9  868.71   227.8  866.89   327.2  864.01   476.4  860.87
   555.9  853.78   565.9   853.7   582.6  853.74   595.7  854.72   617.6  861.29
   625.5  863.05   645.4  864.37   655.4  869.73   665.3  879.72   695.1  913.82
     725  952.19   734.9  963.42   744.8  964.41   784.6 1007.12   794.6 1014.16
   804.5 1015.71   854.2  1004.5     894  998.65   903.9  996.57   913.9  997.71
#Mann= 3 , 0 , 0
       0      .1       0   582.6    .045       0   617.6      .1       0
Bank Sta=582.6,617.6
XS Rating Curve= 0 ,0
Exp/Cntr=0.3,0.1

Type RM Length L Ch R = 1 ,6530.5  ,321.7,320.8,316.9
XS GIS Cut Line= 3
      1819011.21      350322.199     1818771.367      350823.062
     1818479.522      351282.661
#Sta/Elev= 30
       0  914.98    39.7  892.42    59.5  884.86     119     872   148.8  867.56
   208.2  863.61   485.9  858.85   535.5     853   545.4  853.01   565.2  853.18
   580.4  855.42   624.6  863.16   634.5  867.49   664.2  885.68     684  892.02
   693.9  891.16   703.8  894.09   713.7  899.95   792.9  958.55   852.3  994.34
   901.8 1027.29   911.7 1033.03   921.6 1035.28   941.4 1050.68     981 1073.84
  1010.7 1093.53  1030.5 1101.04  1050.3 1111.19  1070.1  1125.5  1099.8 1142.17
#Mann= 3 , 0 , 0
       0     .06       0   545.4    .045       0   580.4      .1       0
Bank Sta=545.4,580.4
XS Rating Curve= 0 ,0
Exp/Cntr=0.3,0.1

Type RM Length L Ch R = 1 ,6209.7  ,230,239.2,248.3
XS GIS Cut Line= 3
     1818755.801      350113.388     1818447.111      350760.494
     1818343.138      351213.761
#Sta/Elev= 30
       0  922.33    19.9  912.07    59.8  898.82   139.4  885.09   199.2  880.88
   268.9  872.34   527.8  858.84   593.4  851.58   617.4  850.87   628.4  850.93
   647.3  853.38   667.2  860.16     697  862.83     717  870.07   746.6  876.29
   756.5  882.87   766.4  895.21   776.3   910.3   796.1  923.27   815.9  943.91
   875.3   999.9   885.2 1007.63   895.1 1010.05   924.8  1035.4   964.3 1058.85
     994 1062.09  1073.2 1081.96    1093 1082.71  1142.4  1091.9    1182  1091.5
#Mann= 3 , 0 , 0
       0     .06       0   593.4    .045       0   628.4      .1       0
Bank Sta=593.4,628.4
XS Rating Curve= 0 ,0
Exp/Cntr=0.3,0.1

Type RM Length L Ch R = 1 ,5970.5  ,344.8,347,328.2
XS GIS Cut Line= 3
     1818646.039      350134.963     1818225.312      350609.579
     1818273.311      351181.747
#Sta/Elev= 30
       0  907.13    29.7  899.91    49.6  896.76    79.3  895.48   287.4  869.45
   396.4  861.46   485.6  856.76     503  852.44   515.3  849.48     538  849.46
   545.1  849.42   614.4  860.65   693.6  862.84   713.4  865.96   723.4  869.22
   743.2  879.18   762.9  886.44   822.3  929.86   842.1  946.13   861.9   954.8
   901.5  989.78   921.3 1003.99   931.2 1008.74   941.1 1011.18     951 1011.35
  1000.5  1027.4  1089.6 1039.33  1129.2 1049.48    1149 1048.66  1208.4 1058.15
#Mann= 3 , 0 , 0
       0     .06       0     503    .045       0     538      .1       0
Bank Sta=503,538
XS Rating Curve= 0 ,0
Exp/Cntr=0.3,0.1

Type RM Length L Ch R = 1 ,5623.5  ,349.2,309.7,292.5
XS GIS Cut Line= 3
     1818432.051      349912.971     1818081.256       350259.73
      1818071.38      350917.521
#Sta/Elev= 30
       0 1050.81    49.3 1011.39    59.2  1002.3    78.9  981.14    88.8  974.95
    98.6  972.52   108.5  960.23   118.4  950.11     148  924.57   167.7  910.81
   197.3  896.74   207.2  890.34   226.9  885.33   266.4  871.73   305.8  861.76
   355.1  858.58   404.5   858.2   443.9  849.85   463.6  848.51   483.4   848.5
   498.6  849.36   523.2  856.63   543.1  859.11   742.4   856.9   931.8  865.38
   961.7   872.3  1041.5  917.58  1061.4  922.97  1131.2  960.56  1151.1  965.39
#Mann= 3 , 0 , 0
       0     .06       0   463.6    .045       0   498.6     .06       0
Bank Sta=463.6,498.6
XS Rating Curve= 0 ,0
Exp/Cntr=0.3,0.1

Type RM Length L Ch R = 1 ,5313.8  ,309.5,300,292.4
XS GIS Cut Line= 3
     1817614.195      349810.356     1817803.399      350239.389
      1818071.38      350917.521
#Sta/Elev= 30
       0 1076.33    29.9  1056.5    49.9 1048.31    59.9 1041.76    99.8 1014.69
   129.7  990.73   149.6  982.75   239.4  922.33   249.4  919.68   259.4  914.53
   279.3  900.64   299.3  889.62   349.2  871.13   369.1  869.17     439  850.21
   451.4  848.68   468.9   848.5   486.4  848.52   498.9  849.37   528.8  855.37
   758.6  855.25   798.5  858.67   908.4  861.26  1008.3  866.63  1018.3  868.53
  1028.3  873.11  1078.2  905.17  1098.2  911.61  1178.1  959.43  1198.1  965.39
#Mann= 3 , 0 , 0
       0     .06       0   451.4    .045       0   486.4     .06       0
Bank Sta=451.4,486.4
XS Rating Curve= 0 ,0
Exp/Cntr=0.3,0.1