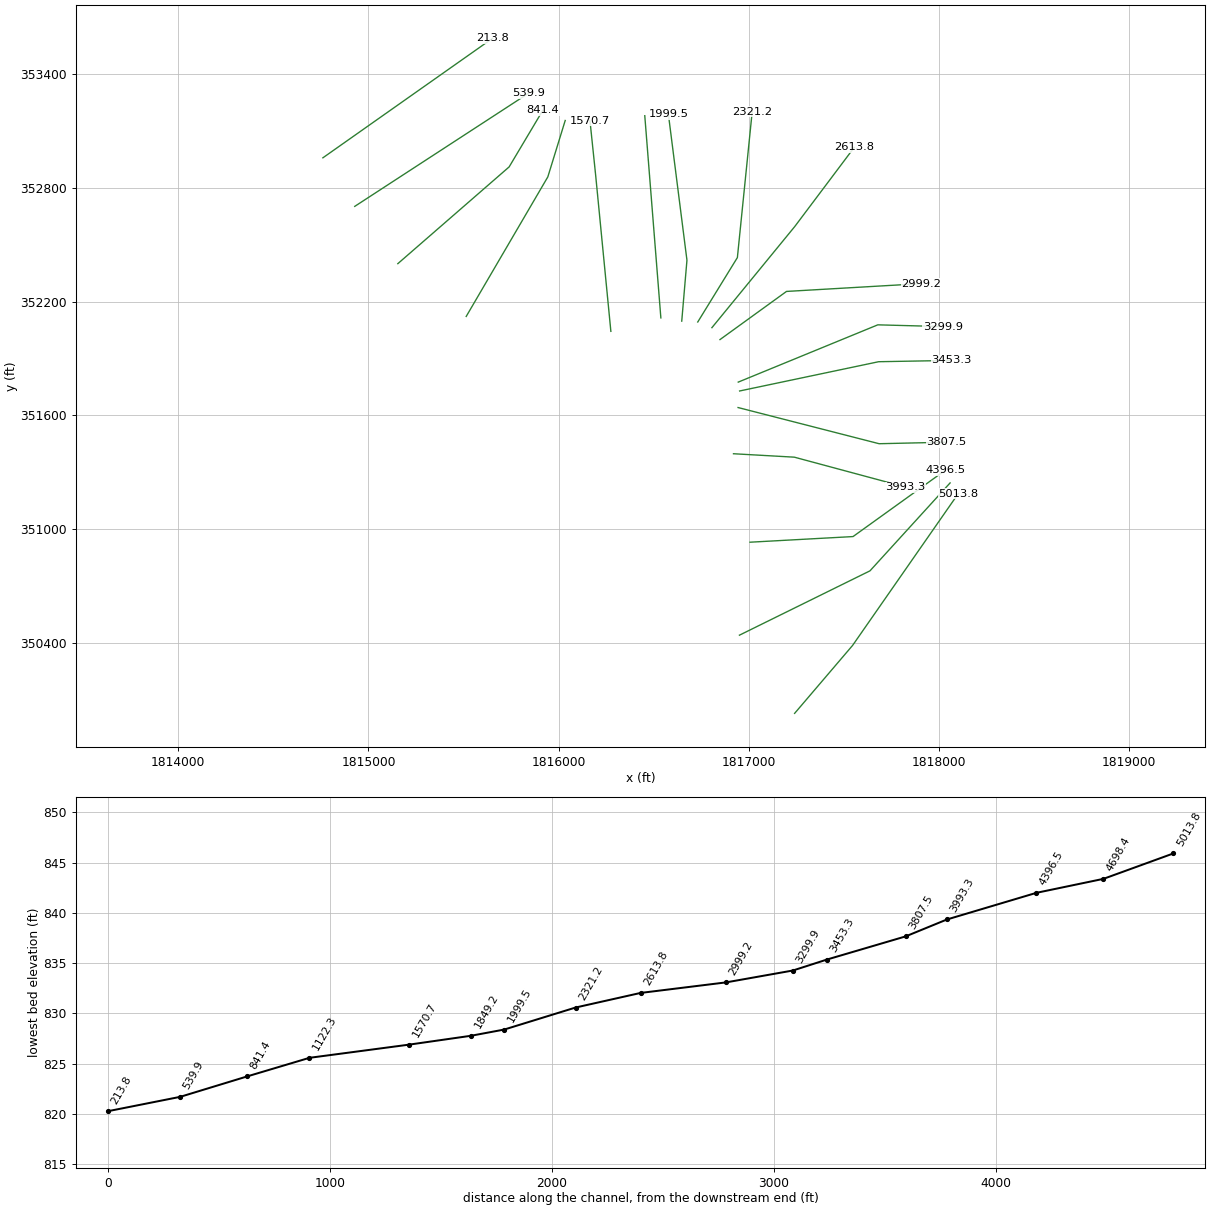
HEC-RAS study ClrFrk1.prj: ClrFrk1

--- ClrFrk1.g01 (geometry) --- (continued)

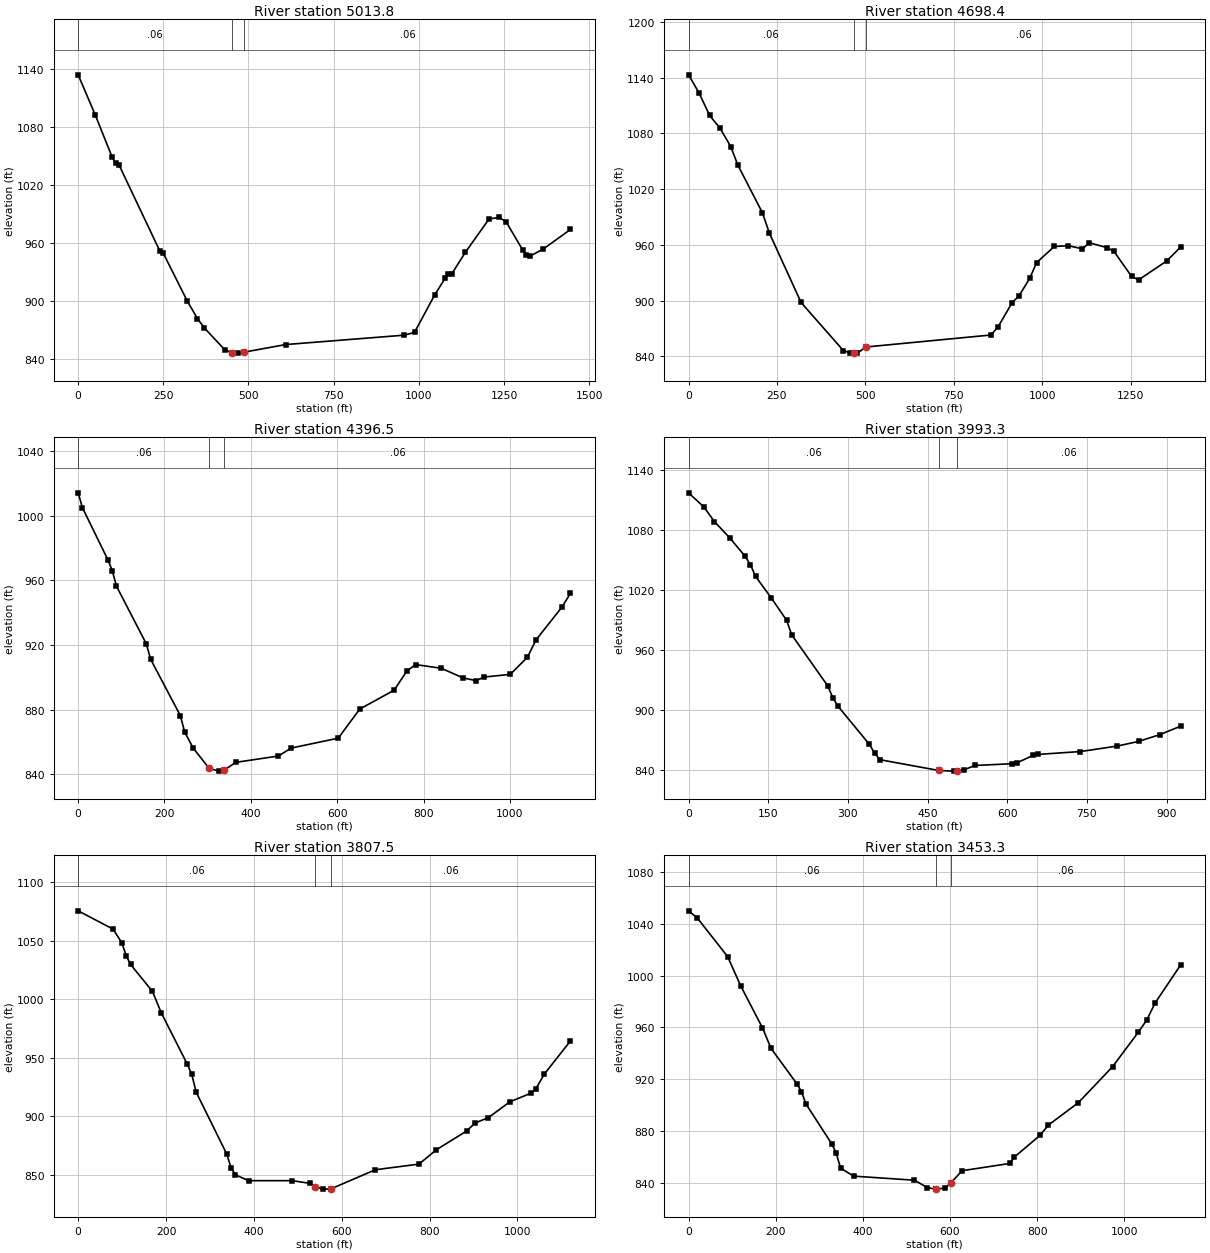
Type RM Length L Ch R = 1 ,5013.8  ,328.7,315.4,298.9
XS GIS Cut Line= 3
     1817241.288      350029.878     1817546.198      350388.003
     1818102.301      351188.517
#Sta/Elev= 30
       0 1133.48      50 1092.24   100.1 1048.13   110.1  1041.9   120.1 1040.26
   240.2   951.1   250.2  948.97   320.2   899.8   350.3  881.59   370.3  872.03
   430.3  849.42   452.8  845.97   470.3  845.91   487.8  846.97   609.6  854.78
   957.7  864.48   987.5   867.4  1047.2  906.42  1077.1  923.15    1087  927.53
    1097  927.89  1136.7  950.08  1206.4  984.59  1236.2  986.08  1256.1  981.79
  1305.8  951.97  1315.8  947.35  1325.7  946.03  1365.5  953.49  1445.1  973.67
#Mann= 3 , 0 , 0
       0     .06       0   452.8    .045       0   487.8     .06       0
Bank Sta=452.8,487.8
XS Rating Curve= 0 ,0
Exp/Cntr=0.3,0.1

Type RM Length L Ch R = 1 ,4698.4  ,315,301.9,288.7
XS GIS Cut Line= 3
     1816951.094       350442.01     1817637.657      350781.073
     1818058.954      351244.381
#Sta/Elev= 30
       0 1143.21    29.8 1123.59    59.7 1099.41    89.5 1085.48   119.3 1065.92
   139.2 1046.17   208.8  994.63   228.7  972.61   318.2  897.93   437.6  846.21
   457.4  843.38   466.5  843.38   477.3   843.4   501.5  849.98   855.2  862.92
   875.1  871.62   914.8  897.62   934.7  905.23   964.5  923.86   984.4  940.96
  1034.1  958.28  1073.9  959.12  1113.6  955.76  1133.5  962.27  1183.2  957.03
  1203.1  952.91  1252.8  925.97  1272.7  922.33  1352.2   942.7  1391.9  957.81
#Mann= 3 , 0 , 0
       0     .06       0   466.5    .045       0   501.5     .06       0
Bank Sta=466.5,501.5
XS Rating Curve= 0 ,0
Exp/Cntr=0.3,0.1

Type RM Length L Ch R = 1 ,4396.5  ,413.4,403.2,393
XS GIS Cut Line= 3
     1817006.557      350931.989      1817548.48      350961.714
     1818033.398      351310.886
#Sta/Elev= 30
       0 1014.26     9.9 1005.05    69.1  972.69    78.9  966.18    88.8  956.46
   157.9  920.78   167.8  911.29   236.8  876.31   246.7  866.22   266.4  856.26
   303.4  843.73   325.6  841.99   338.4  842.59   365.1  847.42   463.8  851.34
   493.4  856.25   602.5   862.4   652.3  880.41     732  892.09   761.8  904.07
   781.8  907.94   841.5  905.64   891.3  899.72   921.2  898.03   941.1  900.24
  1000.9  901.88  1040.7  912.47  1060.6  923.24  1120.4   943.4  1140.3  952.04
#Mann= 3 , 0 , 0
       0     .06       0   303.4    .045       0   338.4     .06       0
Bank Sta=303.4,338.4
XS Rating Curve= 0 ,0
Exp/Cntr=0.3,0.1

Type RM Length L Ch R = 1 ,3993.3  ,185.6,185.8,186
XS GIS Cut Line= 3
     1816919.779      351398.209      1817239.79      351380.161
     1817825.158      351222.386
#Sta/Elev= 30
       0 1117.63    29.1 1103.37    48.6 1088.93    77.7 1072.52   106.8 1054.01
   116.6 1045.65   126.3 1034.01   155.4 1012.79   184.5  990.27   194.2   975.7
   262.2  924.48     272  912.22   281.7  904.02   340.4  866.18   350.3  857.45
   360.3  850.76   471.1  839.98   499.4  839.34   506.1  839.46   519.3   840.8
   539.2  844.99   608.7  846.75   618.7  847.73   648.5     855   658.4  856.06
   737.9  858.93   807.5  864.44   847.3  869.05     887  875.78   926.8  884.35
#Mann= 3 , 0 , 0
       0     .06       0   471.1    .045       0   506.1     .06       0
Bank Sta=471.1,506.1
XS Rating Curve= 0 ,0
Exp/Cntr=0.3,0.1

Type RM Length L Ch R = 1 ,3807.5  ,339.2,354.2,369.1
XS GIS Cut Line= 3
     1816943.876      351641.707     1817685.676      351451.045
     1818040.215      351459.061
#Sta/Elev= 30
       0 1075.53    79.6 1059.86    99.5  1048.1   109.4 1037.16   119.4 1029.66
   169.1 1006.67     189  988.49   248.7  944.27   258.6  935.74   268.6  920.58
   338.2  867.66   348.1  855.78   358.1  849.85   387.9   844.9   487.4   844.9
   527.2  842.62   539.9  839.76     557  837.66   574.9  837.81   676.4  854.22
   775.8  859.04   815.2  871.26   884.1  887.31   903.8  894.23   933.4  898.68
   982.6  912.28  1031.9  919.85  1041.7   923.3  1061.4  936.16  1120.5  964.26
#Mann= 3 , 0 , 0
       0     .06       0   539.9    .045       0   574.9     .06       0
Bank Sta=539.9,574.9
XS Rating Curve= 0 ,0
Exp/Cntr=0.3,0.1

Type RM Length L Ch R = 1 ,3453.3  ,147.5,153.4,159.4
XS GIS Cut Line= 3
     1816952.009      351728.975     1817683.389      351883.211
      1818065.25      351890.071
#Sta/Elev= 30
       0 1049.87    19.9 1044.45    89.7 1014.58   119.6  992.08   169.4  959.84
   189.4  943.77   249.2  916.28   259.1  910.53   269.1  901.15   328.9  870.05
   338.8  863.06   348.8  851.57   378.7  845.38   518.2  842.23   548.1  836.54
   566.8  835.37   568.1  835.36     588  836.15   601.8  840.26   627.9  849.56
   737.5  855.17   747.5  860.06   806.2  876.76   825.8  884.78   894.4  902.01
   972.7  929.66  1031.5  956.11    1051  965.55  1070.6  978.92  1129.4 1008.35
#Mann= 3 , 0 , 0
       0     .06       0   566.8    .045       0   601.8     .06       0
Bank Sta=566.8,601.8
XS Rating Curve= 0 ,0
Exp/Cntr=0.3,0.1

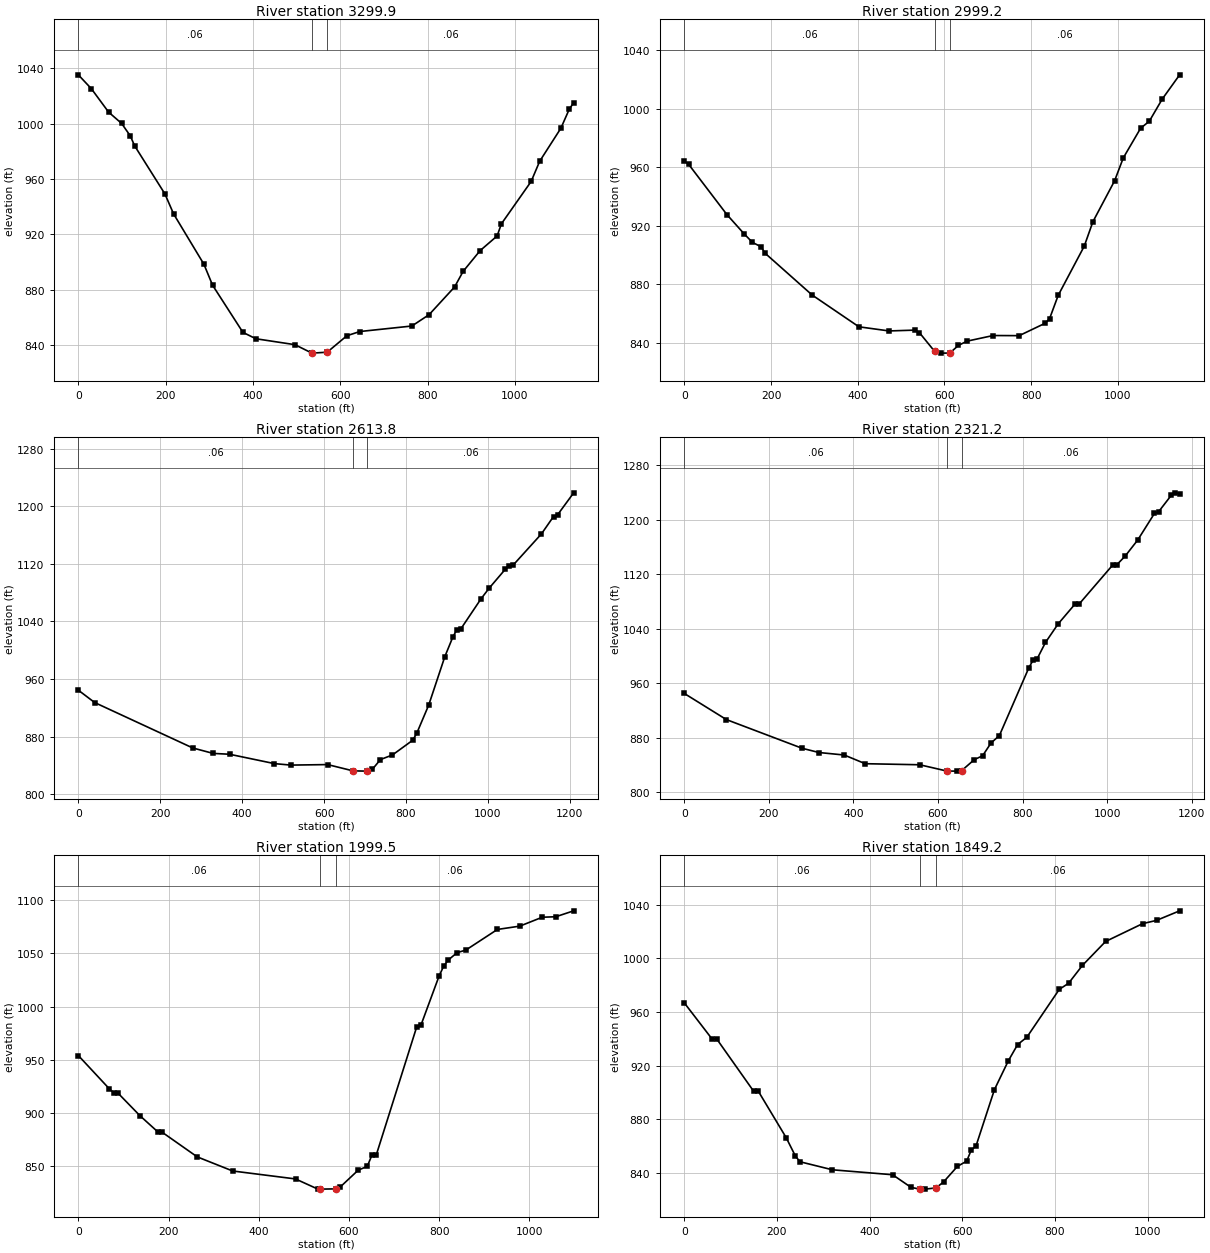
Type RM Length L Ch R = 1 ,3299.9  ,311.5,300.7,289.9
XS GIS Cut Line= 3
     1816944.819      351775.741     1817678.816      352077.572
     1818019.518      352068.425
#Sta/Elev= 30
       0 1035.33    29.8 1025.34    69.4 1008.38    99.2 1000.21     119  991.24
     129  984.03   198.4  949.26   218.2  934.87   287.7  898.46   307.5  883.34
     377  849.27   406.7  844.65     496  840.38     535   834.3   535.7  834.27
     570  834.94   615.1  846.84   644.8  849.88   763.9  853.86   803.4  862.06
   861.8   882.1   881.3  893.32   920.2  908.32   959.2  918.93   968.9  927.66
  1037.1   958.3  1056.6  972.86  1105.2  996.76  1124.7 1010.73  1134.5 1015.14
#Mann= 3 , 0 , 0
       0     .06       0     535    .045       0     570     .06       0
Bank Sta=535,570
XS Rating Curve= 0 ,0
Exp/Cntr=0.3,0.1

Type RM Length L Ch R = 1 ,2999.2  ,358.2,385.4,413.9
XS GIS Cut Line= 3
     1816848.787      351999.863     1817198.631      352253.639
     1817907.475      352294.798
#Sta/Elev= 30
       0  964.29     9.8  962.21    98.2   927.8   137.5  914.77   157.2  908.76
   176.8  905.82   186.6  901.29   294.7  872.83   402.7  851.08   472.2  848.25
   532.2  848.82   542.2  847.06   577.3  834.27   592.2  833.09   612.3  833.14
   632.2   838.4   652.2  841.29   712.2  845.12   772.2  845.03   832.2  853.52
   842.2  856.58   862.2  872.59   922.2  906.16   942.2   922.9   992.2  950.85
  1012.2  966.48  1052.2  986.78  1072.2  991.55  1102.2 1006.77  1142.2 1023.28
#Mann= 3 , 0 , 0
       0     .06       0   577.3    .045       0   612.3     .06       0
Bank Sta=577.3,612.3
XS Rating Curve= 0 ,0
Exp/Cntr=0.3,0.1

Type RM Length L Ch R = 1 ,2613.8  ,273.5,292.6,310.3
XS GIS Cut Line= 3
      1816806.33      352062.683     1817242.028      352595.673
     1817554.561      353012.359
#Sta/Elev= 30
       0  944.55    39.9  927.34   279.4  864.22   329.2  856.66   369.2  855.49
   478.9  842.46   518.8  840.42   608.6  841.13   670.9  832.38   705.9  832.05
   708.1  832.04   717.9  834.63   737.6  848.11     767  854.55   816.2  874.89
     826  884.34   855.5  923.95   894.8  991.19   914.4 1018.49   924.3 1028.74
   934.1  1029.9   983.2 1071.54  1002.9  1086.2  1042.2 1112.44    1052 1117.74
  1061.9 1118.52  1130.7 1161.73  1160.1 1185.83    1170  1188.2  1209.3 1218.73
#Mann= 3 , 0 , 0
       0     .06       0   670.9    .045       0   705.9     .06       0
Bank Sta=670.9,705.9
XS Rating Curve= 0 ,0
Exp/Cntr=0.3,0.1

Type RM Length L Ch R = 1 ,2321.2  ,314.1,321.6,329
XS GIS Cut Line= 3
     1816731.927      352092.634     1816940.246      352431.994
     1817018.215      353201.321
#Sta/Elev= 30
       0  944.78    99.6  906.35   278.7  864.17   318.6  857.94   378.3  854.27
   427.9  841.51   556.8  839.94   621.3  830.68     646  830.59   656.3  831.51
   685.7  847.39   705.5  853.18   725.4  871.91   745.2  882.87   814.6  982.12
   824.5  993.34   834.4  995.56   854.2 1019.72     884 1046.89   923.6  1075.8
   933.5 1075.97  1012.8 1133.26  1022.8 1133.89  1042.6 1146.61  1072.3 1170.26
    1112 1209.46  1121.9 1212.02  1151.6 1235.93  1161.6 1239.66  1171.5 1238.22
#Mann= 3 , 0 , 0
       0     .06       0   621.3    .045       0   656.3     .06       0
Bank Sta=621.3,656.3
XS Rating Curve= 0 ,0
Exp/Cntr=0.3,0.1

Type RM Length L Ch R = 1 ,1999.5  ,151.8,150.2,148.7
XS GIS Cut Line= 3
     1816647.629      352097.126     1816675.001      352418.274
     1816577.304      353187.935
#Sta/Elev= 30
       0  953.99    68.4  922.85    78.1  919.14    87.9  918.67   136.7  897.39
   175.8  882.39   185.6  881.95   263.7   858.7   342.2  845.45   481.5  837.98
   531.2   828.4   535.6   828.4   570.6  828.64   580.9   830.5   620.7   846.3
   640.6  849.77   650.6  860.06   660.5  860.43     750  980.63     760  982.95
   799.8 1028.68   809.7  1037.7   819.6 1043.53   839.5 1050.59   859.4 1053.15
   929.1 1072.47   978.8 1075.59  1028.5 1083.95  1058.4  1084.4  1098.2 1089.97
#Mann= 3 , 0 , 0
       0     .06       0   535.6    .045       0   570.6     .06       0
Bank Sta=535.6,570.6
XS Rating Curve= 0 ,0
Exp/Cntr=0.3,0.1

Type RM Length L Ch R = 1 ,1849.2  ,278,278.5,279.1
XS GIS Cut Line= 2
     1816537.806      352114.157     1816453.202       353179.71
#Sta/Elev= 30
       0  966.77    59.9  939.82    69.9  939.88   149.8  900.76   159.8   900.8
   219.8  866.24   239.8  852.45   249.7   848.2   319.7   842.2   449.5  838.52
   489.5  829.05   508.2  827.81   519.5  827.78   543.2   828.7   559.4  833.11
   589.4  844.74   609.4  848.69   619.4  857.09   629.4  859.87   669.3  902.06
   699.3  923.56   719.3  935.65   739.2  941.11   809.2  976.84   829.2  981.35
   859.1   994.7   909.1 1012.56     989 1025.87    1019  1028.3  1068.9 1035.43
#Mann= 3 , 0 , 0
       0     .06       0   508.2    .045       0   543.2     .06       0
Bank Sta=508.2,543.2
XS Rating Curve= 0 ,0
Exp/Cntr=0.3,0.1

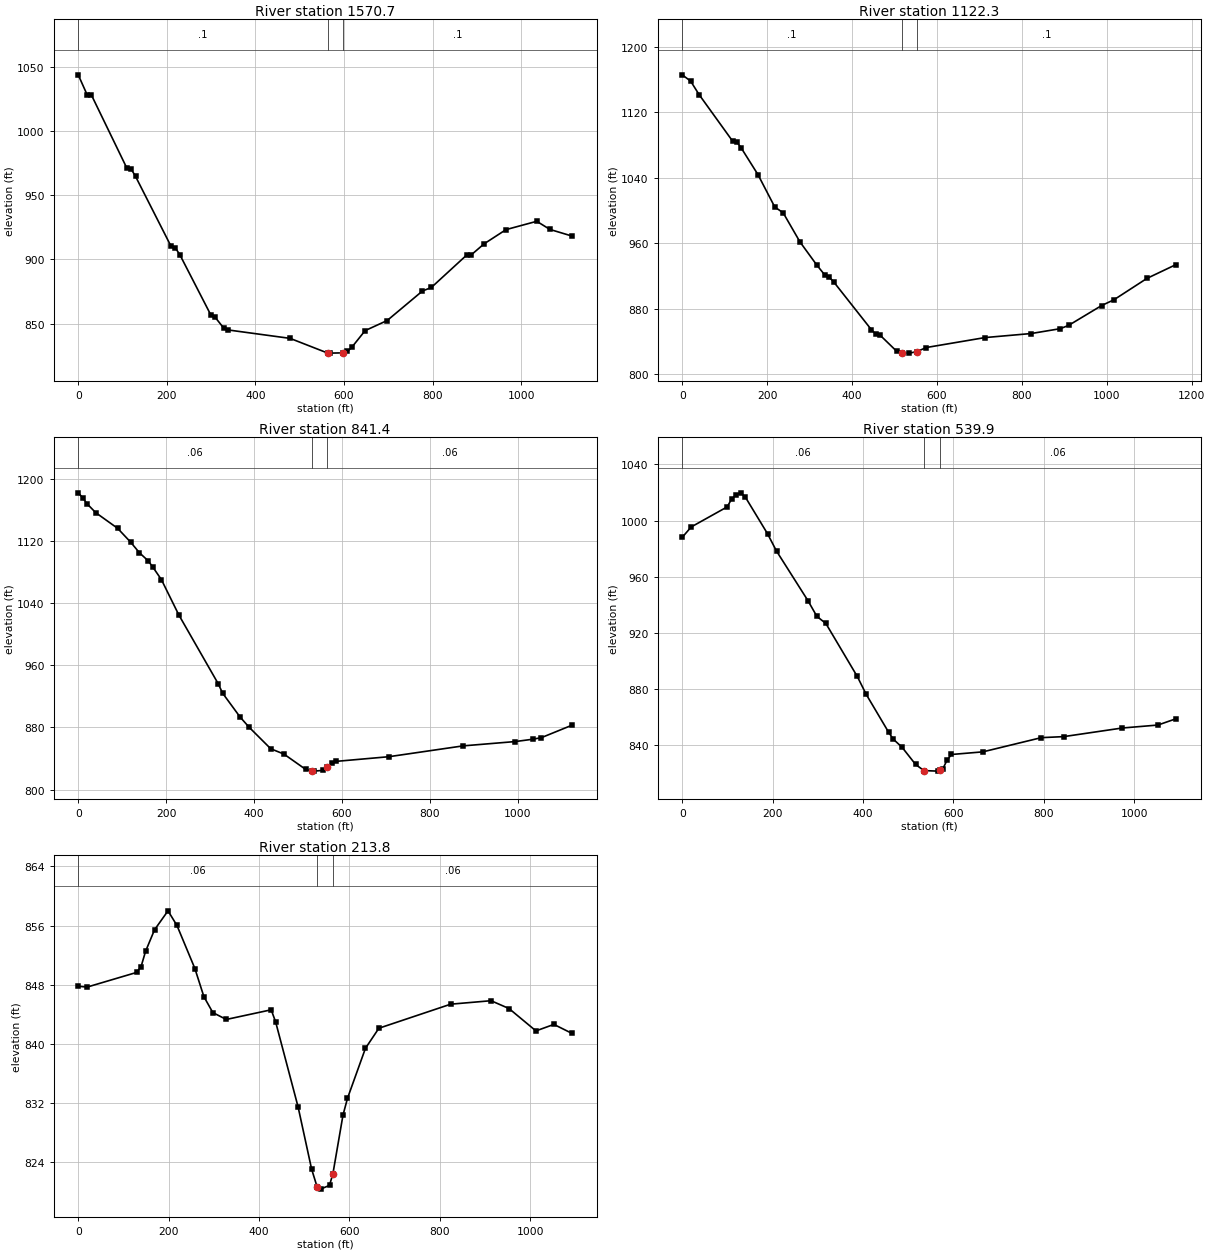
Type RM Length L Ch R = 1 ,1570.7  ,469,448.4,427.8
XS GIS Cut Line= 3
     1816274.848      352043.273     1816194.817      352866.447
     1816165.091      353152.271
#Sta/Elev= 30
       0  1044.1    19.9 1028.69    29.9 1028.28   109.6  971.42   119.6  970.51
   129.5  964.75   209.2  910.52   219.2  909.04   229.2  903.84   298.9     857
   308.9  854.97   328.8   846.3   338.8  844.97   478.3  838.42   562.9  826.99
     568   826.9   597.9  827.12   607.8  828.19   617.8  831.54   647.7  844.46
   697.5  852.35   777.2   875.4   797.2  878.13   876.6  903.32   886.5  903.34
   916.2  912.17   965.8  923.29  1035.2  929.79  1064.9  923.44  1114.4   918.3
#Mann= 3 , 0 , 0
       0      .1       0   562.9    .045       0   597.9      .1       0
Bank Sta=562.9,597.9
XS Rating Curve= 0 ,0
Exp/Cntr=0.3,0.1

Type RM Length L Ch R = 1 ,1122.3  ,291.6,280.9,270.3
XS GIS Cut Line= 3
     1815513.998      352121.753     1815943.291        352857.3
     1816034.755      353154.557
#Sta/Elev= 30
       0 1166.04    19.8 1158.29    39.6 1141.88   118.8 1084.78   128.7 1083.74
   138.6 1076.79   178.2 1044.08   217.9 1004.34   237.7  997.23   277.3  961.61
   316.9  933.33   336.7  920.56   346.6  918.14   356.5  912.87   445.6  854.19
   455.5  848.93   465.4  847.84     505   827.9   517.8  825.74   534.8  825.59
   552.8   827.4   574.4  832.41     713  844.61     822  849.57   890.5  855.52
     910  859.52   987.7  883.77  1016.9  890.88  1094.6  917.03  1162.7  933.84
#Mann= 3 , 0 , 0
       0      .1       0   517.8    .045       0   552.8      .1       0
Bank Sta=517.8,552.8
XS Rating Curve= 0 ,0
Exp/Cntr=0.3,0.1

Type RM Length L Ch R = 1 ,841.4   ,306,301.5,297
XS GIS Cut Line= 3
     1815154.417      352399.981     1815739.785      352909.892
     1815916.848       353207.77
#Sta/Elev= 30
       0 1182.52      10 1176.34    19.9 1168.48    39.8 1156.98    89.6 1136.77
   119.4 1118.81   139.3 1105.23   159.2 1094.82   169.2 1087.18   189.1 1070.74
   228.9 1025.03   318.5  936.33   328.4  924.24   368.2  893.47   388.2  880.63
   437.9  852.56   467.8  845.76   517.5  825.92   531.6  823.81   537.4  823.74
   557.4  824.81   566.6  828.87   577.3  834.14   587.2  836.35   706.6  842.33
   875.3  856.28   994.1  861.86  1033.7  864.84  1053.5  866.89  1122.8  882.87
#Mann= 3 , 0 , 0
       0     .06       0   531.6    .045       0   566.6     .06       0
Bank Sta=531.6,566.6
XS Rating Curve= 0 ,0
Exp/Cntr=0.3,0.1

Type RM Length L Ch R = 1 ,539.9   ,324.9,326.1,327.3
XS GIS Cut Line= 3
     1814927.779      352701.895     1815385.123      353000.145
     1815842.466      353298.395
#Sta/Elev= 30
       0  988.08    19.8  995.45    99.3 1009.71   109.2 1015.29   119.1 1018.41
     129 1019.73     139 1016.97   188.6  990.64   208.5  978.29     278  943.03
   297.8  931.83   317.7  926.77   387.2  889.06     407  876.29   456.6  849.34
   466.6  844.52   486.4  838.63   516.2  826.45   534.6  822.09   565.8  821.71
   569.6  822.16   575.8  822.89   585.7  829.51   595.6  833.55   665.1  835.43
   794.2  845.53   843.8  846.26   972.9  852.37  1052.3   854.5    1092  858.95
#Mann= 3 , 0 , 0
       0     .06       0   534.6    .045       0   569.6     .06       0
Bank Sta=534.6,569.6
XS Rating Curve= 0 ,0
Exp/Cntr=0.3,0.1

Type RM Length L Ch R = 1 ,213.8   ,222,213.8,205.6
XS GIS Cut Line= 3
     1814760.217      352957.798      1815206.29      353272.656
     1815652.362      353587.514
#Sta/Elev= 30
       0  847.77    19.8  847.66     129  849.64     139  850.42   148.9  852.49
   168.8  855.42   198.6  857.99   218.4  856.01   258.1  850.17     278  846.36
   297.8   844.2   327.6  843.27   426.9  844.58   436.8  842.92   486.4  831.42
   516.2  823.02   528.5  820.58   536.1  820.28   555.9  820.79   563.5  822.39
   585.7   830.3   595.6  832.57   635.4  839.36   665.1  842.08     824  845.34
   913.3  845.81     953  844.75  1012.6  841.72  1052.3   842.6    1092  841.39
#Mann= 3 , 0 , 0
       0     .06       0   528.5    .045       0   563.5     .06       0
Bank Sta=528.5,563.5
XS Rating Curve= 0 ,0
Exp/Cntr=0.3,0.1

Chan Stop Cuts=-1
Use User Specified Reach Order=0
Composite Channel Slope=5